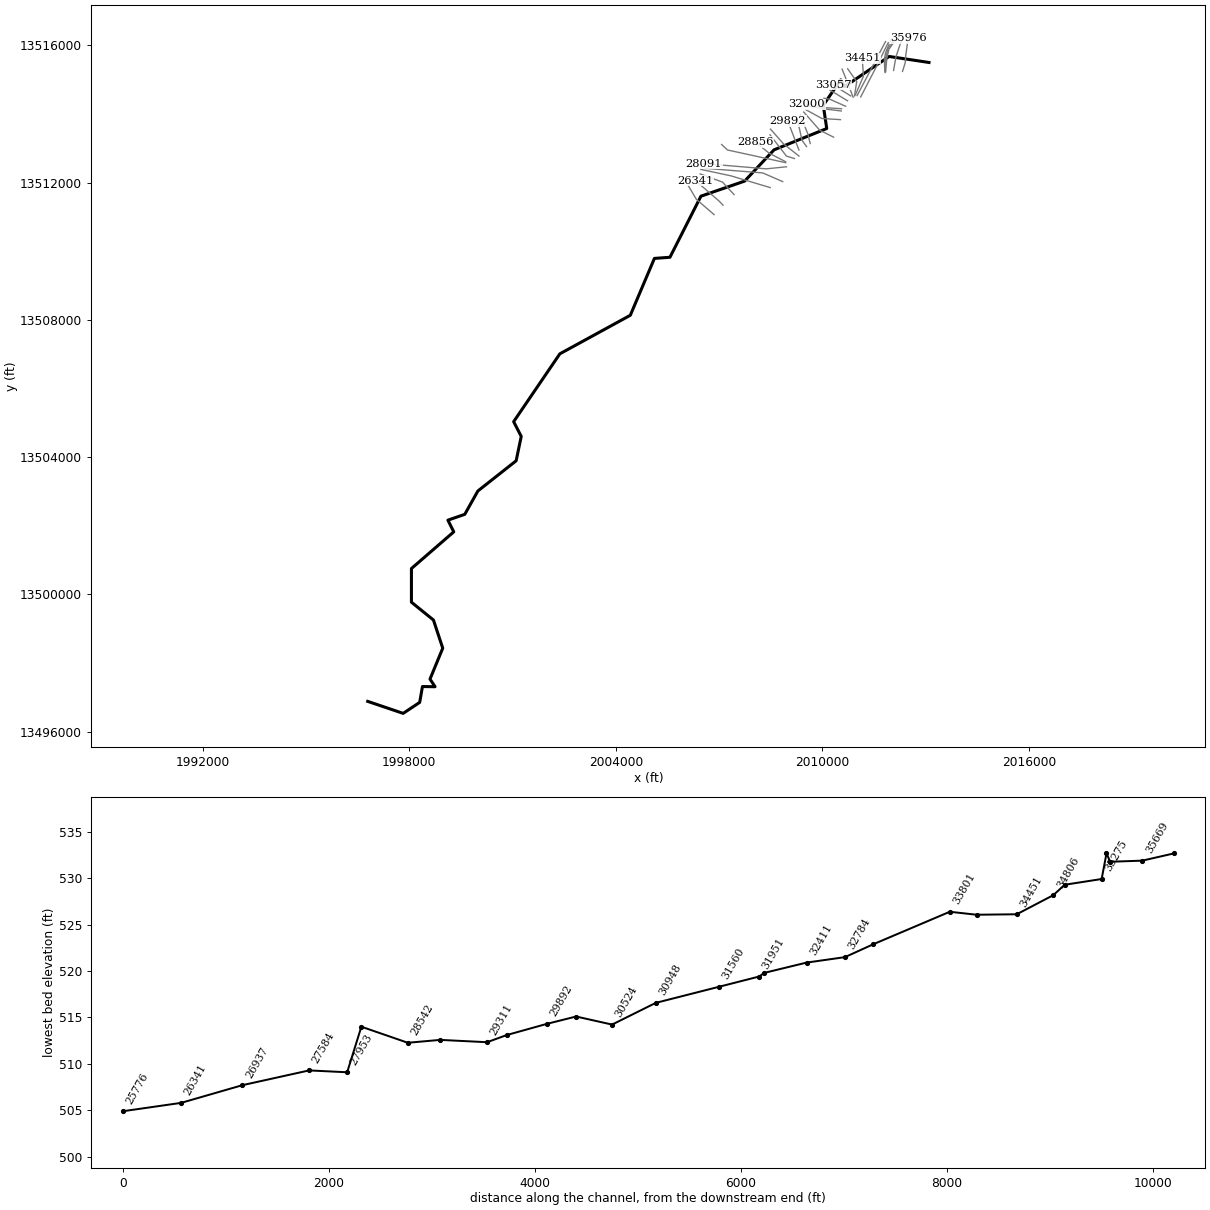
--- Cat Creek.prj (project) ---

Proj Title=Cat Creek Base Level Engineering
Current Plan=p01
Default Exp/Contr=0.3,0.1
English Units
Geom File=g01
Flow File=f01
Plan File=p01
Y Axis Title=Elevation
X Axis Title(PF)=Main Channel Distance
X Axis Title(XS)=Station
BEGIN DESCRIPTION:
Cat Creek
END DESCRIPTION:
DSS Export Rating Curves= 0
DSS Export Rating Curve Sorted= 0
DSS Export Volume Flow Curves= 0
DXF OffsetX= 0
DXF OffsetY= 0
DXF ScaleX= 1
DXF ScaleY= 10

--- Cat Creek.p01 (plan) ---

Plan Title=Multiple Run
Short Identifier=Multiple
Geom File=g01
Flow File=f01
Subcritical Flow
K Sum by GR= 0
Std Step Tol= 0.01
Critical Tol= 0.01
Num of Std Step Trials= 20
Max Error Tol= 0.3
Flow Tol Ratio= 0.001
Split Flow NTrial= 30
Split Flow Tol= 0.02
Split Flow Ratio= 0.02
Log Output Level= 0
Friction Slope Method= 1
Unsteady Friction Slope Method= 2
Unsteady Bridges Friction Slope Method= 1
Parabolic Critical Depth
Global Vel Dist=  1 , 1 , 1
Global Log Level= 0
CheckData=True
Encroach Param= -1, 0, 0, 0
BEGIN DESCRIPTION:
Multiple Run
END DESCRIPTION:

--- Cat Creek.f01 (steady flow) ---

Flow Title=Multiple
Program Version=5.05
Number of Profiles= 7
Profile Names=10-year,25-year,50-year,1pct_min,100-year,1pct_plu,500-year
River Rch & RM=Cat Creek,Reach-1         ,35976
     160     214     257     155     308     615     449
River Rch & RM=Cat Creek,Reach-1         ,35669
     219     298     363     220     439     876     653
River Rch & RM=Cat Creek,Reach-1         ,33057
     297     412     506     310     618    1232     935
River Rch & RM=Cat Creek,Reach-1         ,30524
     335     465     572     350     699    1395    1060
River Rch & RM=Cat Creek,Reach-1         ,26937
     376     526     650     400     798    1592    1222
River Rch & RM=Cat Creek,Reach-1         ,24746
     414     579     716     440     879    1754    1345
River Rch & RM=Cat Creek,Reach-1         ,20058
     445     623     771     474     946    1888    1448
River Rch & RM=Cat Creek,Reach-1         ,16957
     477     669     829     510    1018    2032    1561
River Rch & RM=Cat Creek,Reach-1         ,11265
     501     703     872     537    1071    2136    1641
Boundary for River Rch & Prof#=Cat Creek,Reach-1         , 1
Up Type= 0
Dn Type= 3
Dn Slope=0.005
Boundary for River Rch & Prof#=Cat Creek,Reach-1         , 2
Up Type= 0
Dn Type= 3
Dn Slope=0.005
Boundary for River Rch & Prof#=Cat Creek,Reach-1         , 3
Up Type= 0
Dn Type= 3
Dn Slope=0.005
Boundary for River Rch & Prof#=Cat Creek,Reach-1         , 4
Up Type= 0
Dn Type= 3
Dn Slope=0.005
Boundary for River Rch & Prof#=Cat Creek,Reach-1         , 5
Up Type= 0
Dn Type= 3
Dn Slope=0.005
Boundary for River Rch & Prof#=Cat Creek,Reach-1         , 6
Up Type= 0
Dn Type= 3
Dn Slope=0.005
Boundary for River Rch & Prof#=Cat Creek,Reach-1         , 7
Up Type= 0
Dn Type= 3
Dn Slope=0.005
DSS Import GetInterval= 0
DSS Import GetPeak= 0
DSS Import FillOption= 0

--- Cat Creek.g01 (geometry) ---

Geom Title=Existing Conditions
Program Version=5.05

River Reach=Cat Creek       ,Reach-1
Reach XY= 30
      2013096.33     13515500.62      2011938.63     13515675.66
       2010640.8     13514794.54       2010530.8     13514994.54
      2010024.77     13514253.49      2010125.46      13513576.4
      2008594.79     13512955.34       2007740.8     13512044.54
       2006470.8     13511604.54       2005570.8     13509824.54
      2005119.71       13509792.      2004419.63     13508134.23
      2002372.54     13507011.53       2001030.8     13505034.54
       2001250.8     13504604.54      2001102.56     13503894.28
       1999990.8     13503014.54       1999610.8     13502334.54
       1999120.8     13502164.54       1999290.8     13501824.54
       1998060.8     13500754.54       1998060.8     13499774.54
       1998700.8     13499254.54       1998970.8     13498434.54
      1998600.76     13497533.67      1998747.28     13497310.75
      1998381.18     13497316.73       1998300.8     13496854.54
       1997820.8     13496534.54       1996790.8     13496884.54

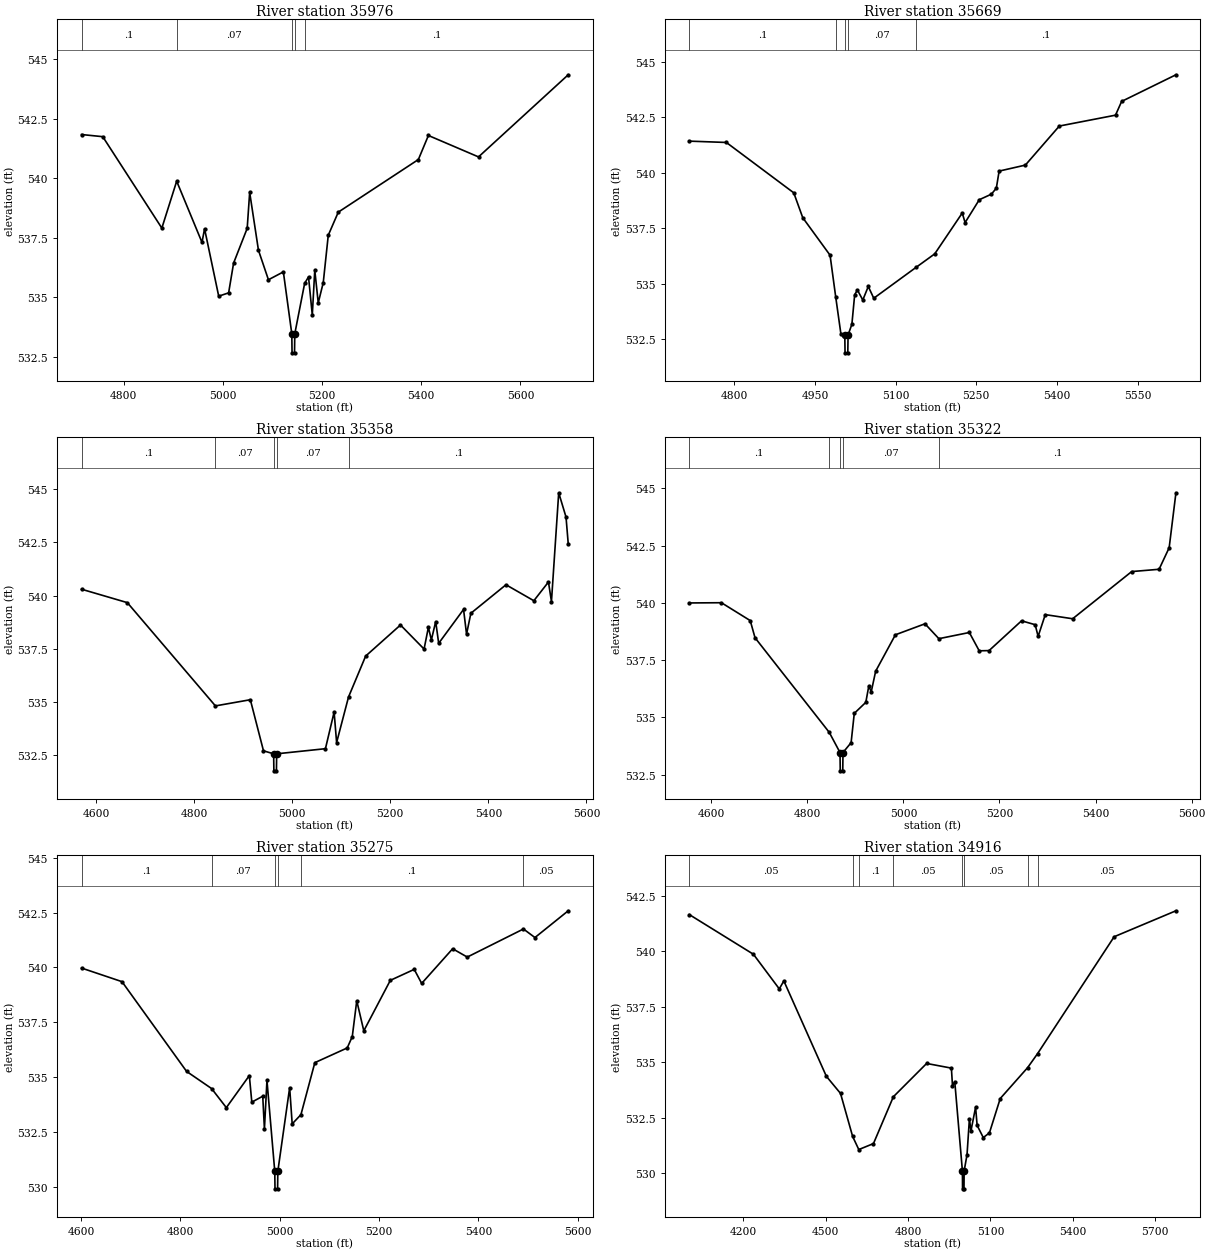
Type RM Length L Ch R = 1 ,35976   ,307,307,307
BEGIN DESCRIPTION:
Mapping XS 5bda5013
END DESCRIPTION:
XS GIS Cut Line= 4
       2012326.8     13515240.63      2012404.92      13515490.2
      2012417.95     13515681.17      2012489.56     13516204.16
#Sta/Elev= 30
  4715.4  541.84  4758.1  541.75  4877.2  537.91  4907.1  539.88  4958.1  537.31
  4963.3  537.88  4991.8  535.05  5011.8  535.19  5021.8  536.44  5049.2   537.9
  5054.2  539.41  5071.9  536.98    5092  535.74  5122.1  536.07  5139.1  533.47
  5139.6  532.67  5144.6  532.67  5145.1  533.47    5165  535.59  5172.8  535.86
  5180.4  534.26  5185.4  536.14  5192.4  534.77  5202.5  535.62  5212.6  537.61
  5232.8  538.58  5394.2  540.79  5414.4   541.8  5515.4   540.9  5696.2  544.35
#Mann= 5 ,-1 , 0
  4715.4      .1       0  4907.1     .07       0  5139.1     .07       0
  5145.1     .07       0    5165      .1       0
Bank Sta=5139.1,5145.1
XS Rating Curve= 0 ,0
Exp/Cntr=0.3,0.1

Type RM Length L Ch R = 1 ,35669   ,311,311,311
BEGIN DESCRIPTION:
Cat Creek 49.0
END DESCRIPTION:
XS GIS Cut Line= 3
      2012066.38     13515267.09      2012137.56     13515669.45
      2012293.98     13516140.87
#Sta/Elev= 30
  4716.1  541.43  4785.1  541.37  4910.5   539.1  4927.2  537.98    4978  536.29
  4988.5  534.41  4998.3  532.72  5005.4  532.69  5005.9  531.89    5011  531.89
  5011.5  532.69  5018.6  533.18  5023.8  534.51  5028.9  534.72  5038.9  534.27
  5049.1  534.88  5059.3  534.35  5137.9  535.74  5172.7  536.35  5223.9  538.19
  5229.2  537.76  5255.6  538.79  5278.1  539.04  5287.3  539.31  5292.5  540.08
  5341.3  540.35  5404.5  542.11    5509   542.6  5520.4  543.22  5621.4  544.42
#Mann= 5 ,-1 , 0
  4716.1      .1       0  4988.5     .07       0  5005.4     .07       0
  5011.5     .07       0  5137.9      .1       0
Bank Sta=5005.4,5011.5
XS Rating Curve= 0 ,0
Exp/Cntr=0.3,0.1

Type RM Length L Ch R = 1 ,35358   ,36,36,36
BEGIN DESCRIPTION:
Mapping XS bf19f99a
END DESCRIPTION:
XS GIS Cut Line= 4
      2011838.95     13515231.98      2011868.47     13515603.48
      2011930.97       13515883.      2012120.13     13516157.19
#Sta/Elev= 30
  4570.7   540.3    4664  539.67  4843.6  534.82  4914.8  535.11  4941.6  532.71
  4962.3  532.57  4962.8  531.77    4968  531.77  4968.5  532.57  5067.9  532.81
  5085.6  534.53  5090.7   533.1    5115  535.24  5149.9  537.16  5220.9  538.62
    5269  537.49  5277.8  538.51  5283.9  537.92  5292.7  538.78  5298.8  537.76
  5349.5  539.35  5355.6  538.19  5364.4  539.17    5436  540.51  5492.8  539.76
  5522.6  540.64  5528.7  539.72  5543.5  544.83  5558.4  543.69  5562.9  542.44
#Mann= 5 ,-1 , 0
  4570.7      .1       0  4843.6     .07       0  4962.3     .07       0
  4968.5     .07       0    5115      .1       0
Bank Sta=4962.3,4968.5
XS Rating Curve= 0 ,0
Exp/Cntr=0.3,0.1

Type RM Length L Ch R = 1 ,35322   ,47,47,47
BEGIN DESCRIPTION:
Mapping XS 56dd70de
END DESCRIPTION:
XS GIS Cut Line= 4
      2011823.33     13515208.06      2011823.33     13515553.14
      2011901.45     13515891.68      2012080.77     13516157.42
#Sta/Elev= 30
  4554.2     540  4621.1  540.01  4681.1  539.23  4691.1  538.48  4845.6  534.35
    4868  533.47  4868.5  532.67  4873.7  532.67  4874.2  533.47  4891.1   533.9
  4897.7  535.18  4921.7  535.66  4927.9  536.37    4933  536.12  4942.2  537.02
  4983.3  538.61  5044.9  539.09  5073.8  538.44  5137.2  538.71  5157.8  537.91
  5178.3  537.92  5245.9  539.22  5274.3  539.05  5280.4  538.54  5295.3  539.49
  5352.3  539.31  5475.2  541.37  5532.2  541.47  5553.2  542.41  5567.3  544.81
#Mann= 5 ,-1 , 0
  4554.2      .1       0  4845.6     .07       0    4868     .07       0
  4874.2     .07       0  5073.8      .1       0
Bank Sta=4868,4874.2
XS Rating Curve= 0 ,0
Exp/Cntr=0.3,0.1

Type RM Length L Ch R = 1 ,35275   ,359,359,359
BEGIN DESCRIPTION:
Mapping XS 3d35591a
END DESCRIPTION:
XS GIS Cut Line= 4
      2011812.91      13515233.7      2011799.02     13515598.27
      2011837.22     13515787.51      2011996.93     13516178.13
#Sta/Elev= 30
    4601  539.97  4682.4  539.35  4812.5  535.26  4862.8  534.48  4892.5  533.61
  4938.8  535.07  4943.8  533.86  4965.8  534.13  4969.2  532.64  4974.3  534.85
    4990  530.71  4990.5  529.91  4995.7  529.91  4996.2  530.71    5020  534.52
  5025.1  532.87  5042.7  533.29  5070.7  535.66  5135.9  536.33  5146.1  536.85
  5155.1  538.48  5169.3  537.11  5222.7  539.41  5270.8  539.91  5285.8  539.27
  5348.2  540.85  5377.6  540.47  5490.7  541.75  5513.9  541.36  5580.9  542.58
#Mann= 6 ,-1 , 0
    4601      .1       0  4862.8     .07       0    4990     .07       0
  4996.2     .07       0  5042.7      .1       0  5490.7     .05       0
Bank Sta=4990,4996.2
XS Rating Curve= 0 ,0
Exp/Cntr=0.3,0.1

Type RM Length L Ch R = 1 ,34916   ,110,110,110
BEGIN DESCRIPTION:
Cat Creek 48.0
END DESCRIPTION:
XS GIS Cut Line= 3
      2011111.07     13514495.38      2011549.46     13515343.93
      2011911.89     13516077.48
#Sta/Elev= 30
  4002.4  541.65  4236.2  539.86  4330.4   538.3    4347  538.66    4502  534.36
  4553.5  533.59  4597.7  531.65  4620.1  531.06  4673.6  531.33  4746.1  533.44
  4867.3  534.94  4957.5  534.73  4961.5  533.94  4969.8  534.12  4997.7  530.09
  4998.2  529.29  5003.4  529.29  5003.9  530.09  5014.5  530.83  5023.2  532.45
  5028.8   531.9  5045.7  532.97  5051.3  532.15  5073.7   531.6  5096.1  531.81
  5135.5  533.36  5235.2  534.75  5271.4  535.38  5550.6  540.65  5775.7  541.82
#Mann= 8 ,-1 , 0
  4002.4     .05       0  4597.7     .08       0  4620.1      .1       0
  4746.1     .05       0  4997.7     .04       0  5003.9     .05       0
  5235.2     .07       0  5271.4     .05       0
Bank Sta=4997.7,5003.9
XS Rating Curve= 0 ,0
Exp/Cntr=0.3,0.1

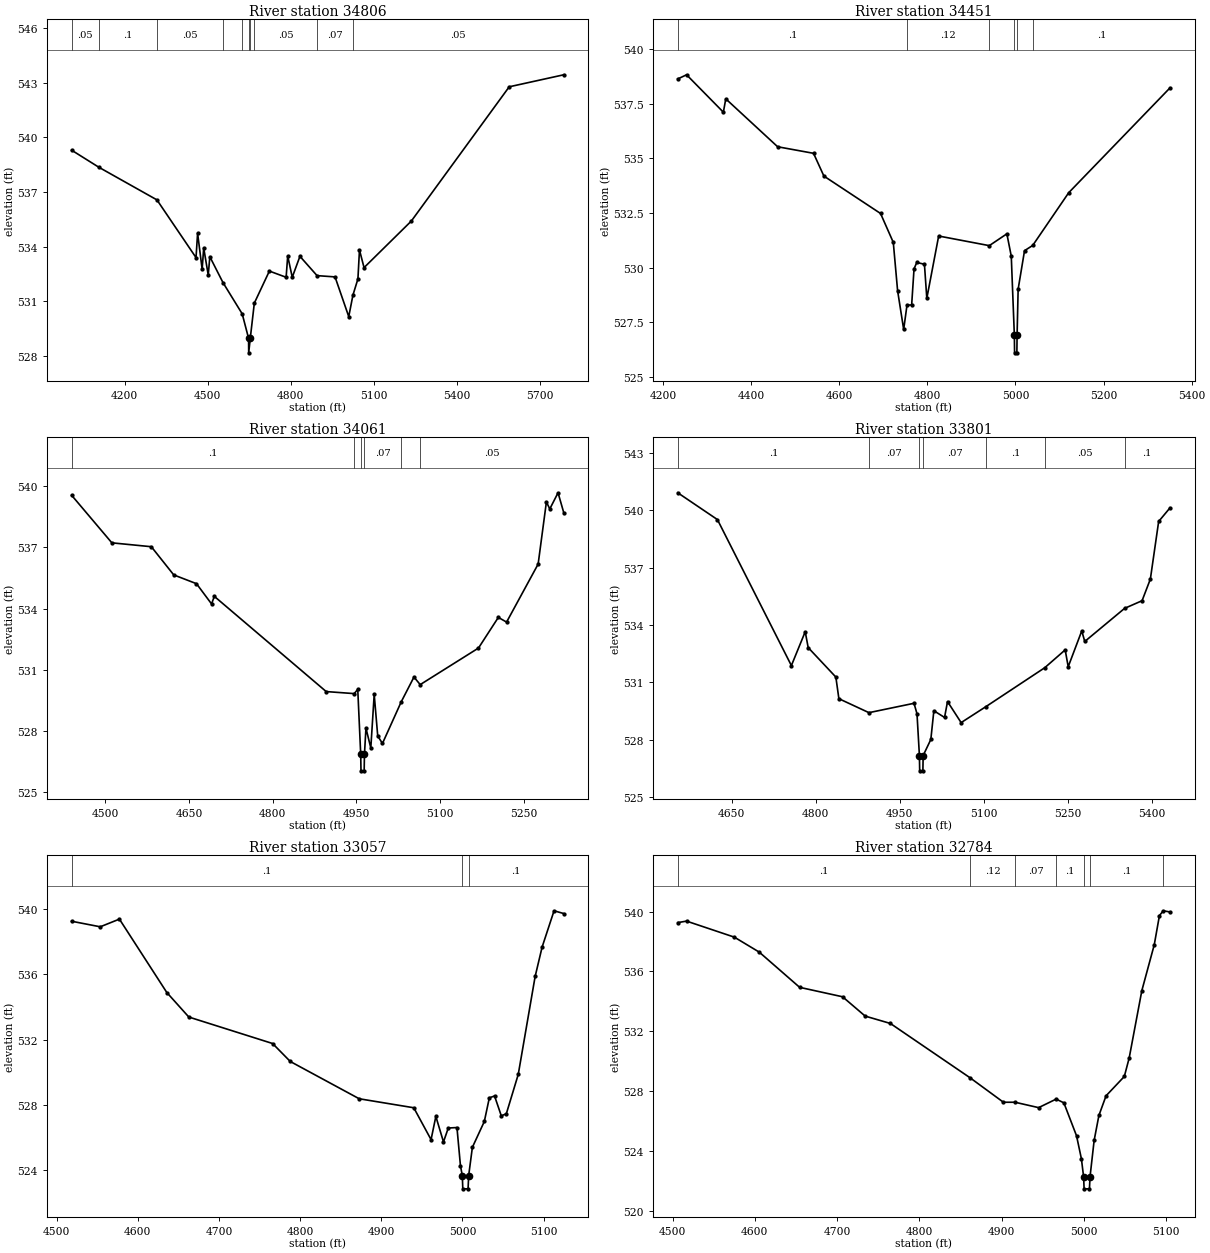
Type RM Length L Ch R = 1 ,34806   ,355,355,355
BEGIN DESCRIPTION:
Cat Creek 47.0
END DESCRIPTION:
XS GIS Cut Line= 3
      2011009.09     13514536.65        2011475.       13515425.
      2011833.76     13516110.03
#Sta/Elev= 30
  4008.7   539.3  4107.3  538.36  4316.7  536.57  4457.8   533.4  4463.5  534.74
  4479.9  532.76  4485.5  533.93  4501.9  532.44  4507.6  533.45    4555  532.03
  4624.5  530.31  4647.4  528.97  4647.9  528.17  4653.6  528.97  4668.2   530.9
  4722.5  532.66    4783  532.32  4788.7  533.49  4805.1  532.32  4832.8  533.47
  4894.6  532.41  4959.5  532.34    5009  530.16  5024.1  531.34  5042.1  532.23
  5047.7  533.82  5064.2  532.85    5235  535.41  5588.1  542.78  5785.1  543.44
#Mann= 10 ,-1 , 0
  4008.7     .05       0  4107.3      .1       0  4316.7     .05       0
    4555     .07       0  4624.5     .08       0  4647.4     .07       0
  4653.6     .08       0  4668.2     .05       0  4894.6     .07       0
  5024.1     .05       0
Bank Sta=4647.4,4653.6
XS Rating Curve= 0 ,0
Exp/Cntr=0.3,0.1

Type RM Length L Ch R = 1 ,34451   ,390,390,390
BEGIN DESCRIPTION:
Cat Creek 46.0
END DESCRIPTION:
XS GIS Cut Line= 3
      2010958.33     13514556.65      2011192.68     13515101.31
       2011155.8     13515624.27
#Sta/Elev= 30
  4233.4  538.63  4253.4  538.82  4336.9  537.11  4342.4  537.72  4460.1  535.53
  4541.6  535.23  4565.1  534.19  4693.7  532.48  4722.6  531.16  4732.4  528.95
  4746.2  527.18  4753.7  528.29  4764.3   528.3  4769.7  529.95  4775.9  530.24
  4793.3  530.16  4798.7   528.6  4825.6  531.45  4940.5  531.01  4980.4  531.55
  4990.4  530.53  4997.4  526.91  4997.9  526.11  5003.1  526.11  5003.6  526.91
    5006  529.02  5020.5  530.78  5039.1  531.02  5120.8  533.43  5350.6  538.22
#Mann= 6 ,-1 , 0
  4233.4      .1       0  4753.7     .12       0  4940.5     .07       0
  4997.4     .07       0  5003.6     .07       0  5039.1      .1       0
Bank Sta=4997.4,5003.6
XS Rating Curve= 0 ,0
Exp/Cntr=0.3,0.1

Type RM Length L Ch R = 1 ,34061   ,260,260,260
BEGIN DESCRIPTION:
Mapping XS b7480219
END DESCRIPTION:
XS GIS Cut Line= 3
      2010930.97     13514523.67      2010996.94      13514945.5
      2010733.03     13515317.06
#Sta/Elev= 30
  4439.3  539.55  4511.5  537.22  4582.3  537.03  4622.5  535.65  4663.3  535.22
  4690.3  534.23  4695.3   534.6  4895.9  529.94  4946.2  529.84  4952.5  530.05
  4957.8  526.86  4958.3  526.06    4964  526.06  4964.5  526.86  4967.2  528.15
  4975.9  527.18    4982   529.8  4988.3  527.77  4996.8   527.4  5030.5  529.44
  5053.3  530.65  5064.5  530.28    5169  532.07  5204.6  533.57  5219.4  533.34
    5276  536.18  5290.8  539.22  5296.9  538.88  5311.7  539.67    5322  538.69
#Mann= 6 ,-1 , 0
  4439.3      .1       0  4946.2     .07       0  4957.8     .07       0
  4964.5     .07       0  5030.5      .1       0  5064.5     .05       0
Bank Sta=4957.8,4964.5
XS Rating Curve= 0 ,0
Exp/Cntr=0.3,0.1

Type RM Length L Ch R = 1 ,33801   ,744,744,744
BEGIN DESCRIPTION:
Cat Creek 45.0
END DESCRIPTION:
XS GIS Cut Line= 3
       2010891.9     13514488.91        2010725.       13514925.
      2010572.01      13515307.5
#Sta/Elev= 30
  4553.4  540.91  4624.2  539.51  4756.3  531.88    4781  533.65  4786.3  532.82
  4835.7  531.28  4841.1  530.15  4894.8  529.42  4975.3  529.91  4980.6  529.36
  4984.9  527.18  4985.4  526.38  4991.1  526.38  4991.6  527.18  5005.3  528.02
  5010.7  529.52  5029.8  529.17  5035.1     530  5059.4   528.9  5103.9  529.74
  5208.8  531.77  5245.2   532.7  5250.6  531.82  5274.8  533.69  5280.2  533.14
  5351.3  534.87  5382.5  535.27  5397.3   536.4  5412.1  539.41  5432.3  540.12
#Mann= 7 ,-1 , 0
  4553.4      .1       0  4894.8     .07       0  4984.9     .07       0
  4991.6     .07       0  5103.9      .1       0  5208.8     .05       0
  5351.3      .1       0
Bank Sta=4984.9,4991.6
XS Rating Curve= 0 ,0
Exp/Cntr=0.3,0.1

Type RM Length L Ch R = 1 ,33057   ,273,273,273
BEGIN DESCRIPTION:
Cat Creek 44.0
END DESCRIPTION:
XS GIS Cut Line= 3
      2010824.97     13514525.02        2010425.       13514775.
      2010315.93     13514853.93
#Sta/Elev= 30
  4518.5  539.24  4553.8   538.9  4577.4  539.37  4635.8  534.88  4662.9  533.38
  4766.1  531.76  4787.9  530.66  4872.8  528.38    4940  527.83  4961.3  525.88
  4967.2   527.3  4976.6  525.74  4982.5  526.59  4993.2  526.62  4997.5  524.29
  4999.8  523.67  5000.4  522.87  5006.9  522.87  5007.6  523.67  5012.2  525.41
  5026.9  526.99  5033.1  528.44  5039.5  528.55  5047.8  527.34    5054  527.46
  5068.7  529.87  5089.5  535.86  5098.1  537.66  5112.8  539.88  5124.8  539.71
#Mann= 3 ,-1 , 0
  4518.5      .1       0  4999.8     .07       0  5007.6      .1       0
Bank Sta=4999.8,5007.6
XS Rating Curve= 0 ,0
Exp/Cntr=0.3,0.1

Type RM Length L Ch R = 1 ,32784   ,373,373,373
BEGIN DESCRIPTION:
Mapping XS 0462e67a
END DESCRIPTION:
XS GIS Cut Line= 2
      2010729.58     13514384.73      2010218.68     13514696.47
#Sta/Elev= 30
  4506.3  539.26    4517  539.36  4575.1  538.29  4605.4  537.29  4654.5  534.94
  4706.7  534.31  4734.2  533.02  4764.8  532.53  4861.8   528.9  4902.3  527.27
  4916.4  527.27  4945.1  526.91  4966.4  527.48  4975.8  527.23  4991.2  525.03
  4997.1   523.5  4999.8  522.29  5000.4  521.49  5006.9  521.49  5007.6  522.29
  5012.6  524.72  5018.4  526.39  5027.1   527.7  5049.3  528.99  5055.2  530.22
  5070.6  534.72  5085.7  537.78    5092  539.73  5096.7  540.05  5104.8  539.97
#Mann= 7 ,-1 , 0
  4506.3      .1       0  4861.8     .12       0  4916.4     .07       0
  4966.4      .1       0  4999.8     .07       0  5007.6      .1       0
  5096.7     .07       0
Bank Sta=4999.8,5007.6
XS Rating Curve= 0 ,0
Exp/Cntr=0.3,0.1

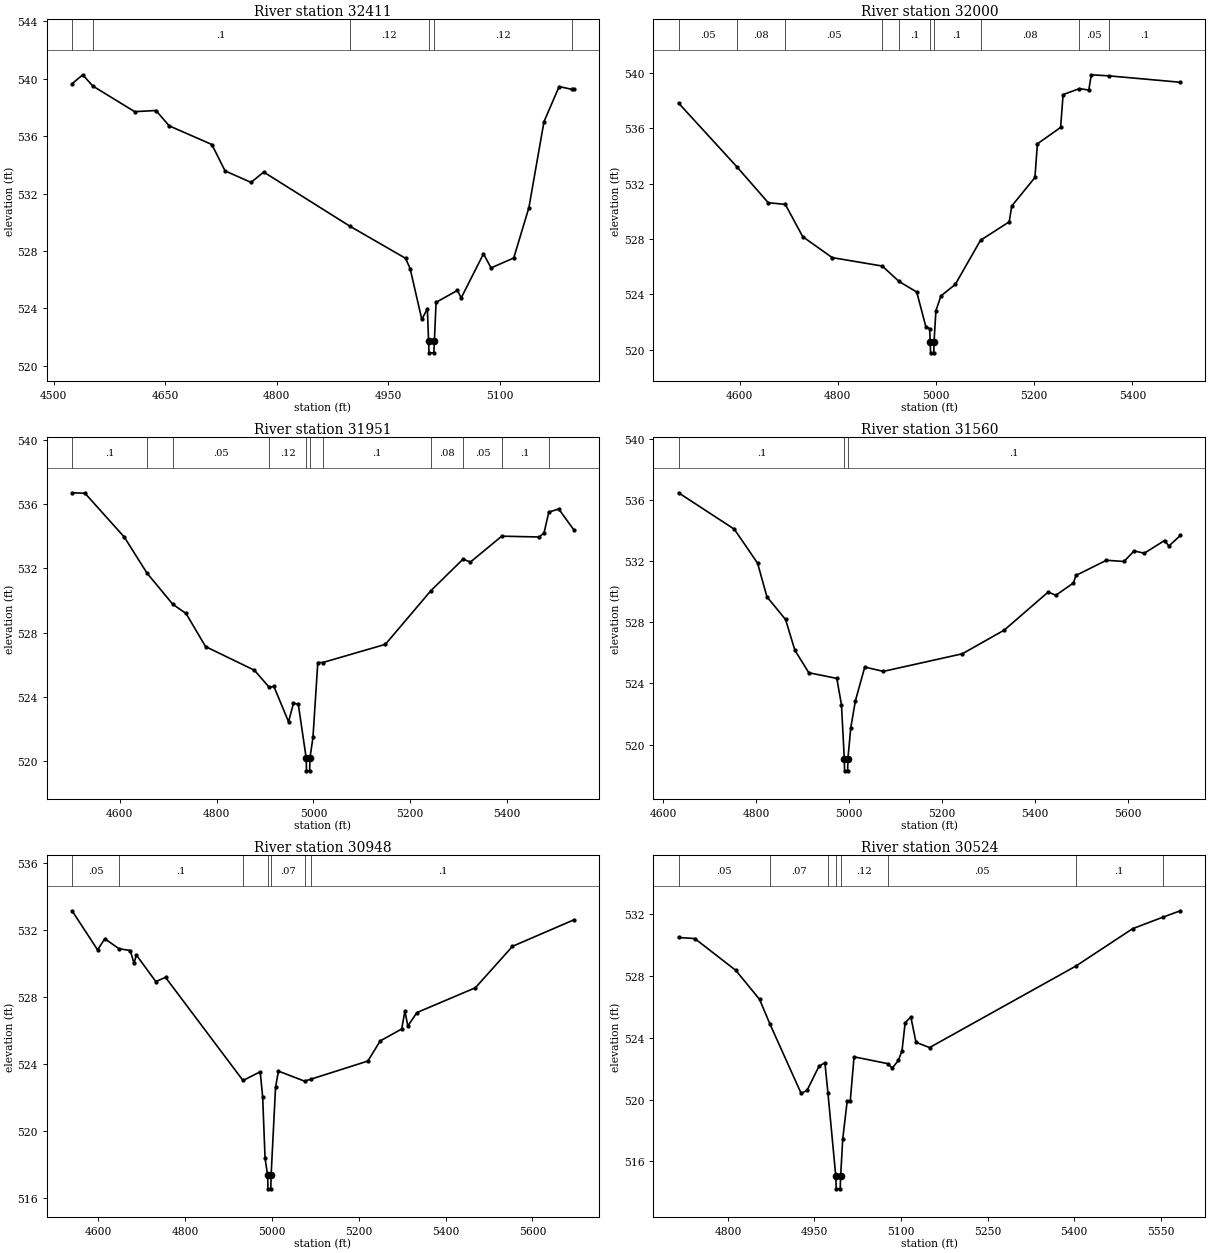
Type RM Length L Ch R = 1 ,32411   ,411,411,411
BEGIN DESCRIPTION:
Cat Creek 43.0
END DESCRIPTION:
XS GIS Cut Line= 3
      2010675.04     13514224.98        2010225.       13514425.
      2010045.55     13514459.38
#Sta/Elev= 30
  4524.8  539.66  4539.2  540.28  4552.6   539.5    4609  537.71  4637.7  537.79
  4655.5  536.72  4712.9  535.42  4730.7  533.58  4765.6  532.78  4782.7   533.5
  4898.2  529.74  4973.5  527.49  4979.7  526.77  4995.4  523.23  5002.9  523.97
  5004.5   521.7  5005.1   520.9  5011.6   520.9  5012.3   521.7  5014.6  524.42
  5043.3  525.25  5048.4  524.73  5078.4   527.8  5088.6  526.82  5119.1  527.51
  5139.5  531.02  5159.8  537.01  5180.2  539.46  5197.7  539.26    5200  539.26
#Mann= 6 ,-1 , 0
  4524.8     .05       0  4552.6      .1       0  4898.2     .12       0
  5004.5     .07       0  5012.3     .12       0  5197.7     .05       0
Bank Sta=5004.5,5012.3
XS Rating Curve= 0 ,0
Exp/Cntr=0.3,0.1

Type RM Length L Ch R = 1 ,32000   ,49,49,49
BEGIN DESCRIPTION:
Mapping XS a861df43
END DESCRIPTION:
XS GIS Cut Line= 3
      2010557.28     13514152.09      2010073.33     13514184.65
      2009545.94     13514284.48
#Sta/Elev= 30
  4475.8  537.81  4594.4  533.22  4658.5  530.62  4693.2   530.5  4728.7  528.17
  4788.8  526.66  4890.7  526.05  4924.8  524.94  4960.8  524.18  4979.5  521.67
  4987.1  521.54  4988.3  520.59    4989  519.79  4995.5  519.79  4996.1  520.59
  4999.9  522.83    5010  523.89  5039.4  524.73  5090.7  527.91  5149.2  529.24
  5154.3  530.38  5201.5  532.44  5206.6  534.87  5253.8  536.05  5258.9  538.42
    5292  538.85  5311.2  538.75  5316.3  539.85  5352.9  539.77  5497.6  539.31
#Mann= 10 ,-1 , 0
  4475.8     .05       0  4594.4     .08       0  4693.2     .05       0
  4890.7     .12       0  4924.8      .1       0  4988.3     .07       0
  4996.1      .1       0  5090.7     .08       0    5292     .05       0
  5352.9      .1       0
Bank Sta=4988.3,4996.1
XS Rating Curve= 0 ,0
Exp/Cntr=0.3,0.1

Type RM Length L Ch R = 1 ,31951   ,391,391,391
BEGIN DESCRIPTION:
Mapping XS b1e5d773
END DESCRIPTION:
XS GIS Cut Line= 3
      2010548.54       13514087.      2009966.99      13514158.6
      2009524.26      13514238.9
#Sta/Elev= 30
  4501.8   536.7  4528.5  536.67  4609.7  533.94  4656.3  531.71  4709.8  529.76
  4737.1  529.19  4777.4  527.13  4878.2  525.66  4908.7   524.6  4918.5  524.65
  4948.7  522.45  4958.8   523.6  4968.8  523.55  4985.1   520.2  4985.7   519.4
  4992.2   519.4  4992.9   520.2  4999.1  521.48  5009.1  526.14  5019.5  526.14
  5148.6  527.27  5242.6  530.61  5308.9  532.57  5324.2  532.39  5388.8     534
  5465.8  533.95    5476  534.19    5486   535.5  5506.5  535.69  5537.7  534.39
#Mann= 11 ,-1 , 0
  4501.8      .1       0  4656.3     .08       0  4709.8     .05       0
  4908.7     .12       0  4985.1     .07       0  4992.9     .12       0
  5019.5      .1       0  5242.6     .08       0  5308.9     .05       0
  5388.8      .1       0    5486     .05       0
Bank Sta=4985.1,4992.9
XS Rating Curve= 0 ,0
Exp/Cntr=0.3,0.1

Type RM Length L Ch R = 1 ,31560   ,612,612,612
BEGIN DESCRIPTION:
Mapping XS 4077c94e
END DESCRIPTION:
XS GIS Cut Line= 3
      2010524.73     13513835.25      2009986.52     13513867.81
      2009513.45     13514128.21
#Sta/Elev= 30
  4632.7  536.46  4752.7  534.08  4802.7  531.86  4822.8  529.66  4862.9  528.18
  4882.9  526.17  4912.9   524.7  4973.1  524.33  4983.1  522.61  4989.2  519.09
  4989.8  518.29  4996.4  518.29    4997  519.09  5003.1   521.1  5013.1  522.87
  5033.2  525.07  5073.2  524.79  5243.2  525.94  5333.4  527.49  5427.9  529.98
    5444  529.76  5481.8  530.56  5487.5  531.06  5552.9  532.05  5590.7  531.97
  5612.5  532.66  5634.3  532.51  5677.9  533.34  5687.3  532.98  5711.9  533.67
#Mann= 3 ,-1 , 0
  4632.7      .1       0  4989.2     .07       0    4997      .1       0
Bank Sta=4989.2,4997
XS Rating Curve= 0 ,0
Exp/Cntr=0.3,0.1

Type RM Length L Ch R = 1 ,30948   ,424,424,424
BEGIN DESCRIPTION:
Cat Creek 42.0
END DESCRIPTION:
XS GIS Cut Line= 3
      2010324.98     13513325.01        2009925.       13513525.
      2009457.04     13514056.57
#Sta/Elev= 30
  4540.1  533.14  4598.8  530.81  4615.5  531.47  4648.1  530.88  4674.2  530.77
  4682.6  530.01  4688.2   530.5  4732.9  528.92  4755.3  529.17  4933.7  523.02
  4973.3  523.54  4978.9  522.06  4984.5  518.37  4990.5  517.36  4991.1  516.56
  4997.7  516.56  4998.4  517.36  5008.6  522.61  5015.3  523.58  5075.5  522.98
  5090.1   523.1  5221.2  524.18  5249.6  525.38    5299  526.09  5306.5  527.15
  5313.2  526.27  5334.1  527.07  5468.8  528.55  5554.2  531.02  5695.5   532.6
#Mann= 7 ,-1 , 0
  4540.1     .05       0  4648.1      .1       0  4933.7     .07       0
  4990.5     .07       0  4998.4     .07       0  5075.5     .05       0
  5090.1      .1       0
Bank Sta=4990.5,4998.4
XS Rating Curve= 0 ,0
Exp/Cntr=0.3,0.1

Type RM Length L Ch R = 1 ,30524   ,349,349,349
BEGIN DESCRIPTION:
Cat Creek 41.0
END DESCRIPTION:
XS GIS Cut Line= 3
      2009645.81     13513138.65        2009575.       13513425.
      2009359.66     13513958.18
#Sta/Elev= 30
  4714.3   530.5  4742.5  530.43  4813.6  528.37  4854.8  526.49  4872.7   524.9
  4926.9   520.4  4937.2   520.6  4957.8  522.16  4968.1  522.39  4973.4   520.4
    4987  515.02  4987.7  514.22  4994.6  514.22  4995.3  515.02    4999  517.45
  5006.7   519.9    5012   519.9  5018.6  522.77    5077  522.33  5084.8  522.04
  5095.6  522.54  5101.8  523.18  5107.2  524.98  5117.1  525.35    5126  523.71
  5149.5  523.37  5402.8  528.64  5501.6  531.07  5553.7  531.81  5584.3  532.23
#Mann= 8 ,-1 , 0
  4714.3     .05       0  4872.7     .07       0  4973.4     .12       0
    4987     .07       0  4995.3     .12       0    5077     .05       0
  5402.8      .1       0  5553.7     .05       0
Bank Sta=4987,4995.3
XS Rating Curve= 0 ,0
Exp/Cntr=0.3,0.1

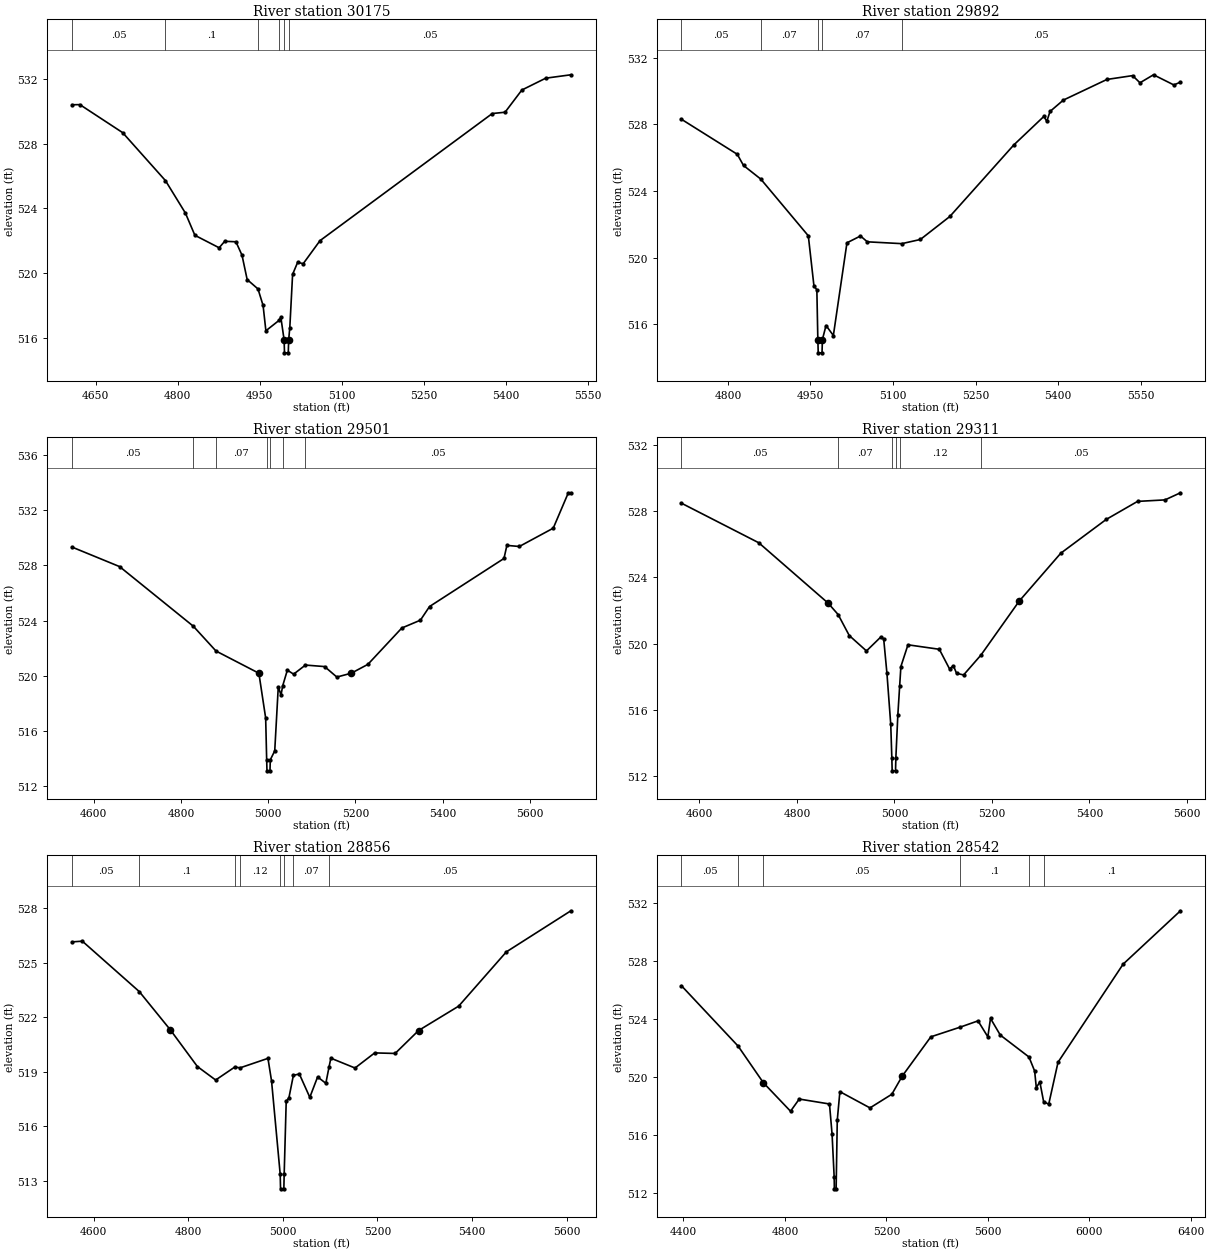
Type RM Length L Ch R = 1 ,30175   ,283,283,283
BEGIN DESCRIPTION:
Mapping XS 2866e146
END DESCRIPTION:
XS GIS Cut Line= 3
      2009539.47     13513049.66      2009407.09     13513234.13
      2009259.53     13513902.49
#Sta/Elev= 30
  4606.8  530.39  4621.3   530.4  4699.5  528.67  4777.7  525.71  4814.1  523.71
  4831.4  522.34  4875.7  521.57  4885.9  521.97  4906.4  521.94  4917.5  521.11
  4926.9  519.61  4946.7  519.03    4956  518.01  4961.1  516.45  4985.1  517.09
  4988.4  517.29  4994.4  515.89  4995.1  515.09    5002  515.09  5002.7  515.89
  5004.8  516.64  5009.9  519.93  5019.1  520.67  5029.3  520.59    5060  522.01
  5374.7  529.85    5398  529.93  5428.7   531.3  5472.3  532.03  5518.3  532.24
#Mann= 6 ,-1 , 0
  4606.8     .05       0  4777.7      .1       0  4946.7     .12       0
  4985.1     .05       0  4994.4     .03       0  5002.7     .05       0
Bank Sta=4994.4,5002.7
XS Rating Curve= 0 ,0
Exp/Cntr=0.3,0.1

Type RM Length L Ch R = 1 ,29892   ,391,391,391
BEGIN DESCRIPTION:
Mapping XS 818083d5
END DESCRIPTION:
XS GIS Cut Line= 2
      2009318.12     13512949.84      2008992.59      13513796.2
#Sta/Elev= 30
  4715.6  528.31    4817  526.21  4828.3  525.54  4859.8  524.72  4946.1  521.32
  4956.3  518.32  4961.6  518.08  4963.4   515.1  4964.1   514.3    4971   514.3
  4971.7   515.1  4978.3  515.94  4991.6  515.34  5016.3   520.9  5040.9  521.31
  5053.3  520.96    5116  520.85  5149.7   521.1  5203.3  522.48  5319.5  526.77
  5374.1  528.48  5379.5  528.19  5385.4  528.78  5409.5  529.46  5488.8   530.7
  5535.4  530.93  5548.8   530.5  5573.4  530.98  5610.4  530.37  5622.4  530.54
#Mann= 5 ,-1 , 0
  4715.6     .05       0  4859.8     .07       0  4963.4     .07       0
  4971.7     .07       0    5116     .05       0
Bank Sta=4963.4,4971.7
XS Rating Curve= 0 ,0
Exp/Cntr=0.3,0.1

Type RM Length L Ch R = 1 ,29501   ,190,190,190
BEGIN DESCRIPTION:
Mapping XS 2382228f
END DESCRIPTION:
XS GIS Cut Line= 3
      2009318.58     13512774.47      2008870.64     13513128.66
      2008492.17     13513559.21
#Sta/Elev= 30
  4550.1  529.34  4659.4  527.92  4828.5  523.59  4880.5  521.79 4978.84520.1781
  4994.4  516.92  4996.7  513.89  4997.4  513.09  5004.3  513.09    5005  513.89
  5015.2  514.54  5023.3  519.19  5029.6  518.59  5033.4  519.26  5044.1   520.4
  5058.5  520.11  5085.6  520.77  5129.6  520.66  5157.6   519.9 5190.67520.1783
  5228.8  520.82  5306.6  523.46  5349.3  524.03  5370.2  525.02  5540.9  528.51
  5547.6  529.46  5576.1  529.38  5653.9  530.71  5688.5  533.28  5694.4  533.28
#Mann= 7 ,-1 , 0
  4550.1     .05       0  4828.5      .1       0  4880.5     .07       0
  4996.7     .07       0    5005     .07       0  5033.4     .12       0
  5085.6     .05       0
Bank Sta=4978.84,5190.67
XS Rating Curve= 0 ,0
Exp/Cntr=0.3,0.1

Type RM Length L Ch R = 1 ,29311   ,455,455,455
BEGIN DESCRIPTION:
Mapping XS a33c7e49
END DESCRIPTION:
XS GIS Cut Line= 3
      2009186.57     13512701.59      2008955.71     13512772.75
      2008477.52     13513391.28
#Sta/Elev= 30
  4563.2  528.48  4721.8  526.09  4863.8  522.45  4884.4  521.76  4907.3  520.49
  4942.6  519.56  4971.6  520.39  4977.9  520.29  4984.6   518.2  4992.4  515.12
  4994.6  513.12  4995.3  512.32  5002.2  512.32  5002.9  513.12  5006.9  515.68
  5010.7  517.45  5013.2  518.62  5027.7  519.93    5092  519.66  5112.9  518.48
    5121  518.66  5127.3  518.21  5141.8  518.11  5177.4  519.31  5255.9  522.57
  5341.1  525.46  5434.3   527.5  5498.6  528.59  5554.8  528.68  5586.6  529.11
#Mann= 6 ,-1 , 0
  4563.2     .05       0  4884.4     .07       0  4994.6     .07       0
  5002.9     .07       0  5010.7     .12       0  5177.4     .05       0
Bank Sta=4863.8,5255.9
XS Rating Curve= 0 ,0
Exp/Cntr=0.3,0.1

Type RM Length L Ch R = 1 ,28856   ,314,314,314
BEGIN DESCRIPTION:
Cat Creek 38.0
END DESCRIPTION:
XS GIS Cut Line= 3
      2008929.64     13512609.92       2008453.1      13512857.3
      2008049.75     13513182.59
#Sta/Elev= 30
    4554  526.14    4576  526.18  4696.4  523.41    4762  521.31  4819.3  519.29
  4857.9  518.55  4898.2  519.26  4909.7  519.22  4968.5  519.74  4976.1   518.5
  4994.4  513.37  4995.1  512.57  5002.1  512.57  5002.8  513.37  5007.1  517.38
  5012.8  517.57  5022.3  518.81  5034.9  518.88    5057   517.6  5073.5  518.72
  5090.9  518.37  5097.7  519.27  5101.5  519.75  5152.6  519.21  5194.2  520.04
  5237.4  520.01    5287  521.27  5371.8  522.61  5472.5  525.59  5609.1  527.85
#Mann= 8 ,-1 , 0
    4554     .05       0  4696.4      .1       0  4898.2     .07       0
  4909.7     .12       0  4994.4     .07       0  5002.8     .12       0
  5022.3     .07       0  5097.7     .05       0
Bank Sta=4762,5287
XS Rating Curve= 0 ,0
Exp/Cntr=0.3,0.1

Type RM Length L Ch R = 1 ,28542   ,451,451,451
BEGIN DESCRIPTION:
Mapping XS 236d6522
END DESCRIPTION:
XS GIS Cut Line= 3
      2008934.87     13512581.26      2007242.16     13512951.05
      2007071.63     13513111.25
#Sta/Elev= 30
  4392.5  526.26  4615.7   522.1    4715  519.58  4822.3  517.61  4856.6  518.45
  4975.8  518.11    4986  516.03  4994.3  513.06    4995  512.26    5002  512.26
  5006.5     517  5016.8  518.96  5135.4  517.84  5221.5  518.78  5262.4  520.03
  5375.3  522.74  5491.4  523.41  5561.2  523.84  5599.9  522.74  5610.4  524.01
    5649  522.86    5762  521.35  5784.4  520.38  5790.9  519.24  5804.9  519.63
  5819.9  518.26  5839.9   518.1  5876.6  520.99  6133.1  527.75  6359.1  531.43
#Mann= 6 ,-1 , 0
  4392.5     .05       0  4615.7      .1       0    4715     .05       0
  5491.4      .1       0    5762     .07       0  5819.9      .1       0
Bank Sta=4715,5262.4
XS Rating Curve= 0 ,0
Exp/Cntr=0.3,0.1

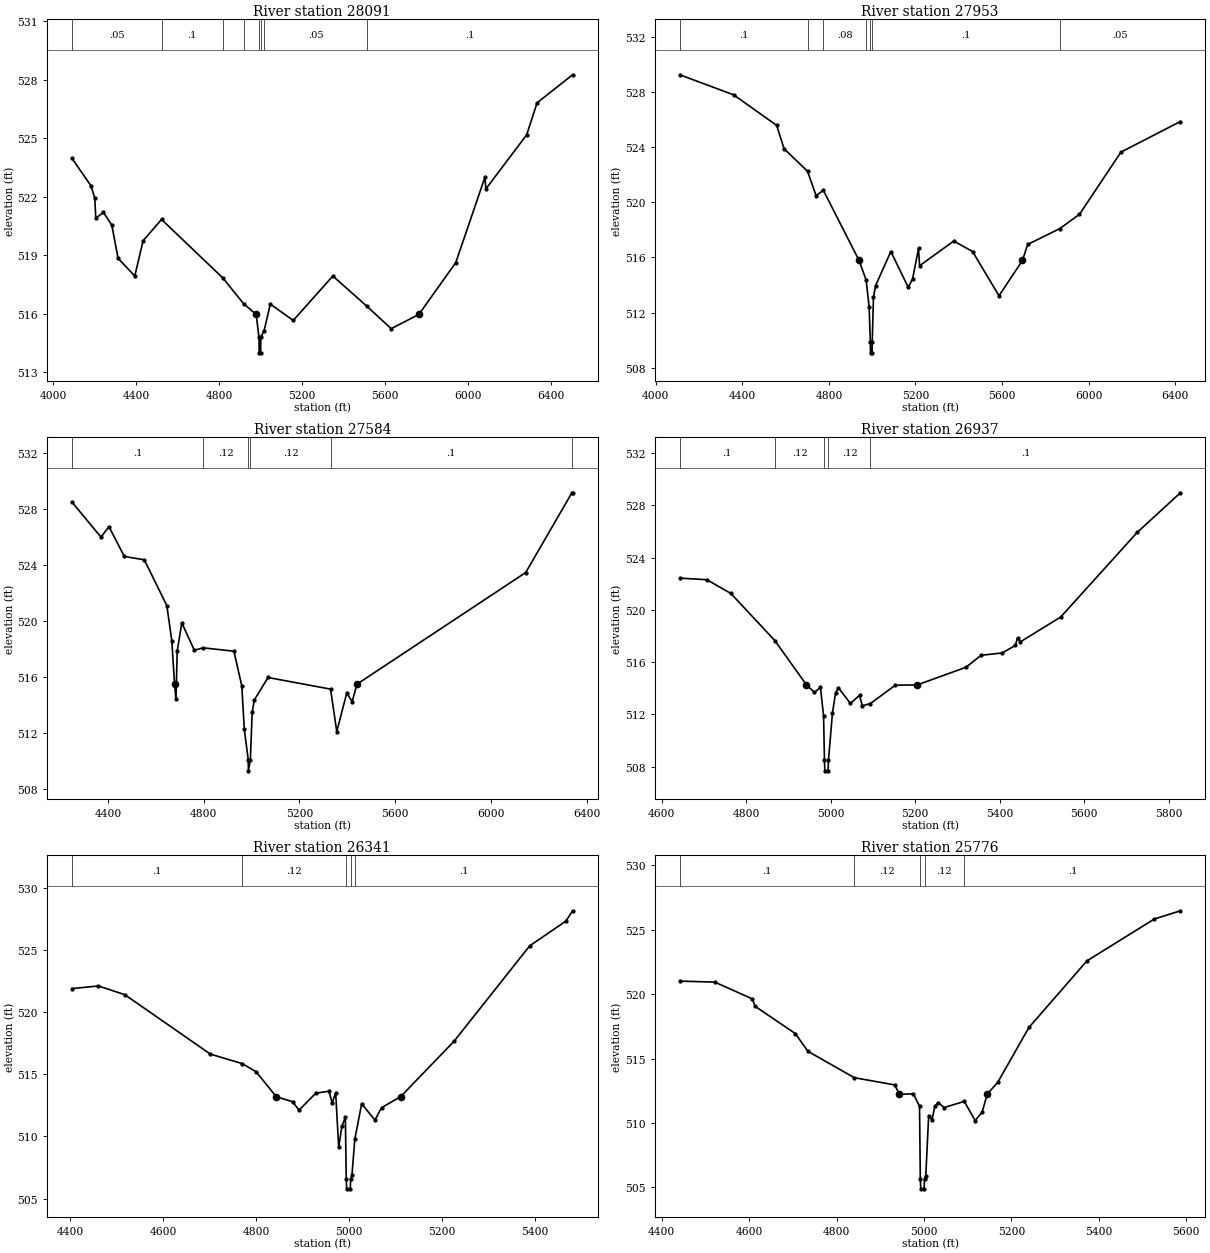
Type RM Length L Ch R = 1 ,28091   ,138,138,138
BEGIN DESCRIPTION:
Cat Creek 37.0
END DESCRIPTION:
XS GIS Cut Line= 3
      2008955.69     13512461.47      2008369.77     13512401.57
      2006554.63     13512555.22
#Sta/Elev= 30
    4092  523.96  4183.2  522.56  4201.5  521.93  4206.5   520.9  4243.5  521.19
  4283.7  520.54  4313.8  518.84  4394.3  517.93  4434.5  519.74  4523.2  520.83
  4819.3  517.82  4918.3  516.51 4978.89515.9598  4992.5  514.79  4993.3  513.99
  5000.5  513.99  5001.3  514.79  5017.2  515.13    5047  516.49  5157.4  515.65
  5348.1  517.93  5511.9  516.38  5629.1  515.23 5762.38515.9597  5940.2  518.62
  6080.4  522.99  6085.4   522.4  6281.4  525.17  6331.6  526.81  6502.6  528.25
#Mann= 8 ,-1 , 0
    4092     .05       0  4523.2      .1       0  4819.3     .07       0
  4918.3     .08       0  4992.5     .07       0  5001.3     .08       0
  5017.2     .05       0  5511.9      .1       0
Bank Sta=4978.89,5762.38
XS Rating Curve= 0 ,0
Exp/Cntr=0.3,0.1

Type RM Length L Ch R = 1 ,27953   ,369,369,369
BEGIN DESCRIPTION:
Cat Creek 36.0
END DESCRIPTION:
XS GIS Cut Line= 3
      2008846.29      13512029.2      2008268.21     13512281.78
      2006591.12      13512417.2
#Sta/Elev= 30
  4110.9  529.25  4360.3  527.79  4558.4  525.58  4592.7  523.89  4701.1  522.25
  4740.8  520.48  4774.1  520.87 4939.29515.7829  4971.9  514.36  4985.8  512.42
  4991.4  509.88  4992.2  509.08  4999.4  509.08  5000.2  509.88  5005.8  513.11
  5015.8  513.96  5086.1  516.43  5166.3  513.84  5186.4  514.42  5214.1  516.65
  5219.1   515.4    5377  517.19  5463.7  516.43    5586  513.22 5694.48515.7827
  5718.4  516.94  5866.6  518.09    5958  519.13  6149.5  523.64  6424.3  525.86
#Mann= 7 ,-1 , 0
  4110.9      .1       0  4701.1     .05       0  4774.1     .08       0
  4971.9      .1       0  4991.4     .07       0  5000.2      .1       0
  5866.6     .05       0
Bank Sta=4939.29,5694.48
XS Rating Curve= 0 ,0
Exp/Cntr=0.3,0.1

Type RM Length L Ch R = 1 ,27584   ,647,647,647
BEGIN DESCRIPTION:
Cat Creek 35.0
END DESCRIPTION:
XS GIS Cut Line= 3
      2008484.34      13511854.7      2007338.52     13512198.45
      2006463.56     13512385.94
#Sta/Elev= 30
  4250.4  528.48  4371.5  525.98  4404.6  526.73    4469   524.6  4552.5  524.36
  4646.4  521.09  4667.3  518.59 4678.76515.4747  4684.7  514.39  4689.9  517.84
  4709.1  519.85  4761.3   517.9  4798.4  518.07  4926.6  517.83  4959.7  515.35
  4970.1  512.26  4986.5  510.08  4987.3  509.28  4995.5  510.08  5003.2  513.49
  5011.9  514.34  5069.3  515.95  5330.5  515.12  5356.4  512.09  5398.1  514.84
  5420.8  514.23 5440.78 515.474  6145.7  523.45    6337   529.1  6341.5  529.15
#Mann= 6 ,-1 , 0
  4250.4      .1       0  4798.4     .12       0  4986.5     .07       0
  4995.5     .12       0  5330.5      .1       0    6337     .05       0
Bank Sta=4678.76,5440.78
XS Rating Curve= 0 ,0
Exp/Cntr=0.3,0.1

Type RM Length L Ch R = 1 ,26937   ,596,596,596
BEGIN DESCRIPTION:
Cat Creek 34.0
END DESCRIPTION:
XS GIS Cut Line= 3
      2007432.28     13511651.56      2007096.33     13512016.16
      2006448.98     13512252.74
#Sta/Elev= 30
    4643  522.43  4707.1  522.31  4763.8  521.26  4867.8  517.66 4942.86514.2628
  4961.7  513.69  4975.9  514.07  4983.3  511.91  4985.4  508.49  4986.3  507.69
    4994  507.69  4994.9  508.49  5004.3  512.11  5011.7  513.65  5018.5  514.04
  5046.8  512.85  5068.4  513.46  5075.2  512.66  5094.3  512.84  5153.1  514.24
 5204.92514.2628  5320.3  515.61  5356.2  516.53  5406.4  516.71  5437.1  517.28
  5442.5  517.86  5448.9  517.55  5544.8  519.46  5725.8  525.93    5828  528.96
#Mann= 5 ,-1 , 0
    4643      .1       0  4867.8     .12       0  4985.4     .07       0
  4994.9     .12       0  5094.3      .1       0
Bank Sta=4942.86,5204.92
XS Rating Curve= 0 ,0
Exp/Cntr=0.3,0.1

Type RM Length L Ch R = 1 ,26341   ,565,565,565
BEGIN DESCRIPTION:
Cat Creek 33.0
END DESCRIPTION:
XS GIS Cut Line= 3
      2007111.93      13511341.7      2007005.18     13511456.26
      2006310.18     13512060.16
#Sta/Elev= 30
  4403.9  521.92  4460.8  522.13  4517.5  521.43  4701.6  516.64  4770.4  515.87
  4800.3  515.21  4843.6513.2042  4878.7   512.8  4892.5  512.12  4928.6  513.49
  4957.1  513.65  4963.7  512.69  4971.3  513.52  4977.9  509.12  4984.7  510.83
  4992.2  511.54  4994.1  506.58    4995  505.78  5002.7  505.78  5003.6  506.58
  5006.4  506.89  5012.5  509.76  5027.3  512.64  5055.8  511.32    5070  512.32
 5110.99513.2043  5225.8  517.66  5389.1  525.37    5467  527.36  5481.2  528.19
#Mann= 5 ,-1 , 0
  4403.9      .1       0  4770.4     .12       0  4994.1     .07       0
  5003.6     .12       0  5012.5      .1       0
Bank Sta=4843.6,5110.99
XS Rating Curve= 0 ,0
Exp/Cntr=0.3,0.1

Type RM Length L Ch R = 1 ,25776   ,265,265,265
BEGIN DESCRIPTION:
Cat Creek 32.0
END DESCRIPTION:
XS GIS Cut Line= 3
      2006851.54     13511068.24      2006338.52     13511513.55
      2006101.52     13511914.62
#Sta/Elev= 30
  4441.2  521.01  4521.4  520.93  4606.9  519.63  4613.5  519.05  4705.7  516.93
  4734.2  515.56  4840.4  513.51  4932.6  512.95 4943.67 512.221  4975.4  512.26
  4989.6  511.29  4991.4  505.68  4992.4  504.88  5000.1  504.88    5001  505.68
  5003.9  505.86  5010.5  510.55  5018.1  510.24  5024.7  511.29  5032.4  511.58
  5045.7  511.19    5092  511.67  5116.8  510.18  5132.7  510.82 5144.34512.2207
  5168.7  513.16  5239.9  517.41  5372.6  522.58  5526.7  525.83  5586.4  526.47
#Mann= 5 ,-1 , 0
  4441.2      .1       0  4840.4     .12       0  4991.4     .07       0
    5001     .12       0    5092      .1       0
Bank Sta=4943.67,5144.34
XS Rating Curve= 0 ,0
Exp/Cntr=0.3,0.1