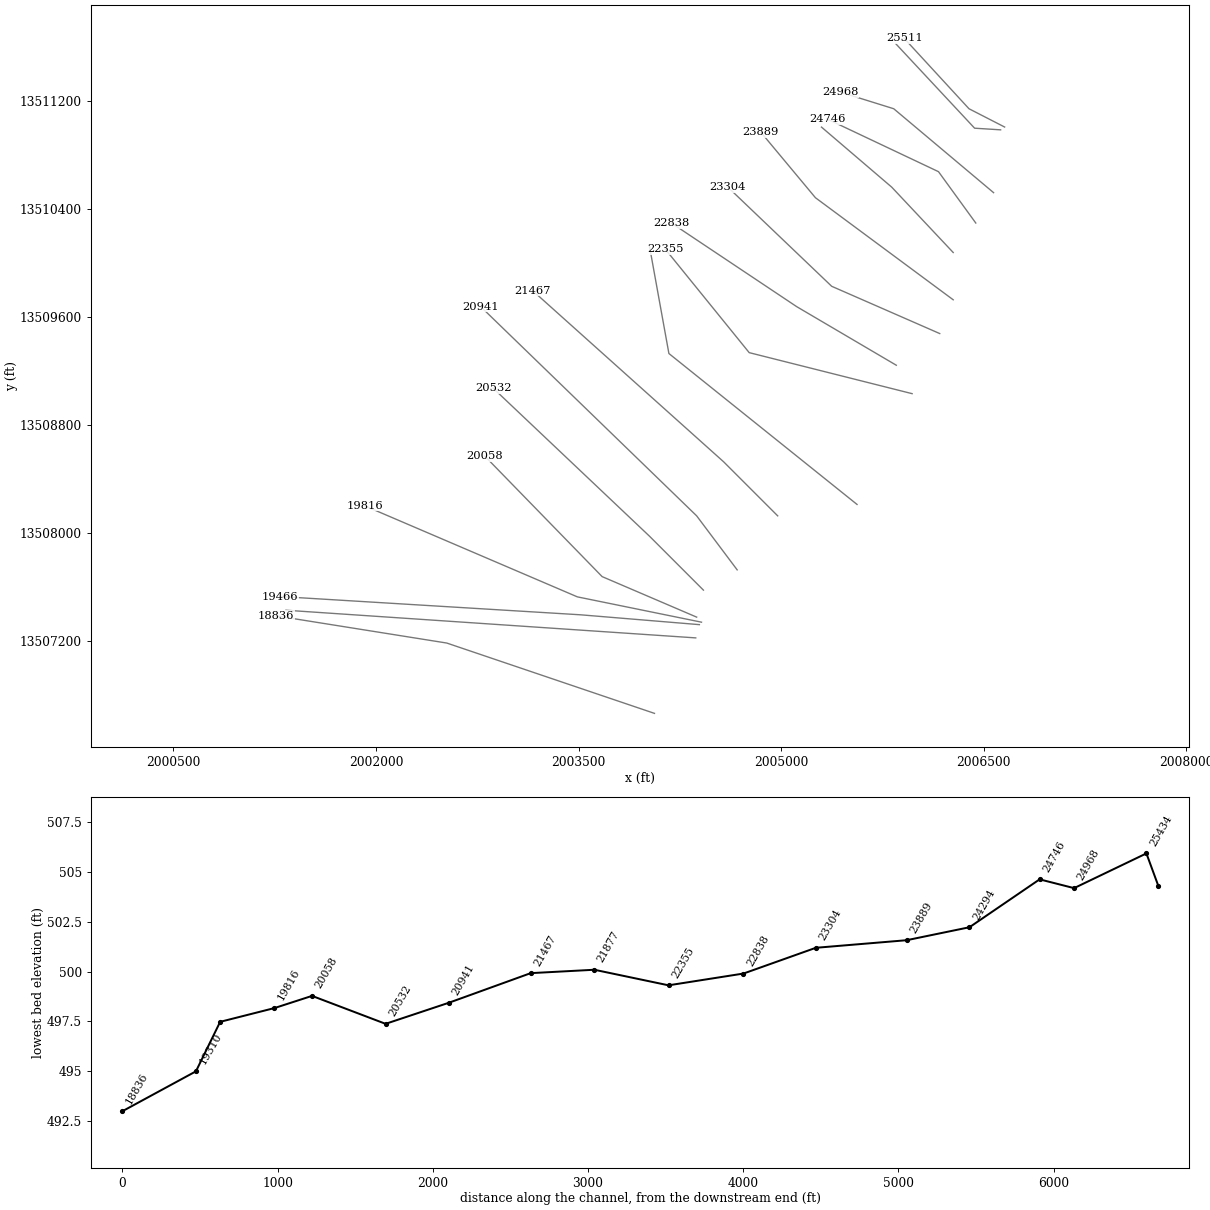
HEC-RAS study Cat Creek.prj: Cat Creek Base Level Engineering

--- Cat Creek.g01 (geometry) --- (continued)

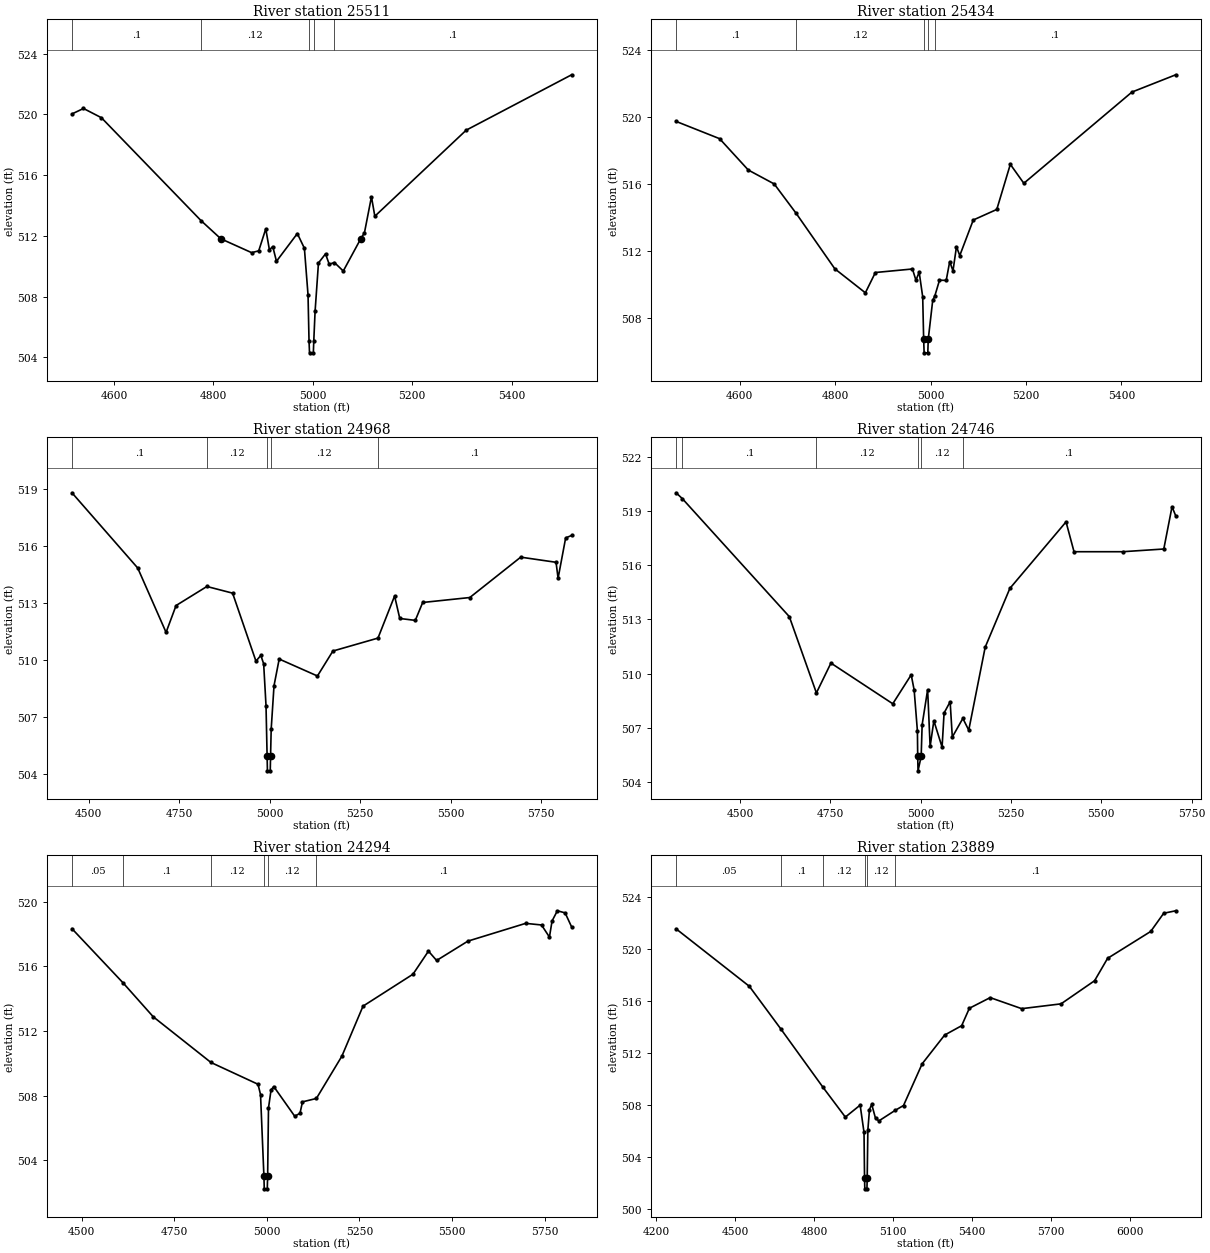
Type RM Length L Ch R = 1 ,25511   ,77,77,77
BEGIN DESCRIPTION:
Cat Creek 31.0
END DESCRIPTION:
XS GIS Cut Line= 3
      2006655.62     13511004.42      2006391.69     13511139.85
      2005911.88     13511661.23
#Sta/Elev= 30
  4515.4  520.03  4538.6  520.39  4574.7  519.78  4775.1     513 4814.91511.8041
  4876.9  510.89  4891.1  511.01  4905.3  512.46  4912.6  511.08  4919.4  511.29
  4926.8  510.32  4968.8  512.15    4983  511.18  4990.3  508.11  4992.3  505.09
  4993.3  504.29    5001  504.29  5001.9  505.09  5004.5  507.02  5011.3  510.21
  5025.5  510.81  5032.9  510.13  5043.4  510.24  5061.2  509.68 5096.34511.8038
  5103.8   512.2  5117.9  514.57  5124.7  513.29  5308.5  518.96  5520.6  522.61
#Mann= 5 ,-1 , 0
  4515.4      .1       0  4775.1     .12       0  4992.3     .07       0
  5001.9     .12       0  5043.4      .1       0
Bank Sta=4814.91,5096.34
XS Rating Curve= 0 ,0
Exp/Cntr=0.3,0.1

Type RM Length L Ch R = 1 ,25434   ,466,466,466
BEGIN DESCRIPTION:
Mapping XS db1dbed6
END DESCRIPTION:
XS GIS Cut Line= 3
      2006626.07      13510983.6      2006433.35     13510995.76
      2005850.38     13511620.37
#Sta/Elev= 30
  4466.6  519.72  4557.8  518.69    4618  516.82  4672.3  515.99  4718.5  514.23
  4799.4  510.93  4863.4   509.5  4884.4  510.71  4962.1  510.92  4969.4  510.25
  4976.2  510.73  4983.6  509.26  4985.6  506.72  4986.6  505.92  4994.3  505.92
  4995.2  506.72  5004.6  509.05    5009  509.31  5018.8  510.25  5032.9  510.24
  5040.2  511.36  5047.1  510.81  5054.4  512.25  5061.3  511.72  5089.6  513.84
  5138.9  514.47  5167.3  517.16  5195.6  516.03  5422.3  521.47  5514.1   522.5
#Mann= 5 ,-1 , 0
  4466.6      .1       0  4718.5     .12       0  4985.6     .07       0
  4995.2     .12       0    5009      .1       0
Bank Sta=4985.6,4995.2
XS Rating Curve= 0 ,0
Exp/Cntr=0.3,0.1

Type RM Length L Ch R = 1 ,24968   ,222,222,222
BEGIN DESCRIPTION:
Cat Creek 30.0
END DESCRIPTION:
XS GIS Cut Line= 3
      2006573.99     13510518.32      2005834.39     13511139.85
      2005439.29     13511262.89
#Sta/Elev= 30
  4453.9  518.78  4635.5  514.83  4713.8  511.45  4741.4  512.86  4826.5  513.86
  4897.5  513.51    4962  509.94  4975.5  510.24  4983.3   509.8  4989.8  507.61
  4992.8  504.98  4993.7  504.18  5001.5  504.18  5002.4  504.98  5004.1  506.37
  5011.9  508.65  5026.2  510.05  5131.8  509.16  5174.5  510.47    5299  511.15
  5344.9  513.36  5359.2  512.18  5402.1  512.08  5422.5  513.02  5552.6  513.28
  5693.2   515.4  5790.8  515.13  5796.4  514.29  5817.3  516.41  5833.8  516.54
#Mann= 5 ,-1 , 0
  4453.9      .1       0  4826.5     .12       0  4992.8     .07       0
  5002.4     .12       0    5299      .1       0
Bank Sta=4992.8,5002.4
XS Rating Curve= 0 ,0
Exp/Cntr=0.3,0.1

Type RM Length L Ch R = 1 ,24746   ,452,452,452
BEGIN DESCRIPTION:
Mapping XS 22e95dbf
END DESCRIPTION:
XS GIS Cut Line= 3
      2006442.02     13510293.52      2006165.99     13510673.71
      2005340.47     13511064.34
#Sta/Elev= 30
  4322.9     520    4340  519.68  4636.3  513.15  4711.3  508.93  4751.5  510.58
  4922.7  508.33  4973.7  509.93  4981.9  509.09  4990.9  506.82  4991.7  505.42
  4992.6  504.62  5001.3  505.42    5004  507.17  5019.2  509.11  5026.1  505.97
  5036.4  507.39  5059.2  505.93  5064.7  507.82  5081.5  508.44  5087.5  506.49
  5116.7  507.52    5133  506.87  5178.5  511.46  5246.8  514.71  5402.3  518.39
  5424.4  516.74  5559.1  516.74  5672.9  516.89  5695.7  519.23    5706  518.72
#Mann= 6 ,-1 , 0
  4322.9     .05       0    4340      .1       0  4711.3     .12       0
  4991.7     .07       0  5001.3     .12       0  5116.7      .1       0
Bank Sta=4991.7,5001.3
XS Rating Curve= 0 ,0
Exp/Cntr=0.3,0.1

Type RM Length L Ch R = 1 ,24294   ,405,405,405
BEGIN DESCRIPTION:
Cat Creek 29.0
END DESCRIPTION:
XS GIS Cut Line= 3
      2006274.97     13510075.04      2005819.64     13510559.13
      2005299.44      13511003.9
#Sta/Elev= 30
  4473.9  518.34  4611.6  514.99  4693.4  512.88  4849.2  510.05  4976.2   508.7
    4983  508.06  4992.1  503.02  4993.1  502.22  5001.2  502.22  5002.2  503.02
  5004.5  507.23  5011.4  508.35  5018.7  508.56  5075.3  506.72  5089.5   506.9
  5096.3  507.61  5133.8  507.82  5202.6  510.44  5259.7  513.54  5394.6  515.52
  5436.4  516.95  5458.4  516.37  5542.9  517.57  5698.8  518.67  5741.6  518.57
    5763  517.82  5770.1  518.82  5784.4  519.45  5805.3  519.32  5822.9  518.45
#Mann= 6 ,-1 , 0
  4473.9     .05       0  4611.6      .1       0  4849.2     .12       0
  4992.1     .07       0  5002.2     .12       0  5133.8      .1       0
Bank Sta=4992.1,5002.2
XS Rating Curve= 0 ,0
Exp/Cntr=0.3,0.1

Type RM Length L Ch R = 1 ,23889   ,585,585,585
BEGIN DESCRIPTION:
Cat Creek 28.0
END DESCRIPTION:
XS GIS Cut Line= 3
      2006274.98     13509725.01      2005254.53       13510481.
      2004850.88     13510965.38
#Sta/Elev= 30
  4275.3  521.57  4553.9  517.15  4673.3  513.88  4834.1  509.38  4919.1  507.09
  4975.4  508.01  4990.1  505.91  4992.1  502.37  4993.1  501.57  5001.2  501.57
  5002.2  502.37  5004.7   506.1  5010.9  507.67  5019.3  508.07  5033.9  506.99
  5046.9   506.8  5108.9  507.61  5140.3  507.98  5211.3  511.19  5296.8   513.4
  5361.5  514.12  5390.8  515.46    5470  516.28  5589.8  515.43  5739.5   515.8
  5867.1  517.58  5916.5   519.3  6080.6  521.37    6130  522.77  6175.8  522.96
#Mann= 6 ,-1 , 0
  4275.3     .05       0  4673.3      .1       0  4834.1     .12       0
  4992.1     .07       0  5002.2     .12       0  5108.9      .1       0
Bank Sta=4992.1,5002.2
XS Rating Curve= 0 ,0
Exp/Cntr=0.3,0.1

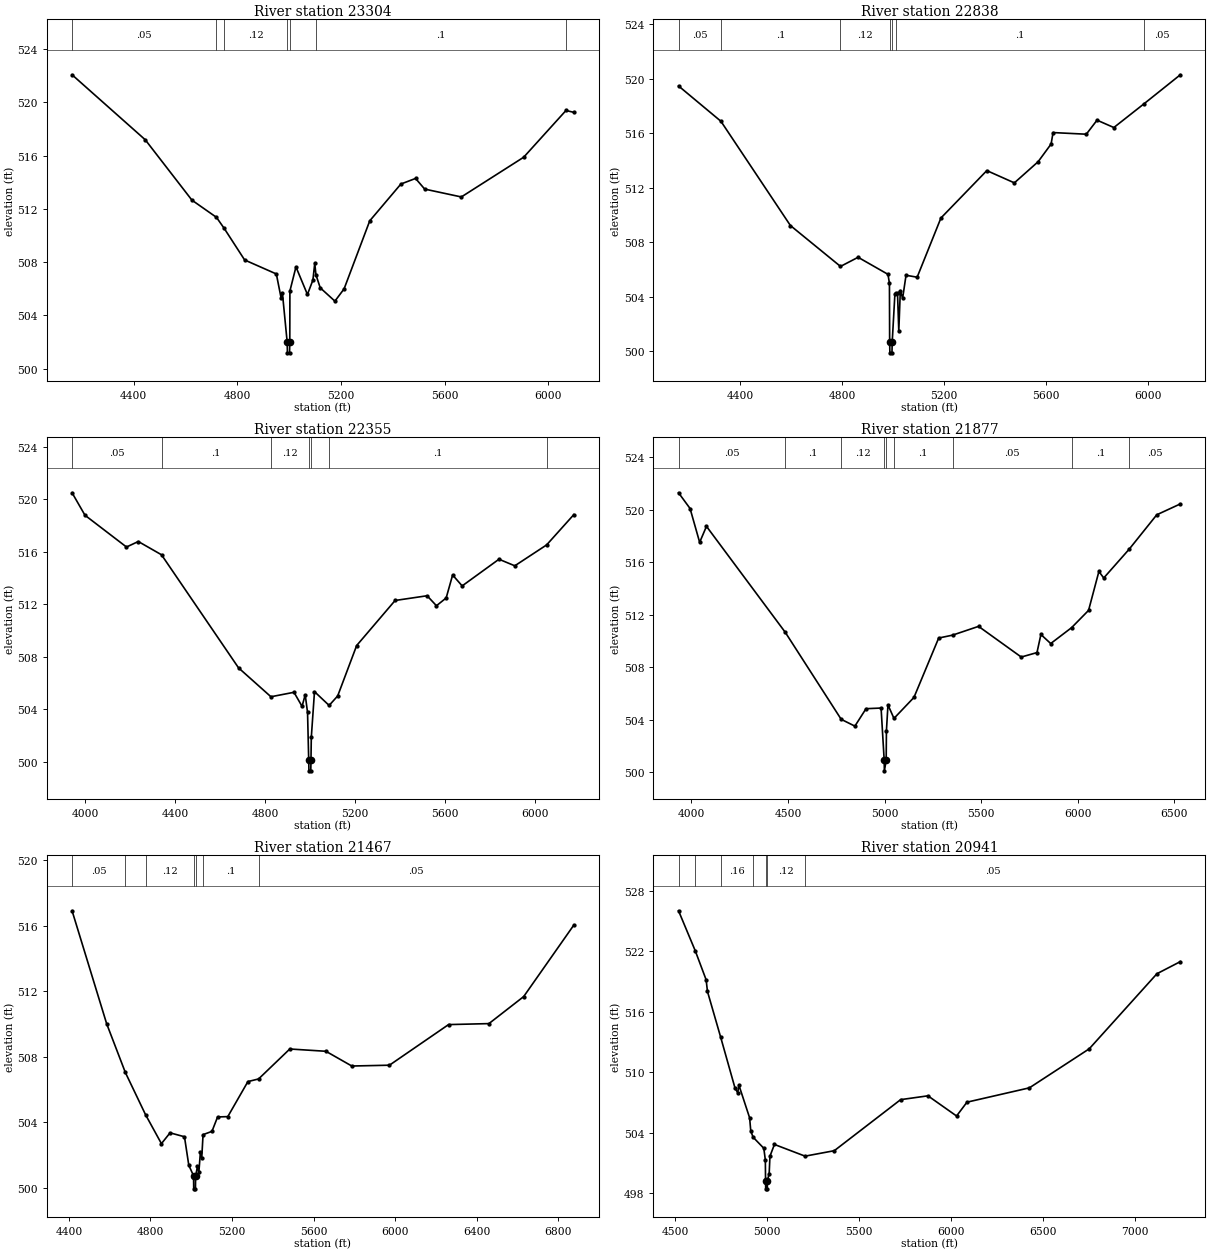
Type RM Length L Ch R = 1 ,23304   ,466,466,466
BEGIN DESCRIPTION:
Cat Creek 27.0
END DESCRIPTION:
XS GIS Cut Line= 3
      2006175.01     13509474.99        2005375.       13509825.
      2004605.65     13510559.79
#Sta/Elev= 30
  4161.9  522.06  4444.5  517.18  4624.6  512.65  4719.3  511.36  4749.2  510.53
  4828.1  508.16  4950.5  507.11  4968.5  505.34  4973.9  505.68  4992.3  501.99
  4993.2  501.19  5001.4  501.19  5002.4  501.99  5002.8  505.83  5026.2  507.64
  5070.5  505.57  5091.6  506.65  5098.8  507.92  5103.3  507.05  5119.9  506.07
  5176.5  505.07    5212  505.99  5311.1   511.1  5431.3  513.86  5487.9  514.28
  5523.1  513.48  5664.6  512.89  5905.2  515.87  6068.6  519.38    6099  519.24
#Mann= 7 ,-1 , 0
  4161.9     .05       0  4719.3      .1       0  4749.2     .12       0
  4992.3     .07       0  5002.4     .12       0  5103.3      .1       0
  6068.6     .05       0
Bank Sta=4992.3,5002.4
XS Rating Curve= 0 ,0
Exp/Cntr=0.3,0.1

Type RM Length L Ch R = 1 ,22838   ,483,483,483
BEGIN DESCRIPTION:
Cat Creek 26.0
END DESCRIPTION:
XS GIS Cut Line= 3
      2005853.51     13509240.32      2005115.64     13509674.36
      2004189.54     13510292.49
#Sta/Elev= 30
  4158.7  519.48    4325  516.89  4597.8  509.24  4794.4  506.24  4863.5  506.91
  4980.7  505.66  4986.5     505  4987.3   500.7  4988.2   499.9  4996.4   499.9
  4997.4   500.7  5007.9  504.21  5012.7  504.26  5018.2  504.26  5023.2  501.48
  5029.2  504.47  5038.2   503.9  5051.6  505.59  5095.3  505.45  5188.5  509.79
  5368.7  513.27  5476.8  512.37    5570  513.92    5621  515.22  5628.7  516.06
  5759.2  515.94  5801.3  516.97  5867.3  516.43  5985.6  518.17  6128.2   520.3
#Mann= 7 ,-1 , 0
  4158.7     .05       0    4325      .1       0  4794.4     .12       0
  4987.3     .07       0  4997.4     .12       0  5012.7      .1       0
  5985.6     .05       0
Bank Sta=4987.3,4997.4
XS Rating Curve= 0 ,0
Exp/Cntr=0.3,0.1

Type RM Length L Ch R = 1 ,22355   ,478,478,478
BEGIN DESCRIPTION:
Cat Creek 25.0
END DESCRIPTION:
XS GIS Cut Line= 3
      2005970.65     13509029.84      2004764.08     13509333.65
      2004142.02     13510100.93
#Sta/Elev= 30
  3940.3  520.48  3997.7  518.77  4182.4  516.35  4234.9  516.77  4338.1  515.76
  4680.8  507.15  4824.9  504.95  4927.4  505.29  4963.3  504.22  4977.3   505.1
  4987.7  503.76  4992.9  500.11  4993.9  499.31  5002.1  499.31    5003  500.11
  5004.4  501.85  5018.6  505.34  5083.7  504.29  5121.7  505.01  5206.2  508.85
  5377.2  512.28  5519.5  512.64  5561.1  511.88  5604.3  512.47    5633  514.22
  5675.5  513.39  5839.2  515.42  5909.6  514.92  6051.1  516.51  6172.3  518.82
#Mann= 7 ,-1 , 0
  3940.3     .05       0  4338.1      .1       0  4824.9     .12       0
  4992.9     .07       0    5003     .12       0  5083.7      .1       0
  6051.1     .05       0
Bank Sta=4992.9,5003
XS Rating Curve= 0 ,0
Exp/Cntr=0.3,0.1

Type RM Length L Ch R = 1 ,21877   ,410,410,410
BEGIN DESCRIPTION:
Cat Creek 24.0
END DESCRIPTION:
XS GIS Cut Line= 3
      2005562.71      13508209.5      2004169.46     13509327.14
      2004024.99     13510125.04
#Sta/Elev= 30
  3933.5   521.3  3993.2   520.1  4042.8  517.52  4078.1  518.74  4486.2  510.65
  4775.3  504.02  4846.2   503.5  4903.8  504.83  4981.8  504.88  4997.9  500.89
  4998.8  500.09  5008.2  500.89  5009.4  503.14  5017.4  505.12  5048.5  504.09
  5151.9  505.69  5279.9  510.22  5351.5  510.44  5486.3  511.11  5707.2  508.77
  5788.6  509.11  5808.9  510.49  5859.7   509.8  5967.6  511.01  6055.6  512.33
  6109.1   515.3  6134.1   514.8    6266     517  6408.5  519.62  6530.5  520.45
#Mann= 9 ,-1 , 0
  3933.5     .05       0  4486.2      .1       0  4775.3     .12       0
  4997.9     .07       0  5008.2     .12       0  5048.5      .1       0
  5351.5     .05       0  5967.6      .1       0    6266     .05       0
Bank Sta=4997.9,5008.2
XS Rating Curve= 0 ,0
Exp/Cntr=0.3,0.1

Type RM Length L Ch R = 1 ,21467   ,526,526,526
BEGIN DESCRIPTION:
Cat Creek 23.0
END DESCRIPTION:
XS GIS Cut Line= 3
      2004975.03     13508124.97        2004575.       13508525.
       2003162.5     13509790.78
#Sta/Elev= 30
  4415.2   516.9    4585     510  4676.5  507.03  4776.1  504.44  4853.7  502.68
  4896.1  503.34  4966.8   503.1    4988  501.36  5011.3  500.72  5012.2  499.92
  5020.6  499.92  5021.6  500.72  5030.7  501.29  5037.4  500.93  5044.9  502.15
  5051.6  501.82    5058  503.23  5101.7  503.43  5129.3  504.31  5179.4  504.33
  5278.1  506.47  5330.4  506.63  5483.7  508.46  5660.9  508.32  5787.9  507.42
  5972.6  507.47  6262.7  509.95  6460.8  510.01  6631.3  511.66  6877.6  516.03
#Mann= 7 ,-1 , 0
  4415.2     .05       0  4676.5      .1       0  4776.1     .12       0
  5011.3     .07       0  5021.6     .12       0    5058      .1       0
  5330.4     .05       0
Bank Sta=5011.3,5021.6
XS Rating Curve= 0 ,0
Exp/Cntr=0.3,0.1

Type RM Length L Ch R = 1 ,20941   ,409,409,409
BEGIN DESCRIPTION:
Cat Creek 22.0
END DESCRIPTION:
XS GIS Cut Line= 3
      2004674.99     13507725.02        2004375.       13508125.
      2002775.03     13509674.97
#Sta/Elev= 30
    4518     526  4609.2  522.02    4668  519.16  4675.3     518  4746.4  513.51
  4825.3  508.41  4839.9  507.96  4846.1  508.72  4904.4  505.48  4910.7  504.16
  4923.7  503.55  4981.5  502.46  4989.9   501.3    4991  499.24  4991.9  498.44
  5000.3  498.44  5001.3  499.24  5010.7  499.96  5014.9  501.67  5039.2  502.84
  5205.9  501.68  5364.6  502.22  5725.2  507.28  5873.7  507.66  6029.3  505.66
  6085.9  507.03  6425.2  508.45  6750.6  512.32  7118.4  519.76  7245.6  520.96
#Mann= 7 ,-1 , 0
    4518     .05       0  4609.2      .1       0  4746.4     .16       0
  4923.7     .12       0    4991     .07       0  5001.3     .12       0
  5205.9     .05       0
Bank Sta=4991,5001.3
XS Rating Curve= 0 ,0
Exp/Cntr=0.3,0.1

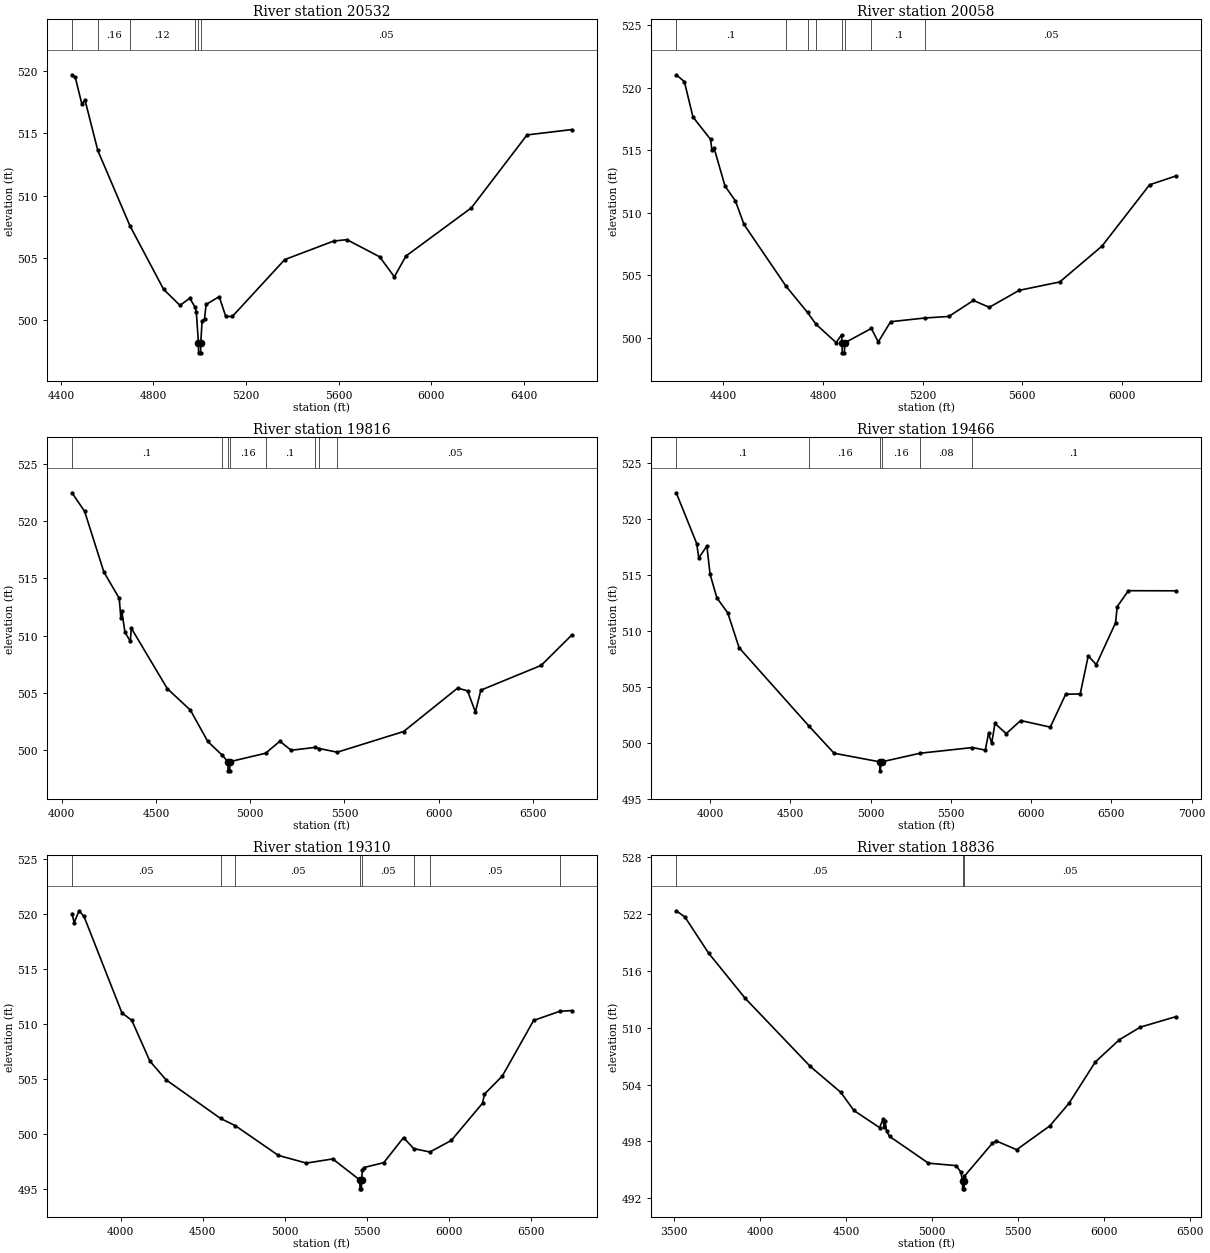
Type RM Length L Ch R = 1 ,20532   ,474,474,474
BEGIN DESCRIPTION:
Cat Creek 21.0
END DESCRIPTION:
XS GIS Cut Line= 3
      2004425.01     13507574.99        2004025.       13507975.
      2002867.54     13509070.96
#Sta/Elev= 30
  4447.9  519.71  4462.1   519.5  4490.3  517.39  4504.5  517.66  4559.5  513.63
  4698.4  507.58  4843.9  502.48  4914.6  501.19    4957  501.77    4979  501.07
  4985.3  500.65  4994.3  498.18  4995.2  497.38  5003.7  497.38  5004.6  498.18
  5010.1  499.95  5020.7   500.1  5027.6  501.27  5084.2  501.89  5112.5   500.3
  5140.8   500.3  5367.4  504.87  5579.3  506.36    5636  506.47  5777.6  505.09
  5841.1  503.48  5890.8  505.15  6173.6  509.02  6414.3  514.88  6607.6  515.31
#Mann= 6 ,-1 , 0
  4447.9      .1       0  4559.5     .16       0  4698.4     .12       0
    4979     .05       0  4994.3    .035       0  5004.6     .05       0
Bank Sta=4994.3,5004.6
XS Rating Curve= 0 ,0
Exp/Cntr=0.3,0.1

Type RM Length L Ch R = 1 ,20058   ,242,242,242
BEGIN DESCRIPTION:
Cat Creek 20.0
END DESCRIPTION:
XS GIS Cut Line= 3
      2004375.01     13507374.99        2003675.       13507675.
       2002806.6     13508566.73
#Sta/Elev= 30
  4211.2  521.02  4243.9  520.47  4278.3  517.65    4349  515.85  4354.5  514.99
  4363.5  515.13    4407  512.12  4448.8  510.93  4483.2  509.05  4652.3   504.1
  4738.2  502.01  4772.1  501.07  4853.1   499.6  4874.9  500.22  4876.9  499.58
  4877.8  498.78  4886.5  498.78  4887.4  499.58  4994.5  500.73  5022.3  499.65
  5071.7  501.27  5211.1  501.57  5305.2  501.69  5404.2  502.97  5467.8  502.42
  5587.9  503.78  5750.7  504.45  5920.5  507.32  6111.3  512.22  6217.5  512.93
#Mann= 8 ,-1 , 0
  4211.2      .1       0  4652.3     .16       0  4738.2      .1       0
  4772.1     .16       0  4876.9     .07       0  4887.4     .16       0
  4994.5      .1       0  5211.1     .05       0
Bank Sta=4876.9,4887.4
XS Rating Curve= 0 ,0
Exp/Cntr=0.3,0.1

Type RM Length L Ch R = 1 ,19816   ,350,350,350
BEGIN DESCRIPTION:
Cat Creek 19.0
END DESCRIPTION:
XS GIS Cut Line= 3
      2004410.82     13507337.55      2003491.51     13507525.05
      2001915.95     13508199.55
#Sta/Elev= 30
    4054   522.5  4121.3  520.87  4223.2  515.57  4304.9  513.26  4313.2  511.56
  4318.3  512.14  4335.5  510.28  4363.8  509.51  4368.9  510.65    4560  505.36
  4682.5  503.48  4774.3  500.75  4851.6  499.53  4881.4  498.97  4882.3  498.17
    4891  498.17  4891.9  498.97  5081.5  499.71  5157.2  500.76  5216.9  499.97
    5343  500.22  5367.3  500.12  5461.6   499.8  5813.8  501.61  6100.4  505.41
    6153  505.17  6194.7  503.32  6223.8  505.23    6544   507.4  6706.1  510.05
#Mann= 8 ,-1 , 0
    4054      .1       0  4851.6     .16       0  4881.4     .07       0
  4891.9     .16       0  5081.5      .1       0    5343     .05       0
  5367.3      .1       0  5461.6     .05       0
Bank Sta=4881.4,4891.9
XS Rating Curve= 0 ,0
Exp/Cntr=0.3,0.1

Type RM Length L Ch R = 1 ,19466   ,156,156,156
BEGIN DESCRIPTION:
Cat Creek 18.0
END DESCRIPTION:
XS GIS Cut Line= 3
      2004395.15     13507319.33      2003514.95     13507392.24
      2001289.17     13507527.61
#Sta/Elev= 30
  3789.6   522.3    3917  517.77  3930.2  516.48  3980.4  517.55  4000.5  515.02
  4042.8  512.92  4110.8  511.57  4181.1  508.47  4616.6  501.47  4772.9  499.05
  5058.2  498.28  5059.1  497.48  5068.7  498.28  5307.6  499.05  5634.9  499.56
  5714.7  499.33  5734.7  500.82  5754.8  499.95  5774.8  501.71  5844.9   500.8
  5935.1  501.97  6119.4  501.38  6215.6  504.32  6305.8  504.34  6355.9  507.74
    6406  506.96  6526.2   510.7  6536.2  512.14  6606.3  513.56  6902.7  513.55
#Mann= 6 ,-1 , 0
  3789.6      .1       0  4616.6     .16       0  5058.2     .07       0
  5068.7     .16       0  5307.6     .08       0  5634.9      .1       0
Bank Sta=5058.2,5068.7
XS Rating Curve= 0 ,0
Exp/Cntr=0.3,0.1

Type RM Length L Ch R = 1 ,19310   ,474,474,474
BEGIN DESCRIPTION:
Mapping XS d3e22dfa
END DESCRIPTION:
XS GIS Cut Line= 2
      2004368.27     13507221.23      2001333.57     13507426.09
#Sta/Elev= 30
  3703.6  520.02  3716.9  519.21    3747  520.28    3777  519.76  4007.6     511
  4067.7  510.32  4177.9  506.61  4276.2  504.91  4607.6   501.4  4696.7  500.75
  4959.7  498.04  5130.1  497.34  5290.5  497.72  5455.6   495.8  5456.5     495
  5465.2     495  5466.1   495.8  5471.4  496.75  5480.9  496.94  5601.2  497.38
  5721.4  499.66    5783  498.66  5881.8  498.35  6012.1   499.4  6202.5  502.79
  6213.4   503.6  6322.8  505.26  6513.2  510.31  6671.9  511.14  6745.2  511.21
#Mann= 8 ,-1 , 0
  3703.6     .05       0  4607.6     .08       0  4696.7     .05       0
  5455.6     .04       0  5466.1     .05       0    5783     .08       0
  5881.8     .05       0  6671.9     .08       0
Bank Sta=5455.6,5466.1
XS Rating Curve= 0 ,0
Exp/Cntr=0.3,0.1

Type RM Length L Ch R = 1 ,18836   ,511,511,511
BEGIN DESCRIPTION:
Cat Creek 17.0
END DESCRIPTION:
XS GIS Cut Line= 3
      2004062.66     13506662.22       2002524.5     13507183.04
      2001260.58     13507384.43
#Sta/Elev= 30
  3512.4  522.35  3562.6   521.7    3700  517.89  3913.6   513.1  4291.2  505.92
  4468.7  503.18  4544.6  501.27    4694  499.46  4713.5  500.34  4720.1  499.55
  4725.4  500.19  4734.6  499.08  4751.6  498.54  4977.4  495.71  5138.6  495.45
  5166.2  494.76  5175.7   493.8  5176.6     493  5185.3     493  5186.2   493.8
  5186.5  494.33  5348.5   497.8  5372.5  498.05  5490.2  497.13  5682.6  499.64
    5794  502.02  5947.1  506.39  6087.7  508.75  6209.2  510.07  6416.2  511.18
#Mann= 3 ,-1 , 0
  3512.4     .05       0  5175.7    .035       0  5186.2     .05       0
Bank Sta=5175.7,5186.2
XS Rating Curve= 0 ,0
Exp/Cntr=0.3,0.1