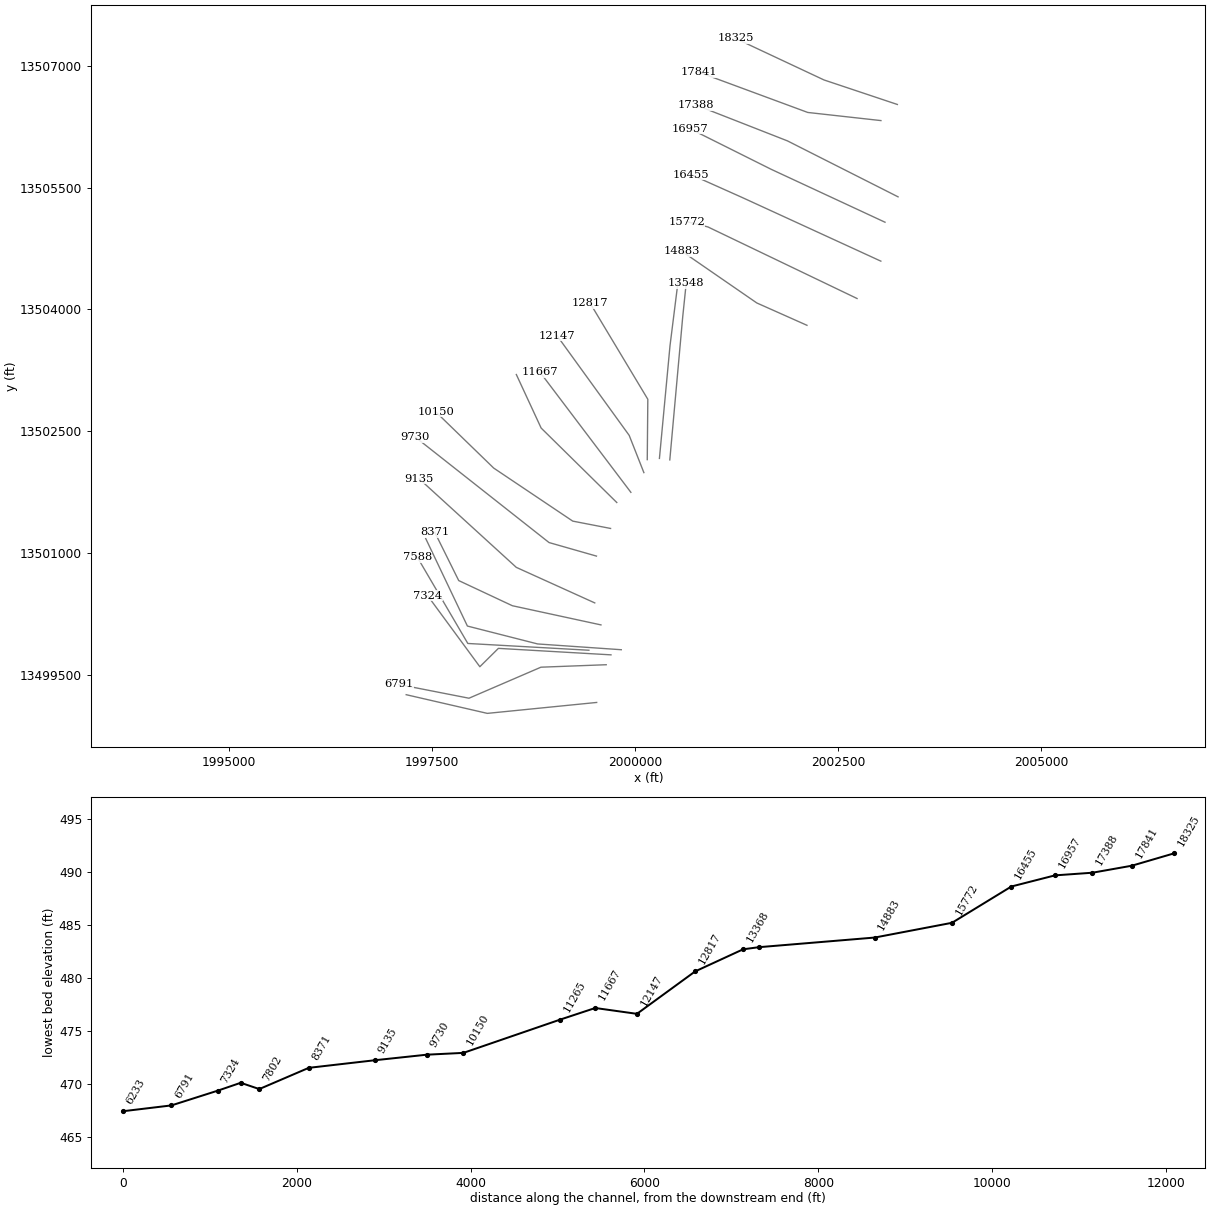
HEC-RAS study Cat Creek.prj: Cat Creek Base Level Engineering

--- Cat Creek.g01 (geometry) --- (continued)

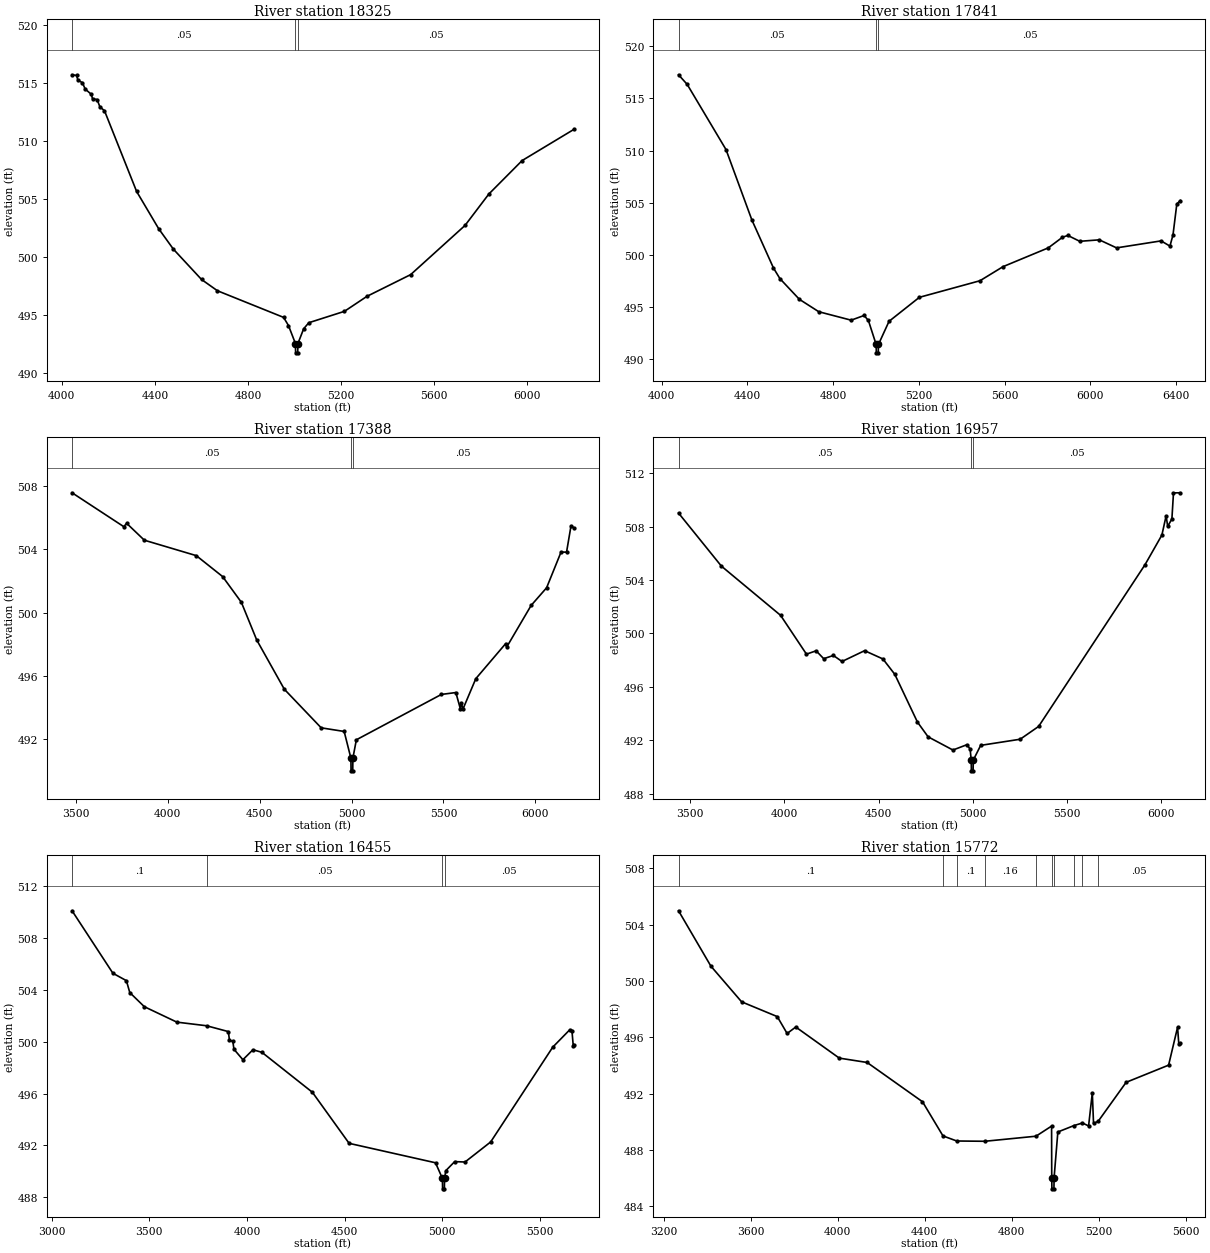
Type RM Length L Ch R = 1 ,18325   ,484,484,484
BEGIN DESCRIPTION:
Cat Creek 16.0
END DESCRIPTION:
XS GIS Cut Line= 3
      2003227.16     13506523.33        2002325.       13506825.
      2001233.73     13507337.54
#Sta/Elev= 30
  4044.1  515.69  4063.7  515.63  4068.9  515.23  4088.6  515.01  4100.5  514.46
  4126.8  514.01  4132.1  513.62  4151.8  513.56  4163.7  512.93  4183.4   512.6
  4321.6  505.65  4416.3  502.45  4479.5  500.69  4600.6  498.08    4669  497.11
  4953.3  494.82  4974.3  494.12  5004.2  492.57    5005  491.77    5014  491.77
  5014.9  492.57  5039.6  493.84  5061.6  494.36  5214.8  495.34  5311.6  496.63
  5499.6   498.5  5733.2  502.73  5835.5  505.43  5978.6  508.31    6201  510.99
#Mann= 3 ,-1 , 0
  4044.1     .05       0  5004.2    .035       0  5014.9     .05       0
Bank Sta=5004.2,5014.9
XS Rating Curve= 0 ,0
Exp/Cntr=0.3,0.1

Type RM Length L Ch R = 1 ,17841   ,453,453,453
BEGIN DESCRIPTION:
Cat Creek 15.0
END DESCRIPTION:
XS GIS Cut Line= 3
      2003025.02       13506325.        2002125.       13506425.
       2000779.6      13506922.5
#Sta/Elev= 30
  4079.3  517.26  4119.6  516.34  4300.7  510.09  4421.4  503.34    4522  498.74
  4552.2  497.72  4642.8  495.74  4733.3  494.55  4884.2  493.74  4944.6  494.19
  4964.7  493.71  5000.8  491.41  5001.7  490.61  5010.7  490.61  5011.5  491.41
  5060.9  493.63  5202.3  495.93    5485  497.52  5592.6  498.87  5803.5  500.67
  5869.8  501.69  5894.8  501.86  5950.3   501.3  6041.5  501.44    6122  500.67
  6329.6  501.34  6370.9  500.84  6385.1  501.91  6402.9  504.87  6419.3  505.21
#Mann= 3 ,-1 , 0
  4079.3     .05       0  5000.8    .035       0  5011.5     .05       0
Bank Sta=5000.8,5011.5
XS Rating Curve= 0 ,0
Exp/Cntr=0.3,0.1

Type RM Length L Ch R = 1 ,17388   ,431,431,431
BEGIN DESCRIPTION:
Cat Creek 14.0
END DESCRIPTION:
XS GIS Cut Line= 3
      2003235.86     13505386.17        2001875.       13506075.
      2000753.23     13506514.64
#Sta/Elev= 30
  3479.4   507.6  3760.6  505.45  3776.6  505.66  3872.6  504.59  4155.3  503.61
  4298.6  502.28  4400.4  500.65  4483.9  498.26  4634.2  495.13  4834.8  492.68
  4959.8  492.45  4996.5  490.75  4997.3  489.95  5006.4  489.95  5007.2  490.75
  5026.1  491.92  5488.8   494.8  5567.5  494.92  5591.9  493.89  5597.3  494.26
  5606.1  493.87    5676   495.8  5838.8  498.03  5844.2  497.81  5977.1  500.45
  6061.2  501.57  6139.9  503.84  6169.7  503.83  6194.1  505.51  6209.5  505.37
#Mann= 3 ,-1 , 0
  3479.4     .05       0  4996.5    .035       0  5007.2     .05       0
Bank Sta=4996.5,5007.2
XS Rating Curve= 0 ,0
Exp/Cntr=0.3,0.1

Type RM Length L Ch R = 1 ,16957   ,502,502,502
BEGIN DESCRIPTION:
Cat Creek 13.0
END DESCRIPTION:
XS GIS Cut Line= 3
      2003075.24     13505073.68        2001675.       13505725.
      2000675.04     13506224.98
#Sta/Elev= 30
    3438  509.03  3665.4  505.05  3979.4  501.36  4116.7  498.45    4168   498.7
  4208.2  498.11  4259.5  498.35  4305.3   497.9  4425.2  498.71  4522.3  498.09
  4585.3  496.94  4705.4  493.36  4762.1  492.25  4893.9  491.26  4968.1  491.66
  4985.1  491.33  4990.9   490.5  4991.7   489.7  5000.9   489.7  5001.7   490.5
    5041  491.61  5250.6  492.07  5348.5  493.03  5913.1  505.16  6002.5  507.38
  6024.9  508.82  6033.3  508.03  6055.6  508.59    6064  510.54  6100.3  510.55
#Mann= 3 ,-1 , 0
    3438     .05       0  4990.9    .035       0  5001.7     .05       0
Bank Sta=4990.9,5001.7
XS Rating Curve= 0 ,0
Exp/Cntr=0.3,0.1

Type RM Length L Ch R = 1 ,16455   ,683,683,683
BEGIN DESCRIPTION:
Cat Creek 12.0
END DESCRIPTION:
XS GIS Cut Line= 3
      2003024.07      13504594.5        2001325.       13505375.
      2000686.37     13505660.72
#Sta/Elev= 30
  3104.7   510.1  3313.9  505.28  3382.8  504.71  3400.3  503.79  3474.8   502.7
  3641.2  501.51  3793.7  501.23    3905  500.78  3910.5  500.12    3928  500.02
  3933.5  499.42  3979.4  498.61  4030.9  499.38  4076.9  499.18  4335.2   496.1
  4523.3  492.16  4965.7  490.66  5001.1  489.45  5001.9  488.65  5011.1  488.65
  5011.9  489.45  5018.3  490.05  5063.9  490.75  5116.9  490.72  5248.3  492.27
    5566  499.58  5653.7  500.93  5664.6   500.8  5671.2  499.64  5674.1  499.78
#Mann= 4 ,-1 , 0
  3104.7      .1       0  3793.7     .05       0  5001.1    .035       0
  5011.9     .05       0
Bank Sta=5001.1,5011.9
XS Rating Curve= 0 ,0
Exp/Cntr=0.3,0.1

Type RM Length L Ch R = 1 ,15772   ,889,889,889
BEGIN DESCRIPTION:
Cat Creek 11.0
END DESCRIPTION:
XS GIS Cut Line= 3
      2002731.36     13504134.43      2000896.61     13505015.59
       2000632.7     13505081.56
#Sta/Elev= 30
  3268.8  504.99  3417.4  501.06  3558.8  498.52  3722.8  497.47  3768.1  496.27
  3807.9  496.73    4008  494.52    4136  494.21  4390.6  491.42  4484.9  488.99
  4548.1  488.63  4677.4  488.61  4912.4  488.97  4984.2  489.69  4984.9  486.03
  4985.7  485.23    4995  485.23  4995.8  486.03    5013  489.27  5087.8  489.73
  5126.2  489.91  5154.4   489.7  5171.5  492.05  5177.1  489.88  5198.5  490.03
    5327   492.8  5522.3  494.02  5563.5  496.71  5569.2  495.53  5576.2  495.57
#Mann= 10 ,-1 , 0
  3268.8      .1       0  4484.9     .16       0  4548.1      .1       0
  4677.4     .16       0  4912.4     .07       0  4984.9     .07       0
  4995.8     .07       0  5087.8      .1       0  5126.2     .07       0
  5198.5     .05       0
Bank Sta=4984.9,4995.8
XS Rating Curve= 0 ,0
Exp/Cntr=0.3,0.1

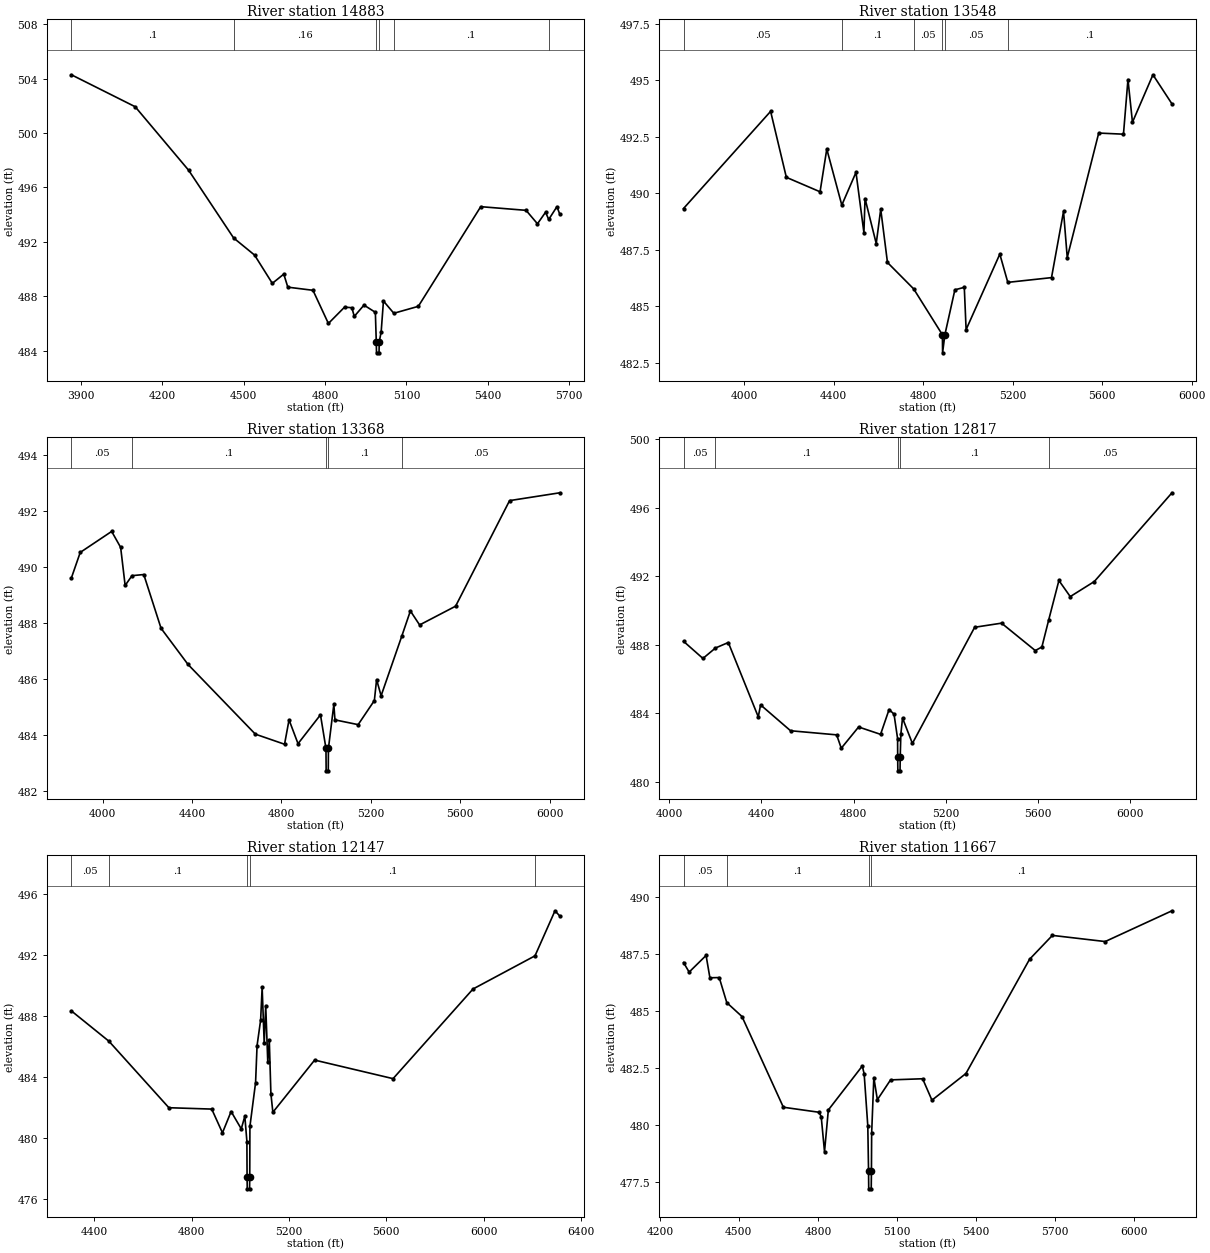
Type RM Length L Ch R = 1 ,14883   ,1335,1335,1335
BEGIN DESCRIPTION:
Cat Creek 10.0
END DESCRIPTION:
XS GIS Cut Line= 3
      2002115.06     13503804.56      2001497.85     13504079.74
       2000573.4     13504717.74
#Sta/Elev= 30
  3866.1  504.29    4101  501.94  4297.8  497.27  4463.5  492.29  4540.7  491.03
  4606.1  488.95  4648.3  489.63  4663.2  488.67  4755.8  488.44  4812.6     486
  4872.1   487.2  4899.1  487.16  4907.9  486.52  4943.7  487.35  4985.6  486.82
    4989  484.64  4989.8  483.84  4999.1  483.84  4999.9  484.64    5007  485.39
  5015.4  487.65  5053.6  486.75  5143.8  487.26  5373.7  494.59  5540.7  494.32
  5582.6  493.33  5612.4  494.18  5624.1  493.65  5654.3  494.59  5665.1  494.02
#Mann= 6 ,-1 , 0
  3866.1      .1       0  4463.5     .16       0    4989     .07       0
  4999.9     .16       0  5053.6      .1       0  5624.1     .08       0
Bank Sta=4989,4999.9
XS Rating Curve= 0 ,0
Exp/Cntr=0.3,0.1

Type RM Length L Ch R = 1 ,13548   ,180,180,180
BEGIN DESCRIPTION:
Cat Creek 9.0
END DESCRIPTION:
XS GIS Cut Line= 3
      2000427.54     13502147.49      2000586.39     13503907.87
       2000629.2     13504320.62
#Sta/Elev= 30
  3729.6  489.32  4118.7  493.62    4189   490.7  4339.6  490.06  4369.7  491.95
  4436.8  489.47  4500.2  490.92  4535.6  488.25  4540.6  489.76  4590.6  487.77
  4610.7  489.29  4640.8  486.93    4758  485.76  4886.3  483.73  4887.1  482.93
  4897.3  483.73    4942  485.72  4984.1  485.83  4992.2  483.96  5142.8   487.3
  5178.5  486.05  5373.8  486.26  5427.5  489.19  5444.1  487.15  5584.7  492.66
  5695.3  492.61  5715.4  495.03  5735.5  493.14    5827  495.24  5912.1  493.95
#Mann= 6 ,-1 , 0
  3729.6     .05       0  4436.8      .1       0    4758     .05       0
  4886.3     .04       0  4897.3     .05       0  5178.5      .1       0
Bank Sta=4886.3,4897.3
XS Rating Curve= 0 ,0
Exp/Cntr=0.3,0.1

Type RM Length L Ch R = 1 ,13368   ,551,551,551
BEGIN DESCRIPTION:
Cat Creek 8.0
END DESCRIPTION:
XS GIS Cut Line= 3
      2000299.93     13502165.67      2000430.14      13503553.7
      2000528.56     13504338.53
#Sta/Elev= 30
  3860.6  489.62  3900.1  490.53  4040.7  491.28  4080.9  490.71    4101  489.35
  4131.7   489.7  4184.4  489.74  4261.7  487.82  4382.2  486.53  4683.5  484.04
  4814.1  483.68  4834.2  484.55  4874.4   483.7  4974.8  484.73  4999.4  483.53
  5000.2  482.73  5009.7  482.73  5010.4  483.53  5034.6   485.1  5039.6  484.55
  5143.3  484.38  5215.9  485.24  5225.9  485.99    5246  485.41    5339  487.55
    5377  488.44  5418.3  487.94  5579.3  488.61  5820.8  492.38  6045.7  492.66
#Mann= 5 ,-1 , 0
  3860.6     .05       0  4131.7      .1       0  4999.4     .07       0
  5010.4      .1       0    5339     .05       0
Bank Sta=4999.4,5010.4
XS Rating Curve= 0 ,0
Exp/Cntr=0.3,0.1

Type RM Length L Ch R = 1 ,12817   ,670,670,670
BEGIN DESCRIPTION:
Mapping XS 37c0bd93
END DESCRIPTION:
XS GIS Cut Line= 3
      2000150.19     13502150.81      2000157.14     13502893.83
      1999449.38     13504073.43
#Sta/Elev= 30
  4062.3  488.21  4146.5  487.21  4200.8  487.82  4256.5  488.14  4386.5   483.8
  4396.5   484.5  4526.5  482.99  4726.5  482.75  4746.5  481.97  4821.7  483.21
    4917  482.78  4953.9  484.23  4975.3  483.96  4990.8  482.53  4991.2  481.45
  4991.9  480.65  5001.4  480.65  5002.2  481.45    5005   482.8  5012.2  483.73
    5055  482.25  5325.1  489.03  5441.7  489.27  5588.1  487.67  5616.7  487.88
  5646.1  489.45  5690.5  491.76  5739.7  490.82  5844.1   491.7    6181  496.88
#Mann= 5 ,-1 , 0
  4062.3     .05       0  4200.8      .1       0  4991.2     .07       0
  5002.2      .1       0  5646.1     .05       0
Bank Sta=4991.2,5002.2
XS Rating Curve= 0 ,0
Exp/Cntr=0.3,0.1

Type RM Length L Ch R = 1 ,12147   ,480,480,480
BEGIN DESCRIPTION:
Mapping XS abcf8bad
END DESCRIPTION:
XS GIS Cut Line= 3
      2000108.52     13501991.06      1999927.97     13502449.39
      1999039.55      13503677.9
#Sta/Elev= 30
  4305.2  488.34  4459.5  486.35  4706.1  481.98  4882.3  481.89  4926.4  480.33
    4962  481.73  5003.7  480.59  5018.4  481.42  5026.9  479.76  5027.6  477.45
  5028.4  476.65  5037.9  476.65  5038.6  477.45  5039.3  480.75  5062.6  483.63
  5068.7  486.06  5083.4  487.74  5089.6  489.88  5098.1  486.21  5104.3  488.69
  5112.8  484.96    5119  486.43  5125.6   482.9  5133.7  481.68  5305.4  485.11
    5628  483.89  5956.7  489.78  6211.7  491.96  6293.9  494.92  6313.9  494.57
#Mann= 5 ,-1 , 0
  4305.2     .05       0  4459.5      .1       0  5027.6     .07       0
  5038.6      .1       0  6211.7     .05       0
Bank Sta=5027.6,5038.6
XS Rating Curve= 0 ,0
Exp/Cntr=0.3,0.1

Type RM Length L Ch R = 1 ,11667   ,402,402,402
BEGIN DESCRIPTION:
Mapping XS 7300d7e0
END DESCRIPTION:
XS GIS Cut Line= 2
       1999948.8     13501748.01      1998830.73     13503227.19
#Sta/Elev= 30
    4290  487.13  4311.3  486.71  4375.6  487.44  4390.1  486.46  4425.5  486.47
  4454.2  485.37  4511.9  484.76    4669  480.78  4804.3  480.56  4812.6  480.37
  4825.2  478.83  4839.7  480.66  4968.7  482.59  4975.7  482.24  4989.5  479.96
  4992.3     478    4993   477.2  5002.5   477.2  5003.3     478  5004.1  479.63
  5012.4  482.08  5025.8  481.11  5075.9  481.98  5197.6  482.03    5233  481.09
    5362  482.26  5603.4  487.27  5690.2  488.32  5890.6  488.05  6144.2   489.4
#Mann= 4 ,-1 , 0
    4290     .05       0  4454.2      .1       0  4992.3     .07       0
  5003.3      .1       0
Bank Sta=4992.3,5003.3
XS Rating Curve= 0 ,0
Exp/Cntr=0.3,0.1

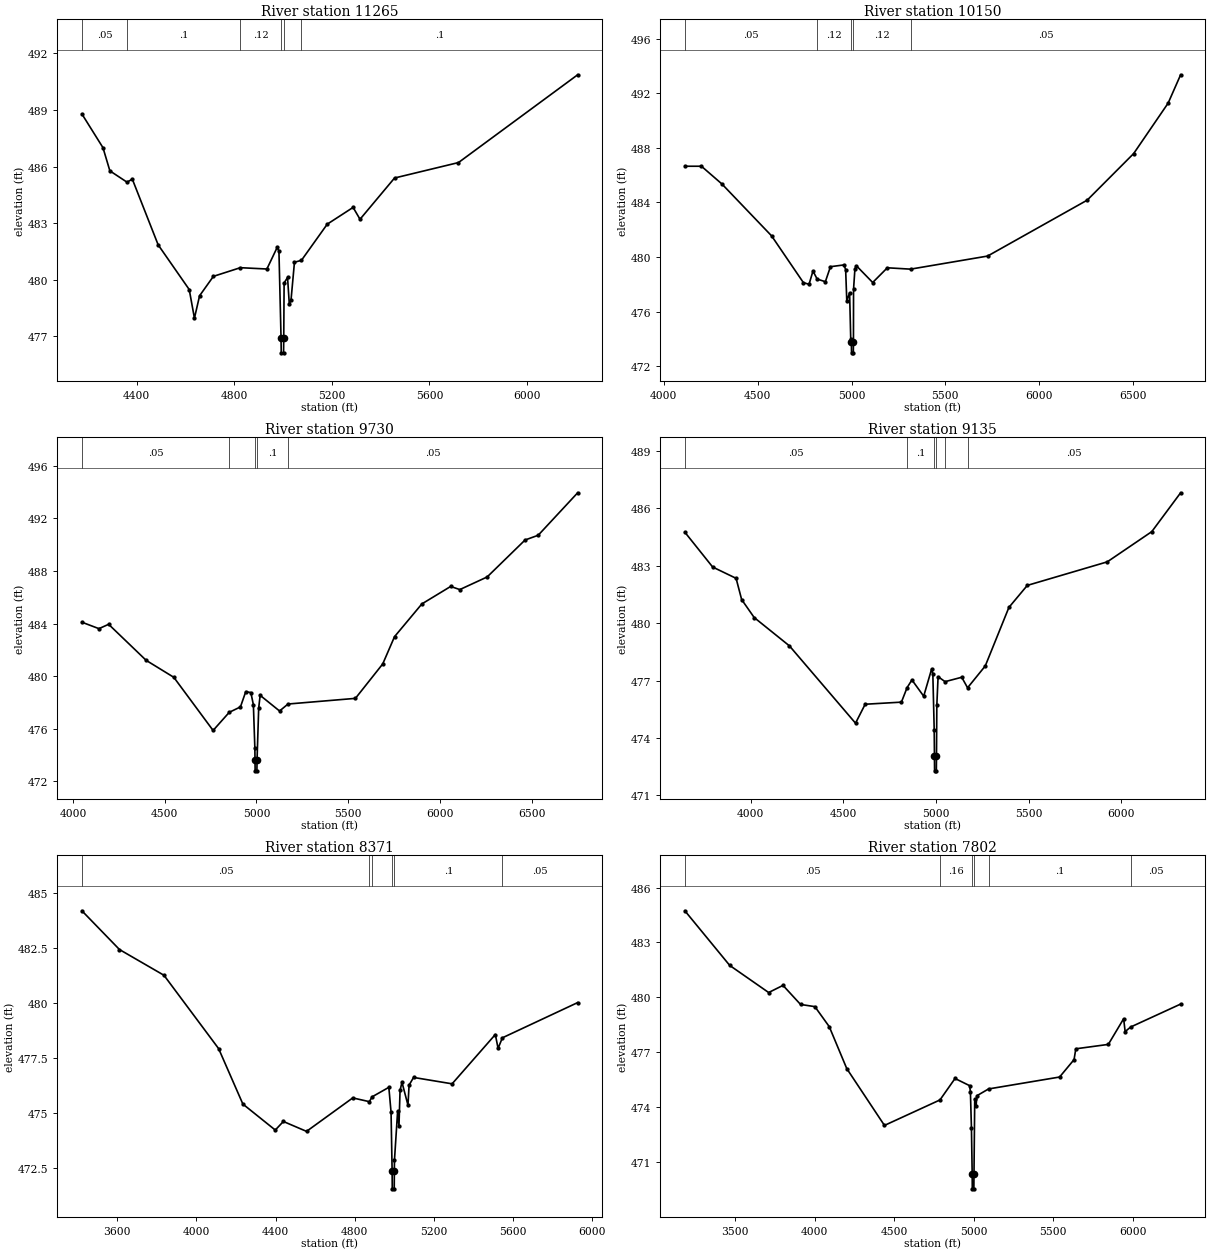
Type RM Length L Ch R = 1 ,11265   ,1115,1115,1115
BEGIN DESCRIPTION:
Mapping XS e4b51846
END DESCRIPTION:
XS GIS Cut Line= 3
      1999775.22     13501622.97      1998844.64     13502539.67
      1998539.55     13503198.39
#Sta/Elev= 30
  4175.5  488.79  4261.9     487  4290.2  485.77  4360.4  485.17  4382.2  485.33
  4488.2  481.84  4615.5  479.47  4636.8  477.95  4657.9  479.14  4714.5  480.17
  4825.1  480.63  4933.8  480.56  4976.1  481.71  4983.2  481.51  4991.8  476.91
  4992.6  476.11  5002.2  476.11  5002.9  476.91  5004.4  479.82  5018.5  480.11
  5025.6  478.71  5032.7  478.91  5046.8  480.92  5075.4  481.02  5181.2  482.94
  5287.2  483.83  5315.5   483.2    5457  485.39  5719.1  486.21  6207.7  490.87
#Mann= 6 ,-1 , 0
  4175.5     .05       0  4360.4      .1       0  4825.1     .12       0
  4991.8     .07       0  5002.9     .12       0  5075.4      .1       0
Bank Sta=4991.8,5002.9
XS Rating Curve= 0 ,0
Exp/Cntr=0.3,0.1

Type RM Length L Ch R = 1 ,10150   ,420,420,420
BEGIN DESCRIPTION:
Mapping XS 717044c2
END DESCRIPTION:
XS GIS Cut Line= 4
      1999698.78     13501303.56      1999233.53     13501393.83
       1998261.3     13502046.61       1997546.6      13502740.5
#Sta/Elev= 30
  4112.2  486.66  4200.6  486.66  4309.6  485.36  4574.4  481.55  4743.8  478.12
  4773.8     478  4794.8  478.97  4817.2  478.38  4860.8  478.19  4887.9  479.29
  4959.9  479.42  4968.8  479.08  4974.9  476.77  4989.9  477.38  4995.9  473.98
  4999.3  473.77  5000.1  472.97  5009.7  472.97  5010.4  473.77  5010.9  477.63
    5018  479.09  5025.9  479.36  5112.9  478.13  5190.9  479.21  5314.6  479.11
    5725  480.07  6255.4  484.17  6503.1  487.59  6686.8  491.29  6753.3  493.37
#Mann= 5 ,-1 , 0
  4112.2     .05       0  4817.2     .12       0  4999.3     .07       0
  5010.4     .12       0  5314.6     .05       0
Bank Sta=4999.3,5010.4
XS Rating Curve= 0 ,0
Exp/Cntr=0.3,0.1

Type RM Length L Ch R = 1 ,9730    ,595,595,595
BEGIN DESCRIPTION:
Mapping XS 6c6aaea4
END DESCRIPTION:
XS GIS Cut Line= 3
      1999525.24     13500963.26      1998941.86     13501129.94
      1997296.01     13502428.56
#Sta/Elev= 30
    4048   484.1    4141  483.61  4193.8  483.94  4398.4   481.2  4549.2  479.91
  4763.4  475.87  4851.5  477.25  4912.5  477.66  4941.4  478.82  4969.2  478.75
    4983  477.83  4991.1  474.53  4991.9   473.6  4992.6   472.8  5002.2   472.8
    5003   473.6  5011.9  477.56  5019.9  478.54  5125.7  477.35    5172  477.88
  5539.4  478.31  5688.4  480.93  5752.6     483  5901.7  485.49  6058.8  486.82
  6108.5  486.58  6257.6  487.54  6464.4  490.35  6535.9  490.71  6751.2  493.94
#Mann= 5 ,-1 , 0
    4048     .05       0  4851.5      .1       0  4991.9     .07       0
    5003      .1       0    5172     .05       0
Bank Sta=4991.9,5003
XS Rating Curve= 0 ,0
Exp/Cntr=0.3,0.1

Type RM Length L Ch R = 1 ,9135    ,764,764,764
BEGIN DESCRIPTION:
Mapping XS 45514d4a
END DESCRIPTION:
XS GIS Cut Line= 3
      1999504.38     13500386.88      1998539.08     13500824.39
      1997344.66     13501914.64
#Sta/Elev= 30
    3644  484.75  3794.2  482.93  3920.7  482.34  3950.7  481.23  4018.5  480.29
  4208.7  478.81  4565.6  474.77  4617.7  475.76  4813.4  475.87  4844.1  476.63
  4870.2  477.03  4933.7  476.18  4976.2  477.59    4983  477.36  4990.4  474.44
  4991.7  473.08  4992.4  472.28    5002  472.28  5002.8  473.08  5004.6  475.71
  5011.4   477.2  5049.1  476.94  5139.1  477.17  5170.6  476.62  5266.1  477.76
  5393.8  480.82  5493.1  481.97  5924.8   483.2  6165.3  484.78    6321  486.81
#Mann= 6 ,-1 , 0
    3644     .05       0  4844.1      .1       0  4991.7     .07       0
  5002.8      .1       0  5049.1      .1       0  5170.6     .05       0
Bank Sta=4991.7,5002.8
XS Rating Curve= 0 ,0
Exp/Cntr=0.3,0.1

Type RM Length L Ch R = 1 ,8371    ,569,569,569
BEGIN DESCRIPTION:
Mapping XS e195b87a
END DESCRIPTION:
XS GIS Cut Line= 4
       1999580.7     13500116.07      1998490.47     13500352.17
      1997830.64     13500661.85      1997536.36     13501255.64
#Sta/Elev= 30
  3420.9  484.19  3610.9  482.43    3836  481.26  4112.3  477.93    4235  475.41
  4398.8  474.23  4439.7  474.62  4556.9  474.17  4790.6  475.69  4874.5  475.52
  4888.6  475.74  4973.1  476.17  4984.3  475.04  4989.7  472.36  4990.4  471.56
  5000.3  471.56    5001  472.36  5001.5  472.86  5017.5  475.08  5024.3   474.4
  5029.8  476.03  5039.5   476.4  5069.9  475.36  5075.4  476.27  5098.2  476.62
    5293  476.33  5511.6  478.57  5525.5  477.94  5547.3  478.42    5928  480.02
#Mann= 6 ,-1 , 0
  3420.9     .05       0  4874.5     .16       0  4888.6      .1       0
  4989.7     .07       0    5001      .1       0  5547.3     .05       0
Bank Sta=4989.7,5001
XS Rating Curve= 0 ,0
Exp/Cntr=0.3,0.1

Type RM Length L Ch R = 1 ,7802    ,214,214,214
BEGIN DESCRIPTION:
Cat Creek 5.0
END DESCRIPTION:
XS GIS Cut Line= 4
      1999830.71      13499810.5      1998801.23     13499881.68
      1997937.41     13500101.96      1997424.42     13501180.03
#Sta/Elev= 30
  3183.3  484.73  3465.3  481.75  3710.3  480.27  3800.5  480.66  3910.7  479.62
    4001   479.5  4091.2  478.41  4201.4  476.12  4438.4  473.02  4787.4  474.41
  4882.1  475.58  4973.6  475.19  4978.8  474.86  4985.3  472.88    4990  470.36
  4990.7  469.56  5000.6  469.56  5001.3  470.36    5006  474.46  5014.5  474.09
  5019.6  474.64    5093  475.01  5539.6  475.66  5630.5  476.61  5641.6   477.2
    5846  477.44  5942.3  478.84  5951.7  478.14  5986.8  478.39  6300.6  479.64
#Mann= 6 ,-1 , 0
  3183.3     .05       0  4787.4     .16       0    4990     .07       0
  5001.3     .16       0    5093      .1       0  5986.8     .05       0
Bank Sta=4990,5001.3
XS Rating Curve= 0 ,0
Exp/Cntr=0.3,0.1

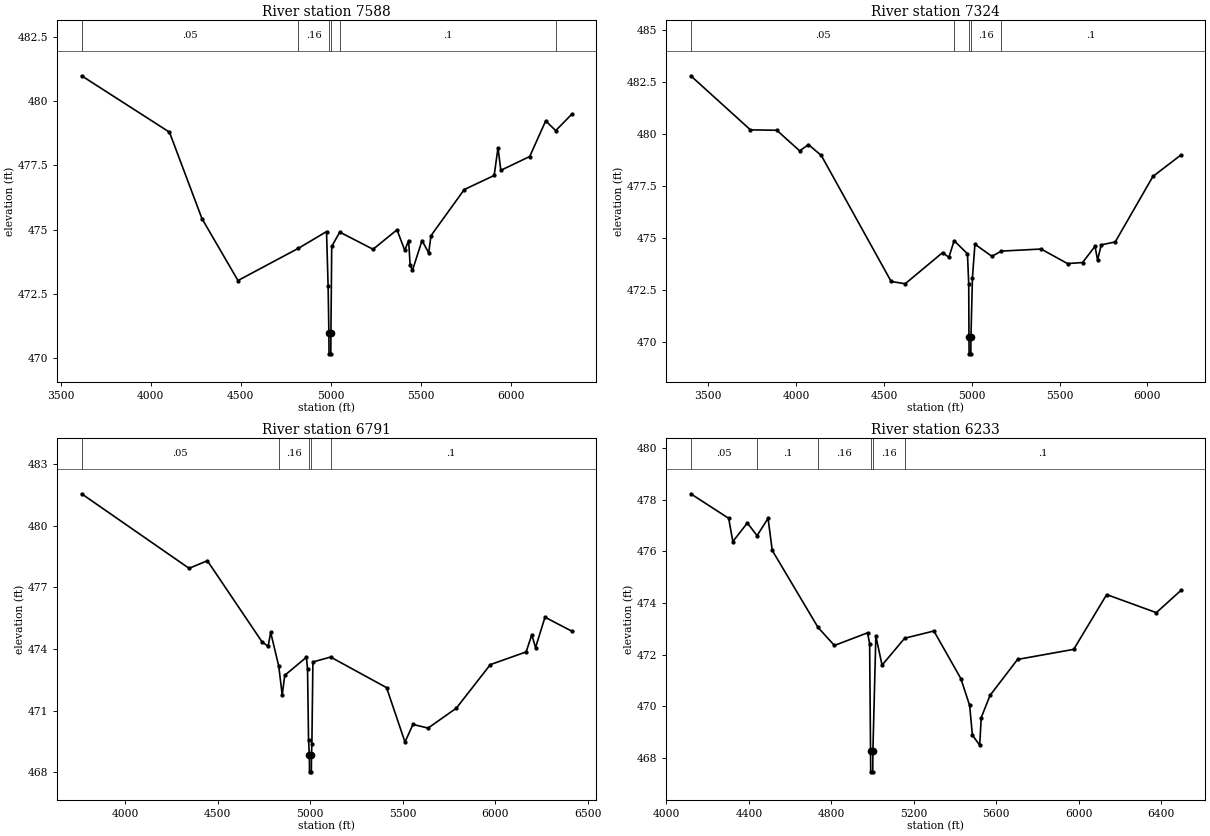
Type RM Length L Ch R = 1 ,7588    ,264,264,264
BEGIN DESCRIPTION:
Mapping XS 0df496c3
END DESCRIPTION:
XS GIS Cut Line= 3
      1999432.24     13499804.21      1997942.62     13499887.55
      1997321.08     13500950.06
#Sta/Elev= 30
  3616.4     481  4104.4   478.8  4284.7  475.43    4485  473.01  4821.2  474.27
    4977  474.92  4985.8  472.79  4990.1  470.95  4990.8  470.15  5000.7  470.15
  5001.4  470.95  5005.8  474.34  5050.5   474.9  5235.5  474.23  5368.5  474.99
  5411.5  474.19    5433  474.57  5441.4  473.61  5454.5  473.41  5507.4  474.57
  5544.5  474.09  5557.2  474.76    5742  476.56  5908.2  477.11  5929.6  478.19
  5945.3  477.31  6105.7  477.85  6194.4  479.24  6250.1  478.86  6339.3   479.5
#Mann= 6 ,-1 , 0
  3616.4     .05       0  4821.2     .16       0  4990.1     .07       0
  5001.4     .16       0  5050.5      .1       0  6250.1     .05       0
Bank Sta=4990.1,5001.4
XS Rating Curve= 0 ,0
Exp/Cntr=0.3,0.1

Type RM Length L Ch R = 1 ,7324    ,533,533,533
BEGIN DESCRIPTION:
Mapping XS b67881d0
END DESCRIPTION:
XS GIS Cut Line= 4
      1999704.19     13499747.35      1998318.81     13499827.21
      1998090.52     13499601.16      1997449.95     13500473.48
#Sta/Elev= 30
  3399.7  482.78  3739.5  480.18  3889.7  480.16  4019.9  479.17    4070  479.47
    4143  478.95  4540.8  472.89  4620.9  472.78  4834.1  474.28  4869.4  474.05
  4899.7  474.85  4975.5  474.22  4982.6  472.77    4984  470.21  4984.7  469.41
  4994.6  469.41  4995.3  470.21  5003.8  473.08  5017.9  474.68  5114.6   474.1
  5169.1  474.35  5394.7  474.45  5545.1  473.75  5630.8   473.8  5701.8  474.58
  5716.4  473.92  5737.3  474.65  5816.8  474.79  6031.5  477.94  6190.9  478.97
#Mann= 5 ,-1 , 0
  3399.7     .05       0  4899.7     .16       0    4984     .07       0
  4995.3     .16       0  5169.1      .1       0
Bank Sta=4984,4995.3
XS Rating Curve= 0 ,0
Exp/Cntr=0.3,0.1

Type RM Length L Ch R = 1 ,6791    ,558,558,558
BEGIN DESCRIPTION:
Mapping XS dd315567
END DESCRIPTION:
XS GIS Cut Line= 4
      1999645.21     13499625.82      1998842.25     13499595.44
      1997956.83     13499213.49      1997093.08     13499382.77
#Sta/Elev= 30
    3765  481.56  4345.6  477.93  4444.3   478.3  4739.8  474.35  4772.5  474.13
  4786.5  474.81  4830.4  473.15  4848.7  471.76  4862.5  472.72  4979.4   473.6
  4985.5  473.03    4991  469.57  4995.5  468.82  4996.2  468.02  5006.2  468.02
  5006.8  468.82    5009  469.36  5014.5  473.37  5110.2  473.61  5412.5  472.12
    5512  469.47  5555.1  470.33  5636.6  470.15  5789.4  471.12  5972.9  473.24
  6166.5  473.86    6197  474.69  6217.4  474.07  6268.4  475.55    6413  474.87
#Mann= 5 ,-1 , 0
    3765     .05       0  4830.4     .16       0  4995.5     .07       0
  5006.8     .16       0  5110.2      .1       0
Bank Sta=4995.5,5006.8
XS Rating Curve= 0 ,0
Exp/Cntr=0.3,0.1

Type RM Length L Ch R = 1 ,6233    ,0,0,0
BEGIN DESCRIPTION:
Mapping XS 65fafe54
END DESCRIPTION:
XS GIS Cut Line= 3
      1999528.02     13499161.41      1998182.53     13499026.86
      1997184.29     13499256.89
#Sta/Elev= 30
  4118.4  478.23  4302.3  477.28  4322.4  476.38  4392.8   477.1  4439.9  476.61
  4493.3  477.28  4513.4  476.04  4735.4  473.06  4814.9  472.36  4975.7  472.85
  4985.7  472.43  4990.1  468.27  4990.8  467.47  5000.8  467.47  5001.5  468.27
  5015.9  472.72    5046   471.6  5155.5  472.64  5297.3  472.92  5427.9  471.08
  5470.6  470.04    5484  468.89  5519.4   468.5  5526.8  469.57  5569.6  470.43
  5703.1  471.82  5975.2  472.21  6135.1  474.33  6375.8  473.63    6495  474.49
#Mann= 6 ,-1 , 0
  4118.4     .05       0  4439.9      .1       0  4735.4     .16       0
  4990.1     .07       0  5001.5     .16       0  5155.5      .1       0
Bank Sta=4990.1,5001.5
XS Rating Curve= 0 ,0
Exp/Cntr=0.3,0.1
LCMann Table=0

Chan Stop Cuts=-1
Use User Specified Reach Order=0
Composite Channel Slope=5