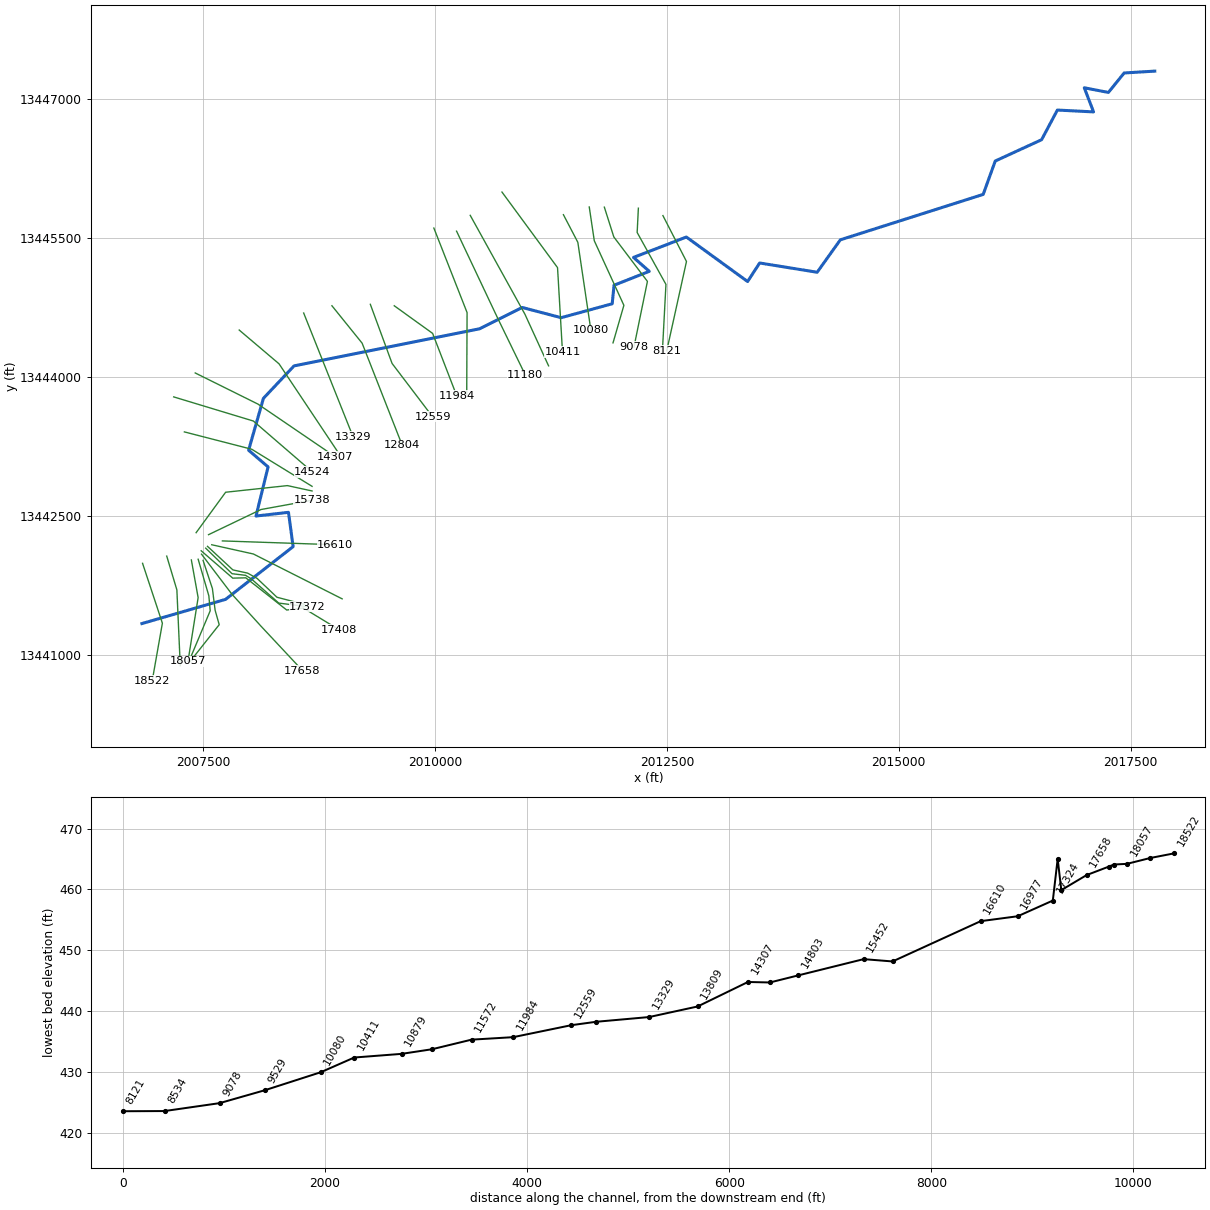
--- Little Calf Creek.prj (project) ---

Proj Title=Little Calf Creek Base Level Engineering
Current Plan=p01
Default Exp/Contr=0.3,0.1
English Units
Geom File=g01
Flow File=f01
Plan File=p01
Y Axis Title=Elevation
X Axis Title(PF)=Main Channel Distance
X Axis Title(XS)=Station
BEGIN DESCRIPTION:
Little Calf Creek
END DESCRIPTION:
DSS Export Rating Curves= 0
DSS Export Rating Curve Sorted= 0
DSS Export Volume Flow Curves= 0
DXF OffsetX= 0
DXF OffsetY= 0
DXF ScaleX= 1
DXF ScaleY= 10

--- Little Calf Creek.p01 (plan) ---

Plan Title=Multiple Run
Short Identifier=Multiple
Geom File=g01
Flow File=f01
Subcritical Flow
K Sum by GR= 0
Std Step Tol= 0.01
Critical Tol= 0.01
Num of Std Step Trials= 20
Max Error Tol= 0.3
Flow Tol Ratio= 0.001
Split Flow NTrial= 30
Split Flow Tol= 0.02
Split Flow Ratio= 0.02
Log Output Level= 0
Friction Slope Method= 1
Unsteady Friction Slope Method= 2
Unsteady Bridges Friction Slope Method= 1
Parabolic Critical Depth
Global Vel Dist=  1 , 1 , 1
Global Log Level= 0
CheckData=True
Encroach Param= -1, 0, 0, 0
BEGIN DESCRIPTION:
Multiple Run
END DESCRIPTION:

--- Little Calf Creek.f01 (steady flow) ---

Flow Title=Multiple
Number of Profiles=7
Profile Names=10-year,25-year,50-year,1pct_min,100-year,1pct_plu,500-year
River Rch & RM= Little Calf Cree,Reach-1,18522
     143     192     232     140     279     556     410
River Rch & RM= Little Calf Cree,Reach-1,17408
     273     382     473     292     582    1161     896
River Rch & RM= Little Calf Cree,Reach-1,13809
     348     491     611     378     755    1506    1172
River Rch & RM= Little Calf Cree,Reach-1,6128
     371     524     652     404     806    1607    1251
Boundary for River Rch & Prof#=Little Calf Cree,Reach-1,1
Up Type=0
Dn Type=3
Dn Slope=0.005
Boundary for River Rch & Prof#=Little Calf Cree,Reach-1,2
Up Type=0
Dn Type=3
Dn Slope=0.005
Boundary for River Rch & Prof#=Little Calf Cree,Reach-1,3
Up Type=0
Dn Type=3
Dn Slope=0.005
Boundary for River Rch & Prof#=Little Calf Cree,Reach-1,4
Up Type=0
Dn Type=3
Dn Slope=0.005
Boundary for River Rch & Prof#=Little Calf Cree,Reach-1,5
Up Type=0
Dn Type=3
Dn Slope=0.005
Boundary for River Rch & Prof#=Little Calf Cree,Reach-1,6
Up Type=0
Dn Type=3
Dn Slope=0.005
Boundary for River Rch & Prof#=Little Calf Cree,Reach-1,7
Up Type=0
Dn Type=3
Dn Slope=0.005

--- Little Calf Creek.g01 (geometry) ---

Geom Title=Existing Conditions
Program Version=5.05

River Reach=Little Calf Cree,Reach-1
Reach XY= 30
       2006840.8     13441344.54      2007742.76     13441605.66
       2008470.8     13442174.54       2008420.8     13442544.54
       2008070.8     13442504.54       2008200.8     13443034.54
       2007990.8     13443214.54       2008150.8     13443774.54
       2008480.8     13444124.54       2010480.8     13444524.54
       2010940.8     13444754.54       2011360.8     13444644.54
       2011910.8     13444794.54       2011930.8     13444994.54
       2012310.8     13445144.54       2012140.8     13445294.54
       2012710.8     13445514.54       2013370.8     13445034.54
       2013500.8     13445234.54       2014120.8     13445134.54
       2014370.8     13445484.54       2015910.8     13445974.54
       2016040.8     13446334.54       2016540.8     13446564.54
       2016710.8     13446884.54       2017100.8     13446864.54
       2017000.8     13447124.54       2017260.8     13447074.54
       2017430.8     13447284.54       2017760.8     13447304.54

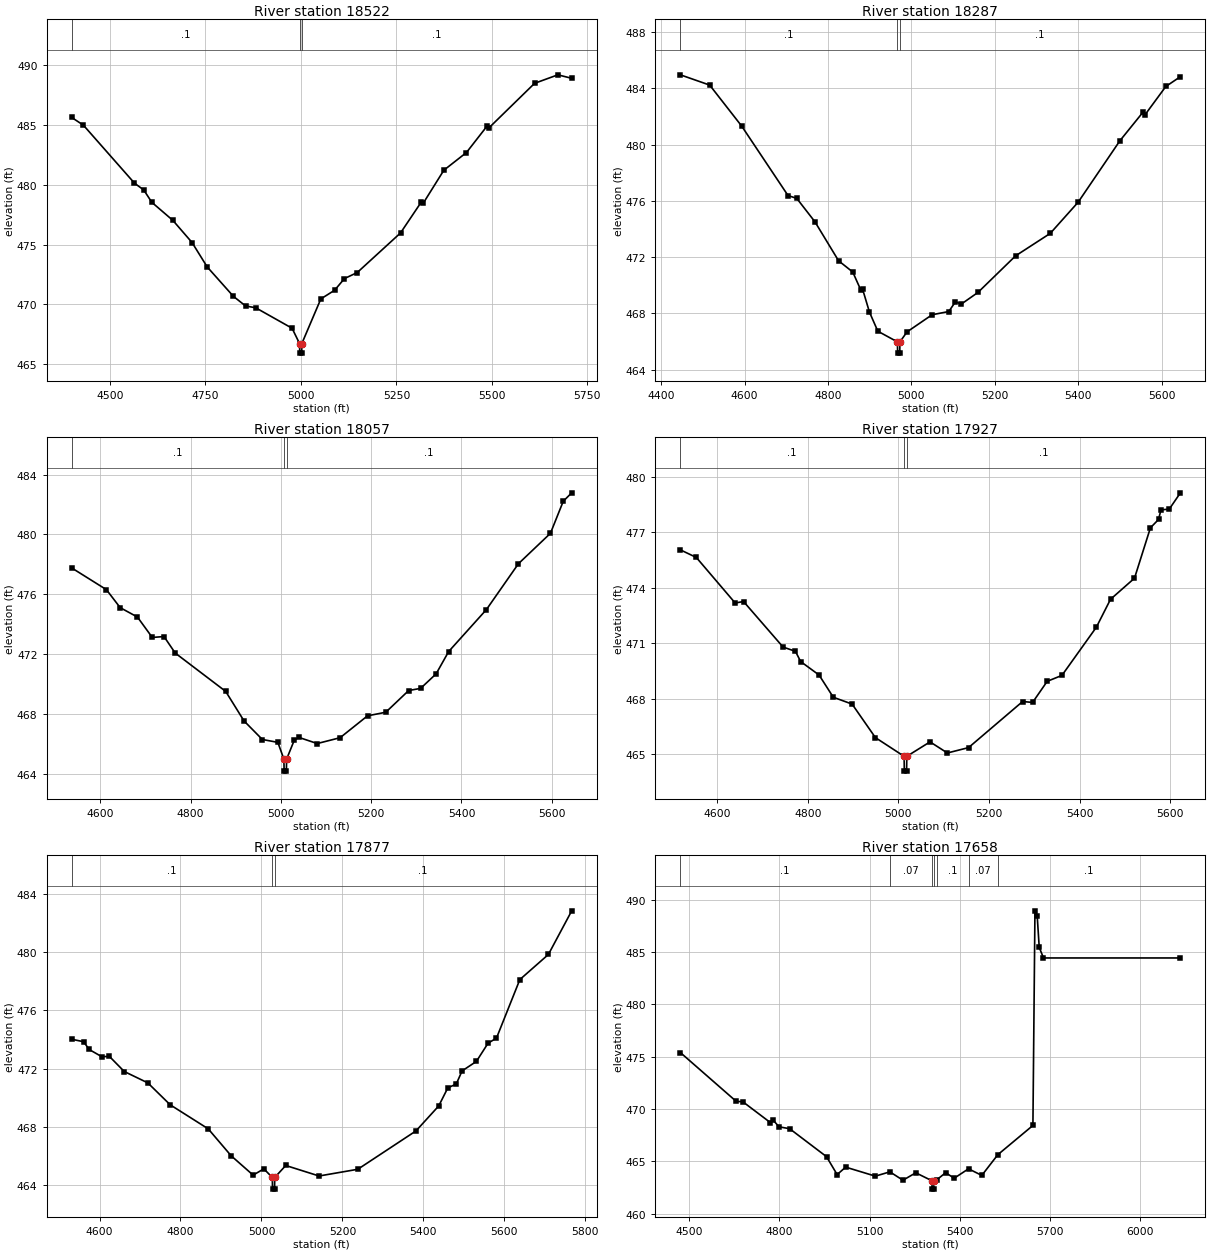
Type RM Length L Ch R = 1 ,18522   ,235,235,235
BEGIN DESCRIPTION:
Little Calf Creek 26.0
END DESCRIPTION:
XS GIS Cut Line= 3
      2006847.75     13441994.21      2007061.28      13441348.4
      2006952.02     13440729.26
#Sta/Elev= 30
    4400  485.62  4430.8  484.97  4564.4  480.13  4588.7  479.56  4609.8  478.53
  4664.9  477.02  4715.1  475.17  4754.8  473.13  4823.5  470.67  4855.2  469.87
  4881.7  469.72  4976.9  468.01  4996.5  466.73    4997  465.93    5002  465.93
  5002.5  466.73  5052.2  470.46  5088.1  471.18  5114.1  472.16  5147.4  472.66
  5260.8  475.97  5314.9  478.54    5320  478.44  5374.2  481.21  5433.4  482.69
  5487.6  484.91  5492.6  484.76  5611.7  488.47  5672.6  489.18  5708.9  488.89
#Mann= 3 ,-1 , 0
    4400      .1       0  4996.5     .07       0  5002.5      .1       0
Bank Sta=4996.5,5002.5
XS Rating Curve= 0 ,0
Exp/Cntr=0.3,0.1

Type RM Length L Ch R = 1 ,18287   ,230,230,230
BEGIN DESCRIPTION:
Mapping XS 44e3fe53
END DESCRIPTION:
XS GIS Cut Line= 3
      2007108.17     13442072.31      2007217.53     13441707.78
      2007253.99     13440890.08
#Sta/Elev= 30
    4446  484.97  4516.3  484.24  4593.1  481.32  4704.2  476.38  4725.1  476.18
  4768.8  474.51  4825.4  471.74  4859.4  470.94  4878.2  469.69  4883.2   469.7
  4899.4  468.09  4919.5  466.73  4966.5  465.97    4967  465.17    4972  465.17
  4972.5  465.97  4989.5  466.68  5049.6   467.9  5089.6  468.13  5105.6  468.82
  5119.7  468.66  5159.7  469.49  5249.8  472.09    5333  473.69  5399.9  475.91
    5500  480.28  5555.3  482.31  5560.3  482.13  5610.1  484.14  5645.1  484.84
#Mann= 3 ,-1 , 0
    4446      .1       0  4966.5     .07       0  4972.5      .1       0
Bank Sta=4966.5,4972.5
XS Rating Curve= 0 ,0
Exp/Cntr=0.3,0.1

Type RM Length L Ch R = 1 ,18057   ,130,130,130
BEGIN DESCRIPTION:
Mapping XS 2cd38353
END DESCRIPTION:
XS GIS Cut Line= 3
      2007373.78     13442030.72       2007446.7     13441624.44
      2007337.56     13440938.44
#Sta/Elev= 30
  4536.7  477.77  4613.6  476.32  4644.1  475.12  4682.4  474.49  4715.2  473.13
  4741.2  473.19    4766  472.09  4877.8  469.53  4918.4  467.56    4959  466.32
  4993.3  466.13  5006.7  465.01  5007.2  464.21  5012.2  464.21  5012.7  465.01
  5029.9  466.29    5040  466.46  5080.5  466.05  5131.2  466.44  5191.9   467.9
  5232.4  468.14  5283.1  469.59  5309.4  469.73  5343.8   470.7  5371.6  472.19
  5455.2  474.99  5526.1  478.05    5597  480.08  5625.4  482.22  5644.1  482.78
#Mann= 3 ,-1 , 0
  4536.7      .1       0  5006.7     .07       0  5012.7      .1       0
Bank Sta=5006.7,5012.7
XS Rating Curve= 0 ,0
Exp/Cntr=0.3,0.1

Type RM Length L Ch R = 1 ,17927   ,50,50,50
BEGIN DESCRIPTION:
Mapping XS f7e3cd54
END DESCRIPTION:
XS GIS Cut Line= 4
      2007446.93     13442038.78      2007562.22     13441643.52
      2007576.86     13441482.49      2007371.93     13440993.96
#Sta/Elev= 30
    4519  476.05  4554.2  475.64  4639.9  473.18  4658.4  473.26  4745.6   470.8
  4772.9  470.57  4784.3  470.02    4825  469.29  4856.4  468.09  4897.9  467.72
  4949.3  465.91  5012.6   464.9  5013.1   464.1  5018.1   464.1  5018.6   464.9
  5069.8  465.68  5108.1  465.08  5154.8  465.37  5274.1  467.86  5296.1  467.81
  5328.3  468.95  5360.8  469.27  5436.7  471.87    5468  473.38  5520.9  474.52
    5556  477.24  5573.9  477.69  5579.3  478.21  5597.6  478.25  5622.2  479.13
#Mann= 3 ,-1 , 0
    4519      .1       0  5012.6     .07       0  5018.6      .1       0
Bank Sta=5012.6,5018.6
XS Rating Curve= 0 ,0
Exp/Cntr=0.3,0.1

Type RM Length L Ch R = 1 ,17877   ,219,219,219
BEGIN DESCRIPTION:
Mapping XS c4d145f8
END DESCRIPTION:
XS GIS Cut Line= 5
        2007500.     13442025.95      2007600.64      13441722.2
      2007629.92     13441487.98      2007673.84     13441332.45
      2007352.94     13440926.51
#Sta/Elev= 30
  4531.2  474.02  4560.8  473.85  4574.3  473.32  4605.9  472.82  4624.2  472.85
  4661.1  471.81  4719.3  471.03  4774.5  469.53  4868.5  467.88  4925.3  466.03
  4979.4  464.71  5005.9  465.14  5026.8  464.55  5027.3  463.75  5032.3  463.75
  5032.8  464.55    5060  465.37  5142.3  464.65  5237.9  465.11  5381.7  467.74
  5437.8  469.45  5460.3  470.69  5481.1  470.95  5495.5  471.85  5530.8   472.5
  5559.7  473.75  5580.5   474.1  5638.2  478.11  5708.7  479.83  5766.3  482.82
#Mann= 3 ,-1 , 0
  4531.2      .1       0  5026.8     .07       0  5032.8      .1       0
Bank Sta=5026.8,5032.8
XS Rating Curve= 0 ,0
Exp/Cntr=0.3,0.1

Type RM Length L Ch R = 1 ,17658   ,250,250,250
BEGIN DESCRIPTION:
Mapping XS 640dd04e
END DESCRIPTION:
XS GIS Cut Line= 4
      2007483.14     13442093.22      2007811.28      13441660.9
      2008123.78     13441317.15      2008571.68     13440838.01
#Sta/Elev= 30
  4470.7   475.4  4656.8  470.73  4678.1  470.71  4769.8  468.72  4777.9     469
  4798.7  468.31  4834.1  468.13  4956.8  465.46  4992.1  463.75  5020.5  464.46
  5119.2   463.6  5167.5  464.01  5211.1  463.21  5253.7  463.92  5307.4  463.16
  5307.9  462.36  5312.9  462.36  5313.4  463.16  5323.2  463.24    5353  463.93
  5381.4   463.4  5429.1   464.3  5473.3  463.67  5526.7  465.65  5643.3  468.44
  5650.1  488.93  5657.5  488.47  5664.3  485.44  5678.5  484.43  6133.9  484.43
#Mann= 7 ,-1 , 0
  4470.7      .1       0  5167.5     .07       0  5307.4     .07       0
  5313.4     .07       0  5323.2      .1       0  5429.1     .07       0
  5526.7      .1       0
Bank Sta=5307.4,5313.4
XS Rating Curve= 0 ,0
Exp/Cntr=0.3,0.1

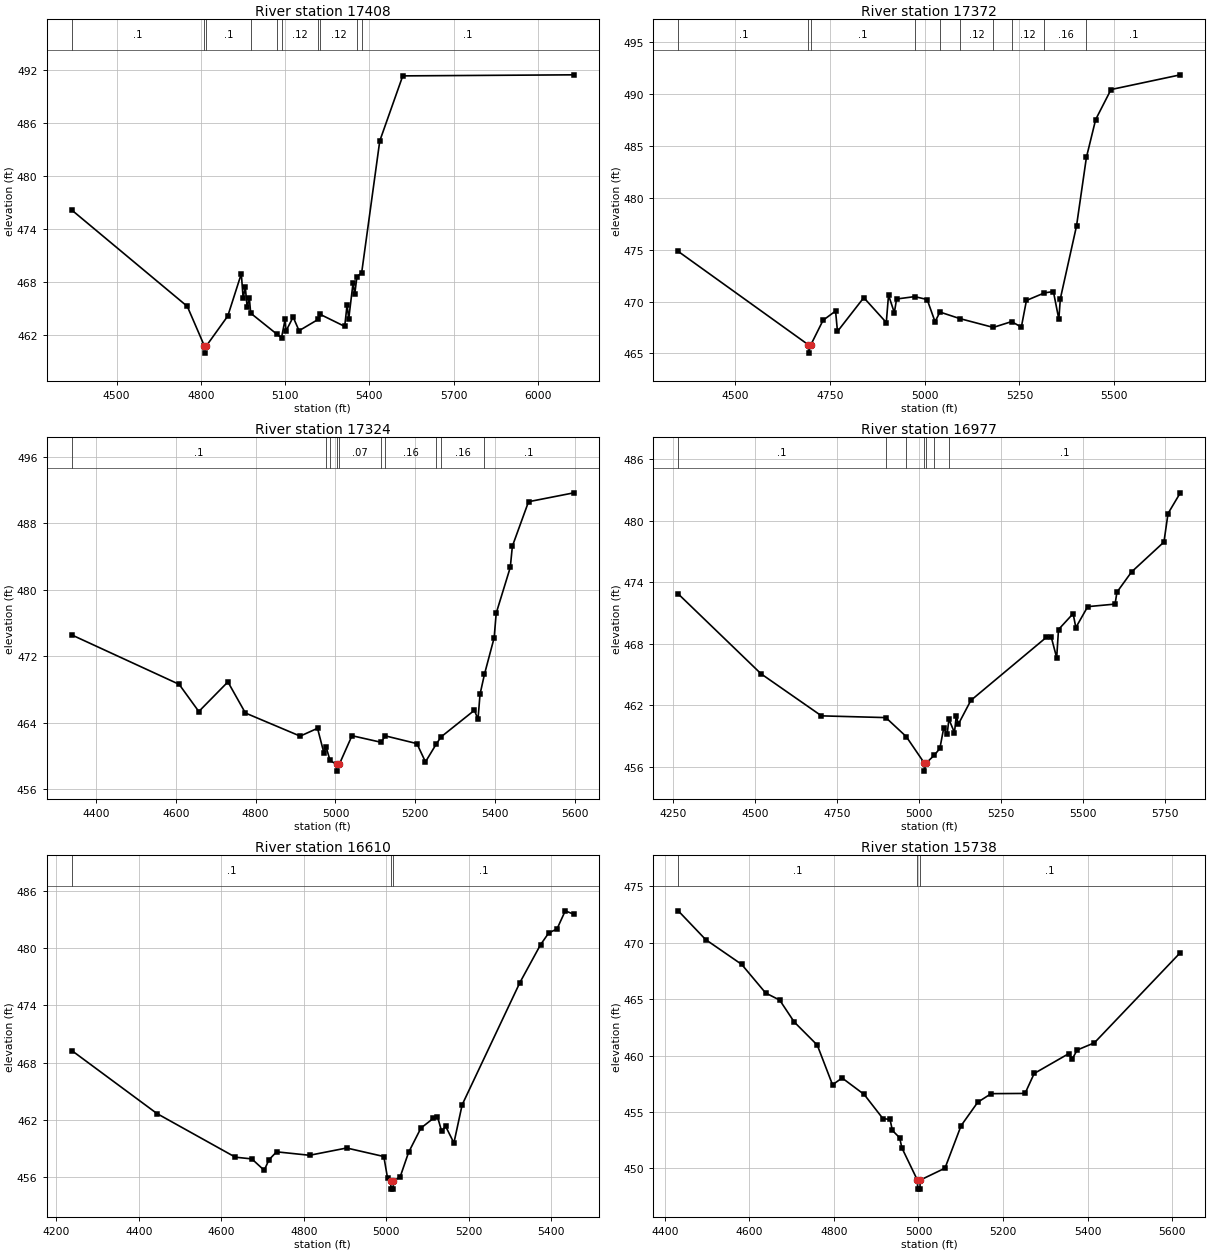
Type RM Length L Ch R = 1 ,17408   ,36,36,36
BEGIN DESCRIPTION:
Little Calf Creek 25.0
END DESCRIPTION:
XS GIS Cut Line= 6
      2007479.64     13442129.73      2007819.91     13441834.61
      2007960.53     13441838.08       2008401.5     13441490.86
      2008582.06     13441511.69      2008967.44     13441277.34
#Sta/Elev= 30
  4340.5  476.11  4751.8  465.19  4812.8  460.69  4813.3  459.89  4819.2  460.69
    4896   464.1  4944.1  468.89  4950.6  466.15  4958.4  467.34  4964.9  465.09
  4972.7  466.13  4977.5  464.42  5069.9  462.06  5087.3  461.65  5100.3  463.76
    5103  462.38  5128.6  463.98  5149.7  462.43    5218  463.72  5225.9  464.27
  5312.2  462.92  5320.7  465.38  5326.5  463.76    5342  467.87  5347.8  466.54
  5355.8  468.57  5372.5  468.98    5437  483.94  5518.9  491.32    6128  491.44
#Mann= 10 ,-1 , 0
  4340.5      .1       0  4812.8     .07       0  4819.2      .1       0
  4977.5     .12       0  5069.9      .1       0  5087.3     .12       0
    5218      .1       0  5225.9     .12       0  5355.8     .16       0
  5372.5      .1       0
Bank Sta=4812.8,4819.2
XS Rating Curve= 0 ,0
Exp/Cntr=0.3,0.1

Type RM Length L Ch R = 1 ,17372   ,48,48,48
BEGIN DESCRIPTION:
Mapping XS eb6a414e
END DESCRIPTION:
XS GIS Cut Line= 6
      2007528.21     13442157.98      2007812.53     13441882.35
      2007957.93     13441864.99      2008020.86     13441825.93
        2008316.     13441565.51      2008626.31     13441526.45
#Sta/Elev= 30
  4350.5  474.84  4693.6  465.83  4694.1  465.03    4700  465.83  4732.3   468.2
  4765.2  469.09  4770.2  467.12  4839.6  470.38  4898.9  467.98  4904.8  470.63
  4920.1  468.93    4926  470.25  4973.8  470.48  5006.6   470.2  5027.4  468.06
  5040.3  468.99  5092.8  468.36  5180.9  467.51  5229.2  468.07  5254.9  467.54
  5268.3  470.11  5315.8  470.84  5339.4  470.97  5353.7   468.3  5357.7  470.28
  5400.3  477.29  5426.4  483.91  5450.8  487.56  5491.2  490.45  5673.9  491.87
#Mann= 10 ,-1 , 0
  4350.5      .1       0  4693.6     .07       0    4700      .1       0
  4973.8     .12       0  5040.3     .07       0  5092.8     .12       0
  5180.9     .16       0  5229.2     .12       0  5315.8     .16       0
  5426.4      .1       0
Bank Sta=4693.6,4700
XS Rating Curve= 0 ,0
Exp/Cntr=0.3,0.1

Type RM Length L Ch R = 1 ,17324   ,347,347,347
BEGIN DESCRIPTION:
Mapping XS 0b043af2
END DESCRIPTION:
XS GIS Cut Line= 6
       2007547.8     13442177.46      2007821.21     13441923.58
      2007979.63     13441888.86      2008081.62     13441832.44
      2008296.47     13441628.44      2008595.93     13441550.32
#Sta/Elev= 30
  4339.5  474.55  4608.4  468.61  4657.7  465.34  4730.6   468.9  4774.4  465.16
  4911.6  462.38  4955.1  463.32  4971.2  460.32  4976.1  461.13  4986.4  459.46
    5003  458.97  5003.5  458.17  5009.4  458.97  5041.4  462.43  5114.1  461.64
    5125  462.41    5204  461.48  5225.4  459.28  5252.9  461.46  5264.6  462.29
  5348.1  465.49    5357  464.39  5362.1  467.41  5373.2  469.82  5397.5  474.21
  5402.6  477.16  5437.9  482.68  5443.1  485.22  5483.6  490.57  5597.1  491.64
#Mann= 10 ,-1 , 0
  4339.5      .1       0  4976.1     .12       0  4986.4     .07       0
    5003     .07       0  5009.4     .07       0  5114.1     .12       0
    5125     .16       0  5252.9     .12       0  5264.6     .16       0
  5373.2      .1       0
Bank Sta=5003,5009.4
XS Rating Curve= 0 ,0
Exp/Cntr=0.3,0.1

Type RM Length L Ch R = 1 ,16977   ,367,367,367
BEGIN DESCRIPTION:
Mapping XS 57a85b9c
END DESCRIPTION:
XS GIS Cut Line= 3
      2007593.34     13442194.85      2008042.56     13442095.02
      2008999.58     13441611.09
#Sta/Elev= 30
  4265.4  472.87  4518.2  465.08  4702.6  460.98  4899.1  460.81  4961.6  458.95
  5016.2  456.39  5016.7  455.59  5022.6  456.39  5046.7  457.13    5064   457.8
  5075.7  459.78  5086.3  459.18  5091.6  460.65  5108.6  459.35  5114.2     461
  5120.5  460.17  5158.7  462.49  5389.5  468.65  5403.9  468.68  5420.6  466.65
  5426.2   469.4  5470.8  470.95  5479.1  469.59  5515.3  471.63  5598.9  471.88
  5604.5  473.04    5649  475.01    5748  477.93  5760.5  480.71    5798  482.73
#Mann= 7 ,-1 , 0
  4265.4      .1       0  4899.1     .07       0  4961.6      .1       0
  5016.2     .07       0  5022.6      .1       0  5046.7     .07       0
  5091.6      .1       0
Bank Sta=5016.2,5022.6
XS Rating Curve= 0 ,0
Exp/Cntr=0.3,0.1

Type RM Length L Ch R = 1 ,16610   ,872,872,872
BEGIN DESCRIPTION:
Mapping XS f00f65b7
END DESCRIPTION:
XS GIS Cut Line= 2
      2007708.34     13442236.08      2008925.84     13442194.85
#Sta/Elev= 30
  4237.1  469.27  4443.9  462.68    4634  458.12    4674  457.94    4704  456.75
  4715.6  457.85    4734  458.68  4814.1  458.32  4904.1  459.08  4994.2  458.19
  5003.4  455.91    5011  455.58  5011.5  454.78    5017  454.78  5017.5  455.58
  5034.2   456.1  5054.2  458.61  5084.2  461.16  5114.3  462.18  5124.3  462.37
  5134.3  460.87  5144.3  461.34  5164.3  459.61  5184.3   463.6  5324.4  476.38
  5374.4  480.33  5394.4  481.57  5414.4  481.98  5434.5  483.88  5455.3  483.52
#Mann= 3 ,-1 , 0
  4237.1      .1       0    5011     .07       0  5017.5      .1       0
Bank Sta=5011,5017.5
XS Rating Curve= 0 ,0
Exp/Cntr=0.3,0.1

Type RM Length L Ch R = 1 ,15738   ,286,286,286
BEGIN DESCRIPTION:
Little Calf Creek 24.0
END DESCRIPTION:
XS GIS Cut Line= 3
      2007558.66     13442303.37        2008125.       13442575.
      2008674.97     13442674.99
#Sta/Elev= 30
    4432  472.84  4496.8  470.29  4581.9  468.09  4638.7  465.55  4671.9  464.92
  4706.2  462.98  4760.7  460.93  4796.8  457.41  4819.5  458.01  4871.6  456.55
  4915.9  454.41  4932.8  454.33  4938.3  453.36  4955.4  452.71  4960.9   451.8
  4997.5  448.95    4998  448.15  5003.5  448.15    5004  448.95  5062.7  450.01
  5100.8  453.78  5140.2  455.86  5171.9  456.62    5252  456.64  5273.6  458.41
  5354.9  460.16  5363.8  459.71  5375.2  460.49  5415.9  461.13  5619.1  469.13
#Mann= 3 ,-1 , 0
    4432      .1       0  4997.5     .07       0    5004      .1       0
Bank Sta=4997.5,5004
XS Rating Curve= 0 ,0
Exp/Cntr=0.3,0.1

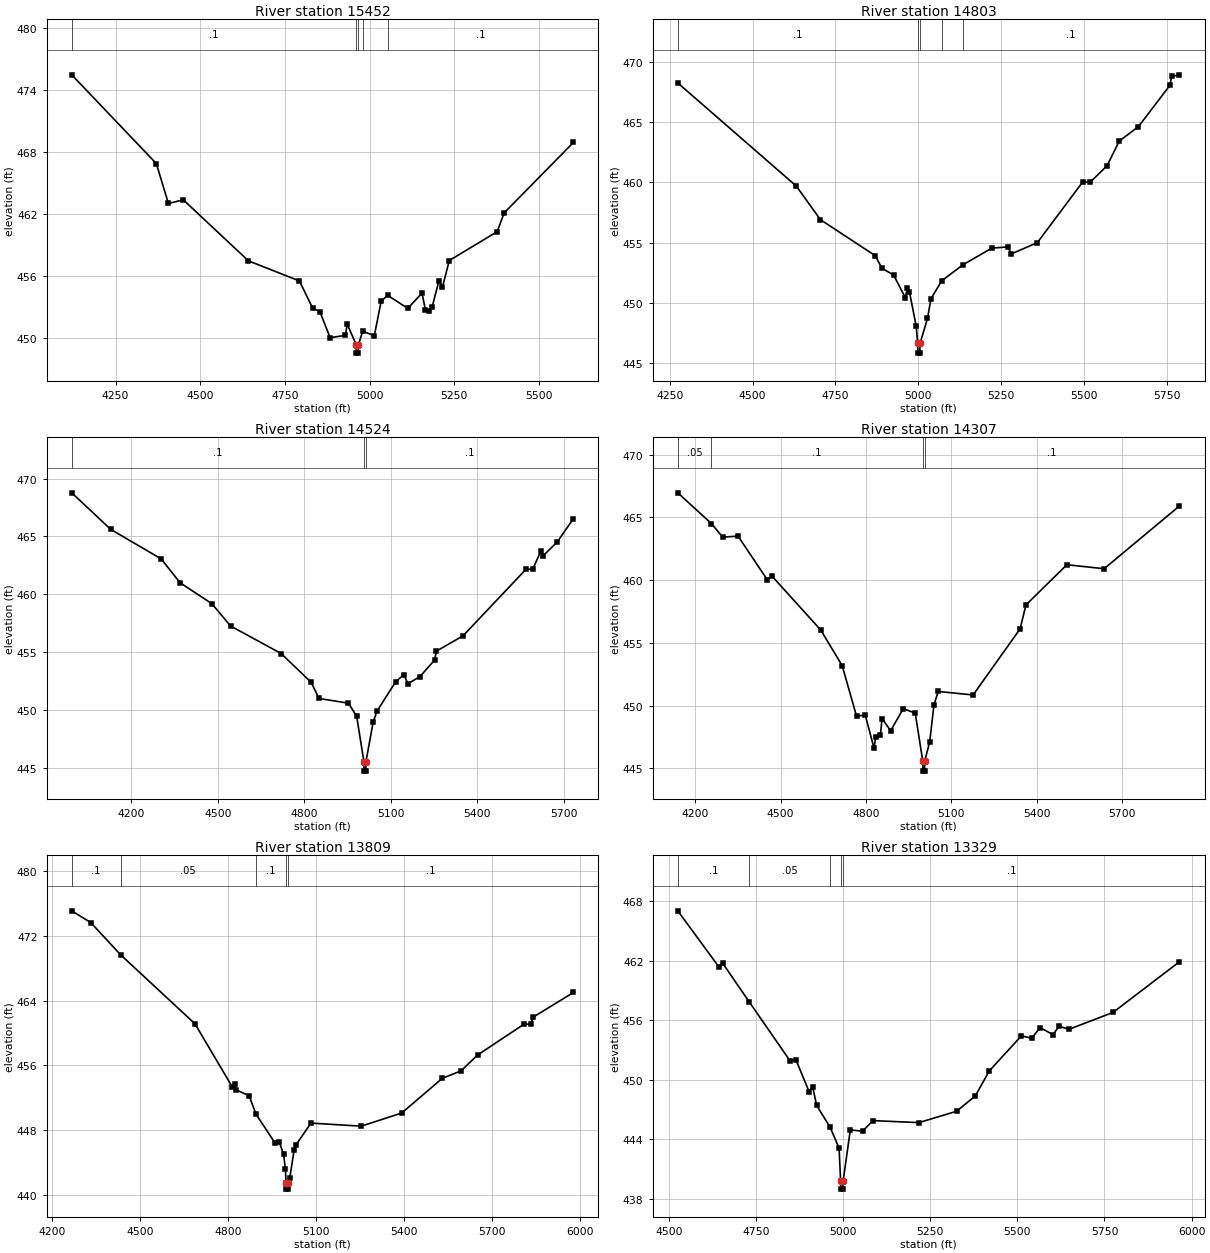
Type RM Length L Ch R = 1 ,15452   ,649,649,649
BEGIN DESCRIPTION:
Little Calf Creek 23.0
END DESCRIPTION:
XS GIS Cut Line= 4
      2007424.98     13442324.97      2007743.08     13442761.26
      2008409.32     13442832.87      2008674.98     13442775.01
#Sta/Elev= 30
  4120.4  475.49  4370.3  466.89  4405.9  463.03  4449.9  463.38  4642.3  457.47
    4793  455.52    4832  452.89  4853.4  452.55  4883.5  450.03    4929  450.25
  4934.1  451.35  4960.7  449.33  4961.2  448.53  4966.7  448.53  4967.2  449.33
  4979.6  450.64  5014.3  450.23  5034.4  453.56  5053.7  454.13  5113.1  452.86
  5155.1  454.35  5165.1  452.73  5175.2  452.64  5185.3  453.04  5205.2  455.56
  5215.4  454.91  5235.6   457.5  5377.2   460.3  5397.6  462.11  5602.3  468.94
#Mann= 5 ,-1 , 0
  4120.4      .1       0  4960.7     .07       0  4967.2      .1       0
  4979.6     .12       0  5053.7      .1       0
Bank Sta=4960.7,4967.2
XS Rating Curve= 0 ,0
Exp/Cntr=0.3,0.1

Type RM Length L Ch R = 1 ,14803   ,279,279,279
BEGIN DESCRIPTION:
Little Calf Creek 22.0
END DESCRIPTION:
XS GIS Cut Line= 3
      2007298.25     13443412.28        2008025.       13443225.
      2008674.99       13442825.
#Sta/Elev= 30
  4274.5  468.24  4632.6  459.68  4704.9  456.91  4870.1  453.93  4890.7  452.88
  4925.8  452.32  4961.4  450.43  4966.5  451.22  4973.4  450.95    4994  448.07
  4998.6  446.65  4999.1  445.85    5005  445.85  5005.5  446.65  5027.9  448.72
  5038.6  450.36  5070.8  451.84  5134.4  453.16    5222  454.55  5271.6  454.65
    5280  454.06  5359.3     455  5496.5  460.04  5518.1  459.99  5569.9  461.38
  5606.6  463.42  5664.6  464.62  5759.2  468.03  5765.1  468.78  5788.2  468.91
#Mann= 5 ,-1 , 0
  4274.5      .1       0  4998.6     .07       0  5005.5      .1       0
  5070.8     .07       0  5134.4      .1       0
Bank Sta=4998.6,5005.5
XS Rating Curve= 0 ,0
Exp/Cntr=0.3,0.1

Type RM Length L Ch R = 1 ,14524   ,217,217,217
BEGIN DESCRIPTION:
Little Calf Creek 21.0
END DESCRIPTION:
XS GIS Cut Line= 3
      2007183.16     13443789.91      2008042.56     13443529.48
      2008679.26     13442979.41
#Sta/Elev= 30
  3993.4  468.78  4128.5  465.62  4303.5  463.06  4369.3  460.99  4478.5   459.2
  4544.3  457.25  4719.4  454.87  4823.3  452.38    4851  450.98  4952.9  450.57
  4981.4  449.43  5006.5  445.49    5007  444.69  5012.9  444.69  5013.4  445.49
  5038.5  448.95  5052.7  449.92  5116.4  452.42  5144.9  453.05  5158.9  452.25
  5200.9  452.88  5251.3   454.3  5257.9  455.08    5350   456.4  5569.4  462.19
  5591.3  462.15  5619.8  463.73  5626.4   463.3  5675.8   464.5  5732.8  466.54
#Mann= 3 ,-1 , 0
  3993.4      .1       0  5006.5     .07       0  5013.4      .1       0
Bank Sta=5006.5,5013.4
XS Rating Curve= 0 ,0
Exp/Cntr=0.3,0.1

Type RM Length L Ch R = 1 ,14307   ,498,498,498
BEGIN DESCRIPTION:
Little Calf Creek 20.0
END DESCRIPTION:
XS GIS Cut Line= 3
      2007415.39     13444048.15      2008092.47     13443711.78
       2008923.6      13443145.4
#Sta/Elev= 30
  4139.2  466.95  4257.6   464.5  4296.5  463.42  4350.9   463.5  4453.4  460.03
  4470.2  460.31  4641.2  456.02  4716.6  453.18    4767  449.15  4797.6  449.24
  4828.6  446.58  4834.2  447.52    4851  447.66  4856.6  448.96  4886.9  447.99
  4931.2  449.75  4973.2  449.39  4999.6  445.57  5000.1  444.77    5006  444.77
  5006.5  445.57    5024  447.11    5039  450.05  5053.9  451.12  5176.5  450.84
  5341.2   456.1  5362.1  458.02  5505.8  461.22  5636.5   460.9    5901   465.9
#Mann= 4 ,-1 , 0
  4139.2     .05       0  4257.6      .1       0  4999.6     .07       0
  5006.5      .1       0
Bank Sta=4999.6,5006.5
XS Rating Curve= 0 ,0
Exp/Cntr=0.3,0.1

Type RM Length L Ch R = 1 ,13809   ,480,480,480
BEGIN DESCRIPTION:
Little Calf Creek 19.0
END DESCRIPTION:
XS GIS Cut Line= 3
      2007889.34     13444511.27      2008319.04     13444146.67
      2008954.43     13443193.59
#Sta/Elev= 30
  4267.8  475.09  4332.9  473.63  4434.1  469.67  4687.7  461.14  4815.1  453.33
  4822.8  453.76  4828.8  452.99  4872.3  452.25  4895.2  450.01  4959.4  446.48
  4974.4  446.58  4989.4  445.05  4995.5  443.26  4998.1  441.54  4998.6  440.74
  5004.7  440.74  5005.2  441.54  5010.5  442.11  5025.5  445.61  5031.5  446.18
  5082.6  448.89    5254  448.51  5392.1  450.14  5530.3  454.42  5593.4  455.33
  5650.6   457.3  5809.7  461.13  5830.9  461.06  5839.8  461.97  5976.8  465.01
#Mann= 5 ,-1 , 0
  4267.8      .1       0  4434.1     .05       0  4895.2      .1       0
  4998.1     .07       0  5005.2      .1       0
Bank Sta=4998.1,5005.2
XS Rating Curve= 0 ,0
Exp/Cntr=0.3,0.1

Type RM Length L Ch R = 1 ,13329   ,525,525,525
BEGIN DESCRIPTION:
Mapping XS 08575bc2
END DESCRIPTION:
XS GIS Cut Line= 2
      2008584.67     13444694.91       2009117.8      13443358.2
#Sta/Elev= 30
  4525.9  467.03  4643.5   461.4    4655  461.74  4730.3  457.89  4848.8  451.88
  4864.6  452.05  4902.6  448.82  4913.1  449.31  4924.1  447.44    4963  445.23
  4988.7  443.12  4993.1   439.8  4993.6     439  4999.7     439  5000.2   439.8
  5020.9  444.97  5055.9  444.83  5085.6   445.9  5217.7   445.7  5325.5  446.84
  5379.4  448.38  5419.4   450.9  5511.5  454.43  5541.1  454.21  5565.4  455.26
  5602.4  454.56  5619.3  455.39  5648.9  455.11  5774.7   456.8    5965   461.9
#Mann= 5 ,-1 , 0
  4525.9      .1       0  4730.3     .05       0    4963      .1       0
  4993.1     .07       0  5000.2      .1       0
Bank Sta=4993.1,5000.2
XS Rating Curve= 0 ,0
Exp/Cntr=0.3,0.1

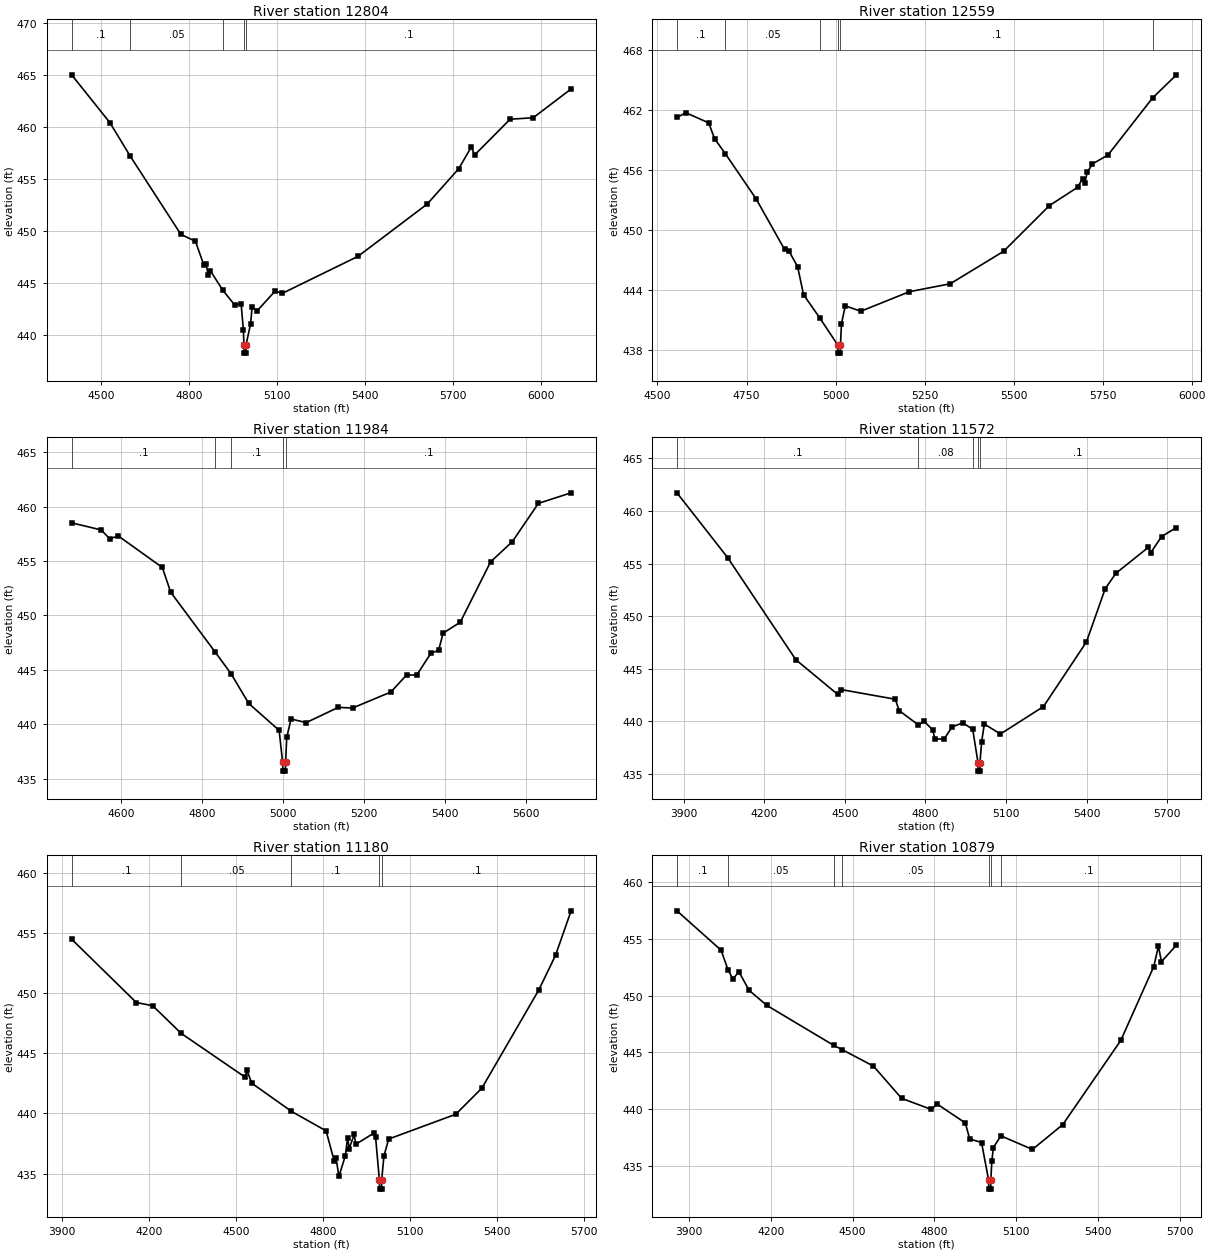
Type RM Length L Ch R = 1 ,12804   ,245,245,245
BEGIN DESCRIPTION:
Little Calf Creek 18.0
END DESCRIPTION:
XS GIS Cut Line= 3
      2008889.34     13444773.07      2009214.87     13444369.42
      2009646.76     13443268.89
#Sta/Elev= 30
    4401  464.99  4531.5  460.38  4599.6  457.21    4773  449.64  4822.6  448.98
  4851.3  446.68  4859.3  446.75  4865.7  445.76  4873.7  446.13  4916.2  444.25
  4956.1  442.86    4978  442.99  4985.9  440.46  4987.6  439.02  4988.1  438.22
  4994.3  438.22  4994.9  439.02  5010.2  441.01  5015.7  442.68  5031.7  442.26
  5094.3   444.2  5117.7  443.96  5376.2  447.53  5611.8  452.56  5719.2  455.96
  5762.2  458.06    5773  457.27  5894.1  460.72  5972.8  460.86  6101.8  463.63
#Mann= 5 ,-1 , 0
    4401      .1       0  4599.6     .05       0  4916.2      .1       0
  4987.6     .07       0  4994.9      .1       0
Bank Sta=4987.6,4994.9
XS Rating Curve= 0 ,0
Exp/Cntr=0.3,0.1

Type RM Length L Ch R = 1 ,12559   ,575,575,575
BEGIN DESCRIPTION:
Little Calf Creek 17.0
END DESCRIPTION:
XS GIS Cut Line= 3
      2009303.41     13444788.69      2009537.79     13444150.67
      2009975.01     13443574.99
#Sta/Elev= 30
  4554.7  461.29  4579.9  461.76  4643.9  460.74  4660.3  459.16  4690.6  457.65
  4776.9  453.13  4856.9  448.05  4868.4  447.94  4893.5  446.33  4910.2  443.52
  4955.1  441.22  5006.5  438.46    5007  437.66  5013.2  437.66  5013.8  438.46
  5016.7  440.62  5027.4   442.4  5071.1  441.86  5207.5  443.82  5321.9  444.61
  5471.7  447.86  5600.6  452.45  5679.6  454.28  5693.6  455.14  5700.4  454.75
  5706.7  455.77  5721.3  456.63  5764.9  457.51  5890.3  463.24  5957.3  465.56
#Mann= 6 ,-1 , 0
  4554.7      .1       0  4690.6     .05       0  4955.1      .1       0
  5006.5     .07       0  5013.8      .1       0  5890.3     .05       0
Bank Sta=5006.5,5013.8
XS Rating Curve= 0 ,0
Exp/Cntr=0.3,0.1

Type RM Length L Ch R = 1 ,11984   ,412,412,412
BEGIN DESCRIPTION:
Little Calf Creek 16.0
END DESCRIPTION:
XS GIS Cut Line= 3
      2009561.25     13444773.04        2009975.       13444475.
      2010235.54     13443799.53
#Sta/Elev= 30
  4477.5  458.51  4550.5  457.86  4571.4  457.05    4593   457.3  4701.5  454.41
  4722.3  452.13  4831.4  446.67  4871.4  444.64    4915  441.91  4990.1  439.44
  4998.8  436.49  4999.3  435.69  5005.5  435.69  5006.1  436.49  5008.9  438.79
  5019.6  440.48    5057  440.15  5136.2  441.55  5171.5  441.49  5266.1  442.96
  5305.3  444.54  5329.9  444.51  5365.2  446.54    5384  446.78  5395.2  448.37
  5437.6  449.38  5512.6  454.93  5566.2  456.78  5630.5   460.3  5711.4  461.27
#Mann= 5 ,-1 , 0
  4477.5      .1       0  4831.4     .05       0  4871.4      .1       0
  4998.8     .07       0  5006.1      .1       0
Bank Sta=4998.8,5006.1
XS Rating Curve= 0 ,0
Exp/Cntr=0.3,0.1

Type RM Length L Ch R = 1 ,11572   ,392,392,392
BEGIN DESCRIPTION:
Little Calf Creek 15.0
END DESCRIPTION:
XS GIS Cut Line= 3
      2009988.32     13445611.58      2010346.35     13444699.48
      2010342.47     13443819.94
#Sta/Elev= 30
  3875.2  461.72  4064.9  455.53  4317.5  445.87  4473.1  442.58  4485.6  443.03
    4688  442.11  4702.5  441.03  4774.3  439.66  4795.4  440.01  4827.6  439.19
  4835.3  438.35  4869.5  438.32  4899.5  439.48  4939.5  439.87  4976.3  439.25
  4995.9  436.08  4996.4  435.28  5002.6  435.28  5003.2  436.08  5009.5  438.08
  5019.5  439.75  5079.5  438.81  5239.5  441.41  5399.5  447.55  5469.5  452.61
  5509.5  454.08  5629.5  456.53  5639.5  456.05  5679.5  457.57  5734.6  458.42
#Mann= 5 ,-1 , 0
  3875.2      .1       0  4774.3     .08       0  4976.3      .1       0
  4995.9     .07       0  5003.2      .1       0
Bank Sta=4995.9,5003.2
XS Rating Curve= 0 ,0
Exp/Cntr=0.3,0.1

Type RM Length L Ch R = 1 ,11180   ,301,301,301
BEGIN DESCRIPTION:
Little Calf Creek 14.0
END DESCRIPTION:
XS GIS Cut Line= 3
      2010233.08     13445577.78      2010675.81     13444640.25
      2010974.98     13444025.04
#Sta/Elev= 30
  3934.6   454.5  4157.4  449.23  4214.1  448.96  4312.1  446.66  4532.8  443.01
  4538.3  443.58  4555.6  442.51  4692.1  440.17  4811.3  438.55  4839.8     436
  4845.4  436.32  4855.6  434.76  4877.7  436.48  4885.4  437.99  4890.9  437.08
  4908.2  438.25  4913.7  437.43  4976.3  438.37  4981.9  438.02  4994.8   434.5
  4995.5   433.7  5002.3   433.7    5003   434.5  5010.6  436.45    5027  437.87
  5258.1  439.93  5348.3  442.11  5544.4  450.28  5601.9  453.16  5655.5  456.86
#Mann= 5 ,-1 , 0
  3934.6      .1       0  4312.1     .05       0  4692.1      .1       0
  4994.8     .07       0    5003      .1       0
Bank Sta=4994.8,5003
XS Rating Curve= 0 ,0
Exp/Cntr=0.3,0.1

Type RM Length L Ch R = 1 ,10879   ,468,468,468
BEGIN DESCRIPTION:
Little Calf Creek 13.0
END DESCRIPTION:
XS GIS Cut Line= 3
      2010380.27     13445748.71      2010970.08     13444681.92
      2011225.01     13444124.97
#Sta/Elev= 30
    3856  457.49  4017.6  454.02  4042.9  452.31  4061.2  451.46  4082.9  452.12
  4120.7  450.47    4186  449.14  4431.7  445.61  4462.9  445.23  4576.6  443.79
  4679.7  440.95  4788.5  439.97  4810.3  440.44  4913.3  438.78  4929.4  437.37
  4972.9  437.05  4998.8  433.74  4999.5  432.94  5006.3  432.94    5007  433.74
  5010.7  435.45  5016.4  436.61  5043.9  437.64  5159.6  436.44    5271  438.64
  5483.6  446.06  5604.2  452.56  5621.5  454.36  5632.7  453.01  5687.5  454.46
#Mann= 7 ,-1 , 0
    3856      .1       0  4042.9     .05       0  4431.7      .1       0
  4462.9     .05       0  4998.8     .03       0    5007     .05       0
  5043.9      .1       0
Bank Sta=4998.8,5007
XS Rating Curve= 0 ,0
Exp/Cntr=0.3,0.1

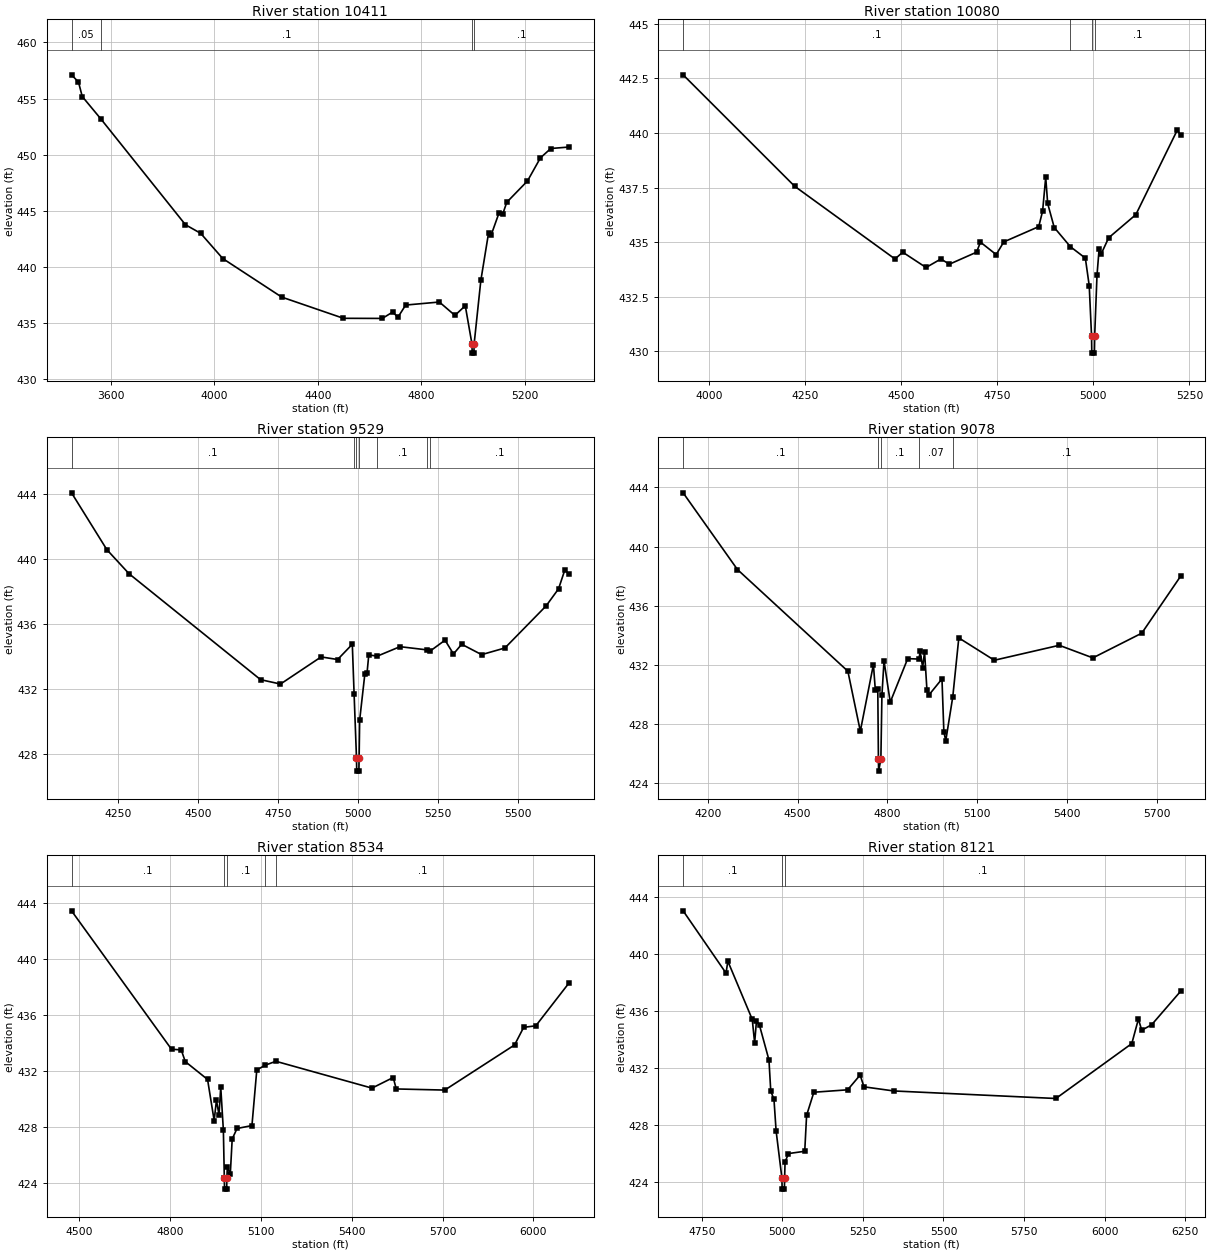
Type RM Length L Ch R = 1 ,10411   ,331,331,331
BEGIN DESCRIPTION:
Little Calf Creek 12.0
END DESCRIPTION:
XS GIS Cut Line= 3
      2010722.69     13445999.61      2011321.64     13445184.52
        2011375.     13444274.97
#Sta/Elev= 30
  3447.6  457.12  3474.4  456.48    3489  455.19  3561.4  453.18    3888  443.77
  3946.6  443.01  4032.2  440.76  4259.9  437.33  4498.7  435.44  4648.9  435.43
    4689     436    4709  435.53  4739.1  436.62  4869.3  436.89  4929.4   435.7
  4969.5  436.56  4995.4  433.14  4996.1  432.34  5002.9  432.34  5003.6  433.14
  5029.6  438.81  5059.6  443.06  5069.7  442.87  5099.7  444.81  5114.4  444.73
  5129.8  445.77  5209.9  447.67    5260  449.73  5300.1  450.56  5370.2  450.69
#Mann= 4 ,-1 , 0
  3447.6     .05       0  3561.4      .1       0  4995.4     .07       0
  5003.6      .1       0
Bank Sta=4995.4,5003.6
XS Rating Curve= 0 ,0
Exp/Cntr=0.3,0.1

Type RM Length L Ch R = 1 ,10080   ,551,551,551
BEGIN DESCRIPTION:
Little Calf Creek 11.0
END DESCRIPTION:
XS GIS Cut Line= 3
        2011385.     13445755.71      2011540.39     13445457.96
      2011681.02     13444509.99
#Sta/Elev= 30
  3932.8  442.66  4222.9  437.56    4484  434.23  4504.2  434.54  4564.8  433.84
  4603.5  434.23  4625.5  433.99  4696.2  434.54  4706.4     435  4747.4  434.43
    4767  435.01    4858  435.71  4868.1  436.42  4876.2  437.97  4881.3  436.77
  4898.4  435.67  4940.5  434.79  4979.3  434.27  4989.4  433.01  4995.4  430.72
  4996.1  429.92  5002.9  429.92  5003.6  430.72  5009.6  433.48  5015.1  434.68
  5020.2  434.45    5040   435.2  5110.7  436.26  5218.5  440.13    5227  439.89
#Mann= 4 ,-1 , 0
  3932.8      .1       0  4940.5     .07       0  4995.4     .07       0
  5003.6      .1       0
Bank Sta=4995.4,5003.6
XS Rating Curve= 0 ,0
Exp/Cntr=0.3,0.1

Type RM Length L Ch R = 1 ,9529    ,451,451,451
BEGIN DESCRIPTION:
Mapping XS fe437b11
END DESCRIPTION:
XS GIS Cut Line= 4
      2011663.66     13445838.99      2011717.91     13445474.45
      2012036.92     13444777.84      2011919.85     13444372.44
#Sta/Elev= 30
  4103.6   444.1  4214.2   440.6  4283.6  439.12  4695.2   432.6  4757.5  432.33
  4884.7     434  4936.3  433.84  4982.3  434.78  4987.9  431.72  4995.4  427.77
  4996.1  426.97  5002.9  426.97  5003.6  427.77  5005.3  430.11  5021.5  432.94
  5028.3  432.99  5033.8  434.12  5060.7  434.05  5131.5  434.63  5217.4  434.43
  5225.2  434.35  5272.5  435.03  5298.9  434.18  5324.6  434.78    5387  434.14
  5459.9  434.55  5588.8  437.14  5627.7  438.19  5647.2  439.34  5660.3   439.1
#Mann= 7 ,-1 , 0
  4103.6      .1       0  4987.9     .07       0  4995.4     .07       0
  5003.6     .07       0  5060.7      .1       0  5217.4     .07       0
  5225.2      .1       0
Bank Sta=4995.4,5003.6
XS Rating Curve= 0 ,0
Exp/Cntr=0.3,0.1

Type RM Length L Ch R = 1 ,9078    ,544,544,544
BEGIN DESCRIPTION:
Mapping XS c4cf3f25
END DESCRIPTION:
XS GIS Cut Line= 4
      2011826.41     13445836.87      2011928.41     13445515.68
      2012290.83     13445036.08      2012145.79     13444328.22
#Sta/Elev= 30
  4117.9  443.63  4299.2  438.45  4667.9  431.58  4709.5  427.53  4753.2  432.03
  4759.5  430.33  4767.8  430.36  4769.9  425.63  4770.6  424.83  4778.1  425.63
  4781.6  429.95  4788.6  432.28  4809.4  429.49  4867.7  432.43  4905.3   432.4
  4909.3  432.94  4917.6  431.83  4923.9  432.89    4932  430.28  4938.4  429.97
  4982.1  431.06  4988.4  427.49  4994.7  426.88  5018.1  429.84  5038.3  433.83
  5156.9  432.32  5373.6  433.33  5485.9  432.48  5649.2  434.15  5778.6  437.99
#Mann= 5 ,-1 , 0
  4117.9      .1       0  4769.9     .07       0  4778.1      .1       0
  4905.3     .07       0  5018.1      .1       0
Bank Sta=4769.9,4778.1
XS Rating Curve= 0 ,0
Exp/Cntr=0.3,0.1

Type RM Length L Ch R = 1 ,8534    ,413,413,413
BEGIN DESCRIPTION:
Mapping XS 0bd9d574
END DESCRIPTION:
XS GIS Cut Line= 4
      2012193.17     13445826.01      2012180.15     13445563.43
      2012490.48     13445003.53      2012451.42     13444265.71
#Sta/Elev= 30
  4475.4  443.45  4805.4  433.54  4837.4   433.5  4850.8  432.66  4924.4  431.38
  4946.2  428.44  4953.7  429.89  4962.2  428.84  4967.9  430.84  4976.6  427.74
  4979.7  424.33  4980.4  423.53  4987.4  423.53  4988.2  424.33  4989.6  425.09
  4999.5  424.63  5005.7  427.12  5021.7  427.87  5070.9  428.08  5086.9  432.06
  5115.6  432.41  5149.9  432.68  5467.1  430.76  5537.2  431.52  5547.2   430.7
  5707.4  430.62  5937.8  433.85  5967.8  435.11  6007.9  435.22  6117.3  438.28
#Mann= 5 ,-1 , 0
  4475.4      .1       0  4979.7     .07       0  4988.2      .1       0
  5115.6     .07       0  5149.9      .1       0
Bank Sta=4979.7,4988.2
XS Rating Curve= 0 ,0
Exp/Cntr=0.3,0.1

Type RM Length L Ch R = 1 ,8121    ,272,272,272
BEGIN DESCRIPTION:
Mapping XS f68a5abc
END DESCRIPTION:
XS GIS Cut Line= 3
      2012457.91     13445745.75      2012711.83     13445250.93
      2012499.16     13444287.39
#Sta/Elev= 30
  4692.4  443.06  4825.5  438.68  4831.1  439.52  4906.8  435.43  4914.2  433.78
  4919.8   435.3  4929.3  435.01  4958.6  432.58  4964.2   430.4  4974.2   429.8
  4980.8  427.59  4998.7   424.3  4999.5   423.5  5006.5   423.5  5007.2   424.3
  5008.6  425.41  5019.2     426  5069.6  426.16  5075.4  428.69  5097.9  430.31
  5202.7  430.48  5241.5  431.52  5253.3  430.69  5345.8   430.4  5848.6  429.87
  6084.1  433.73  6104.6  435.45  6114.9  434.67  6145.6  435.05  6235.3   437.4
#Mann= 3 ,-1 , 0
  4692.4      .1       0  4998.7     .07       0  5007.2      .1       0
Bank Sta=4998.7,5007.2
XS Rating Curve= 0 ,0
Exp/Cntr=0.3,0.1