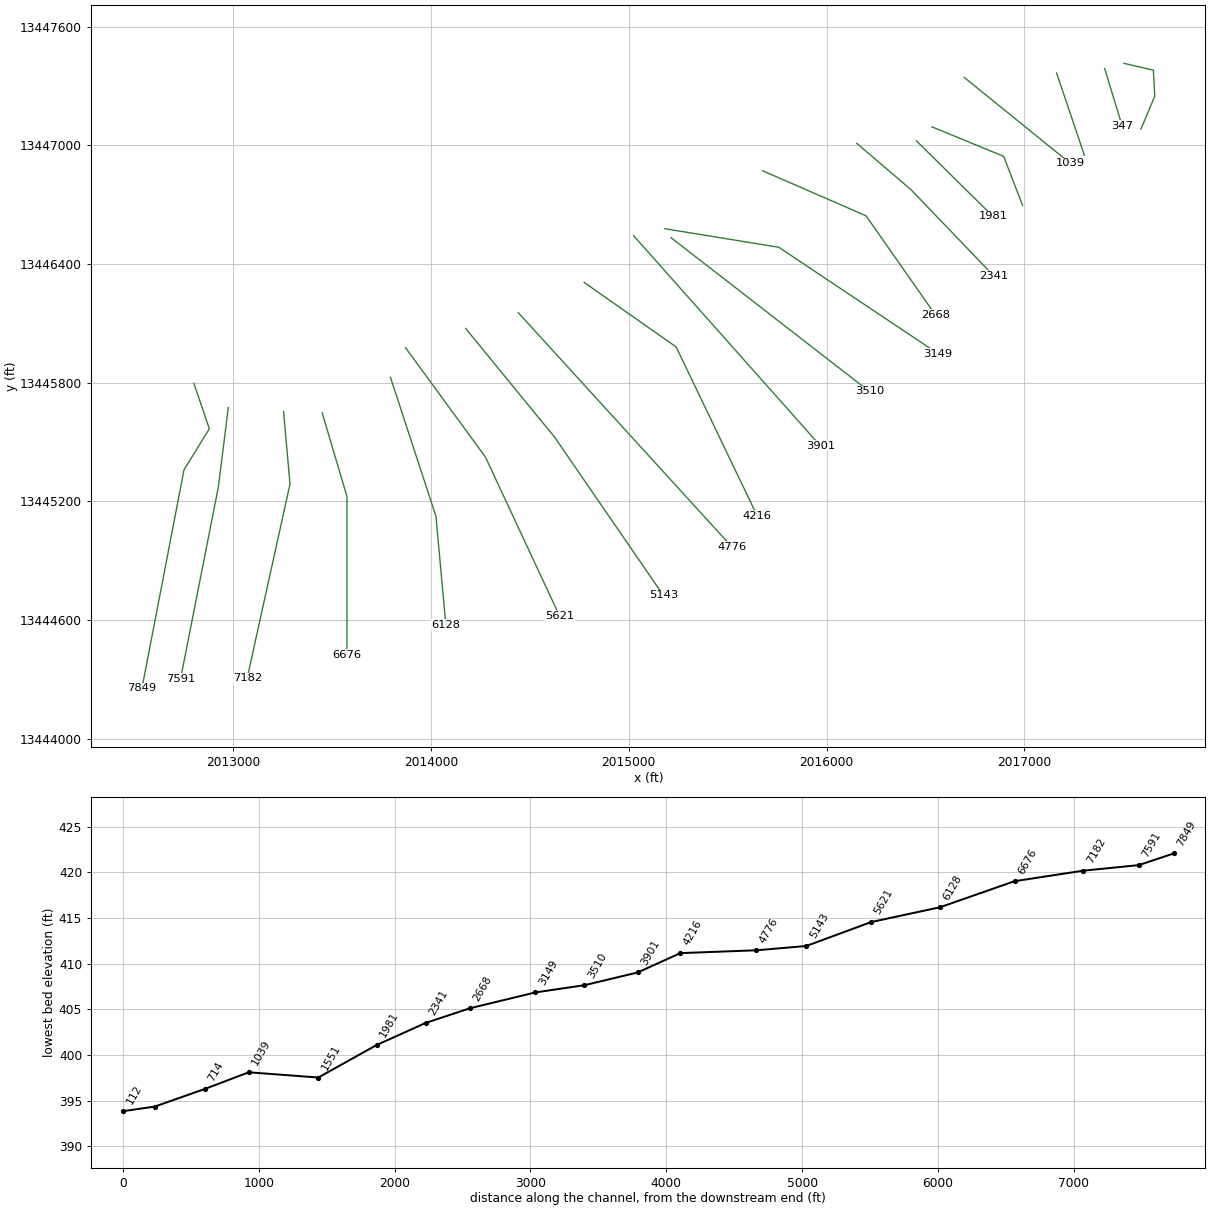
HEC-RAS study Little Calf Creek.prj: Little Calf Creek Base Level Engineering

--- Little Calf Creek.g01 (geometry) --- (continued)

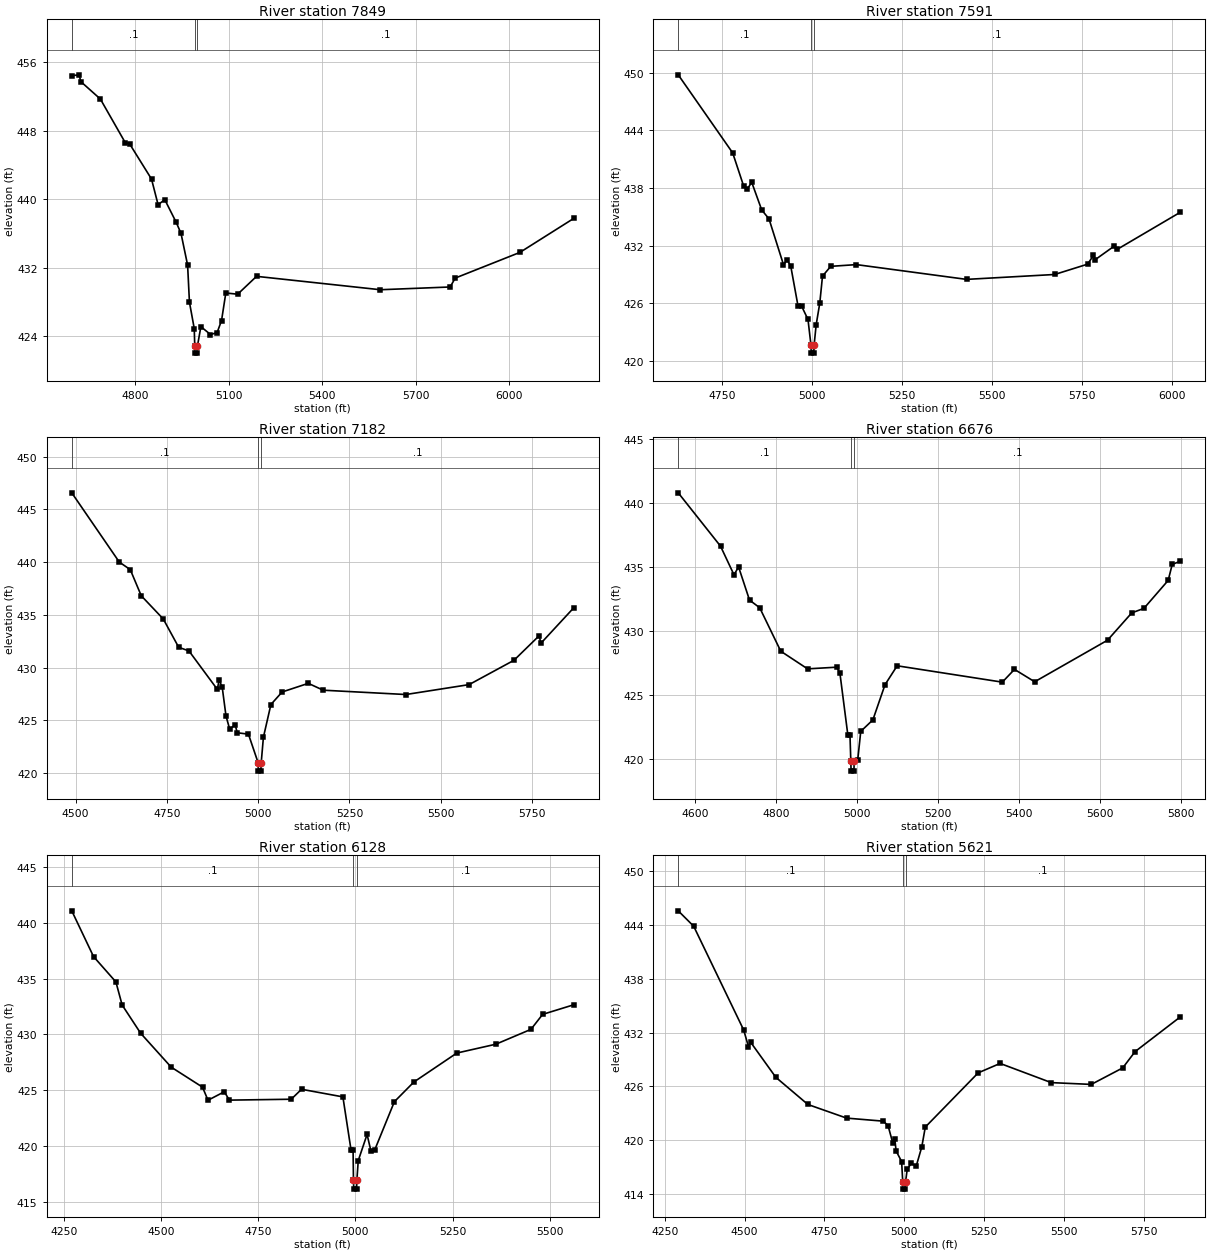
Type RM Length L Ch R = 1 ,7849    ,258,258,258
BEGIN DESCRIPTION:
Mapping XS f47c0cd1
END DESCRIPTION:
XS GIS Cut Line= 4
       2012800.8     13445797.83      2012878.93     13445567.77
       2012750.9     13445359.43      2012538.22     13444254.83
#Sta/Elev= 30
  4596.1   454.4  4619.8   454.5  4625.1  453.71  4687.9  451.68  4768.1  446.58
  4782.1  446.44  4852.2  442.35  4873.4  439.35  4894.7  439.96  4931.4  437.31
  4946.9  436.02  4968.1  432.32    4974     428  4989.4  424.93  4991.1  422.86
  4991.8  422.06  4998.8  422.06  4999.6  422.86  5010.7  425.15  5041.6  424.23
  5062.8  424.45  5077.1  425.86  5090.8  429.07  5128.9  428.93  5189.5  431.01
  5587.1  429.45  5811.2  429.77  5827.6  430.81  6035.2   433.8  6208.5  437.77
#Mann= 3 ,-1 , 0
  4596.1      .1       0  4991.1     .07       0  4999.6      .1       0
Bank Sta=4991.1,4999.6
XS Rating Curve= 0 ,0
Exp/Cntr=0.3,0.1

Type RM Length L Ch R = 1 ,7591    ,409,409,409
BEGIN DESCRIPTION:
Little Calf Creek 10.0
END DESCRIPTION:
XS GIS Cut Line= 3
      2012975.01     13445675.04        2012925.       13445275.
      2012733.54     13444302.62
#Sta/Elev= 30
  4628.5   449.8  4779.7  441.66  4809.9  438.23    4820  437.88  4832.6  438.59
  4860.3  435.71  4880.5  434.78  4920.8     430  4930.9   430.5    4941  429.84
  4961.1   425.7  4971.2  425.67  4988.8  424.29  4997.2  421.58  4997.9  420.78
  5004.9  420.78  5005.7  421.58  5011.5  423.73  5021.6  426.01  5029.1  428.81
    5052  429.83  5123.4  430.01  5429.1  428.47  5673.7  428.98  5765.5  430.06
  5781.5  430.98  5786.6  430.53    5838  431.91    5847  431.59  6022.7  435.47
#Mann= 3 ,-1 , 0
  4628.5      .1       0  4997.2     .07       0  5005.7      .1       0
Bank Sta=4997.2,5005.7
XS Rating Curve= 0 ,0
Exp/Cntr=0.3,0.1

Type RM Length L Ch R = 1 ,7182    ,506,506,506
BEGIN DESCRIPTION:
Little Calf Creek 9.0
END DESCRIPTION:
XS GIS Cut Line= 3
      2013254.37     13445654.57      2013286.92     13445287.82
      2013069.96     13444304.97
#Sta/Elev= 30
  4489.7  446.58  4619.8  440.01  4649.9  439.29    4680  436.81  4740.2  434.61
  4782.5  431.92  4810.5  431.58  4888.2  427.93  4893.3  428.84  4901.7  428.11
    4912   425.4  4922.2  424.14    4937  424.58  4942.7  423.81  4973.4  423.68
  4999.9  420.97  5000.6  420.17  5007.6  420.17  5008.4  420.97  5014.4  423.38
  5034.9  426.49  5065.6  427.68  5137.3   428.5  5178.2  427.85  5404.5  427.44
  5577.6  428.38  5700.5  430.69  5769.2  433.01  5774.4  432.31  5864.4  435.68
#Mann= 3 ,-1 , 0
  4489.7      .1       0  4999.9     .07       0  5008.4      .1       0
Bank Sta=4999.9,5008.4
XS Rating Curve= 0 ,0
Exp/Cntr=0.3,0.1

Type RM Length L Ch R = 1 ,6676    ,548,548,548
BEGIN DESCRIPTION:
Little Calf Creek 8.0
END DESCRIPTION:
XS GIS Cut Line= 3
      2013449.68     13445648.07        2013575.       13445225.
        2013575.     13444425.04
#Sta/Elev= 30
  4558.3  440.79  4662.8  436.62  4696.1  434.38  4707.5  434.99  4734.5   432.4
  4759.7   431.8  4811.8   428.4    4878  427.02  4949.7  427.15  4957.8  426.73
  4977.7  421.82  4982.9  421.82  4984.9  419.82  4985.6  419.02  4992.6  419.02
  4993.4  419.82    5002  419.89  5009.5  422.13  5039.5  423.03  5069.5  425.78
  5099.5  427.26  5359.5  425.98  5389.5  426.98  5439.5  426.01  5619.5  429.26
  5679.5   431.4  5709.5  431.75  5769.5  433.94  5779.5  435.19  5799.5  435.44
#Mann= 3 ,-1 , 0
  4558.3      .1       0  4984.9     .07       0  4993.4      .1       0
Bank Sta=4984.9,4993.4
XS Rating Curve= 0 ,0
Exp/Cntr=0.3,0.1

Type RM Length L Ch R = 1 ,6128    ,507,507,507
BEGIN DESCRIPTION:
Little Calf Creek 7.0
END DESCRIPTION:
XS GIS Cut Line= 3
      2013794.73     13445828.19        2014025.       13445125.
        2014075.       13444575.
#Sta/Elev= 30
  4270.1  441.06  4326.1  436.97  4383.7   434.7  4399.7  432.64  4447.4  430.11
    4526  427.08  4606.6  425.29  4620.7  424.12  4662.8  424.88  4675.6  424.13
  4834.9  424.21  4861.4   425.1  4967.9  424.42  4988.8  419.68  4994.1  419.66
  4995.1  416.97  4995.9  416.17  5003.1  416.17  5003.9  416.97  5007.4  418.72
  5030.1  421.06  5040.2  419.56  5050.2  419.71  5100.4  423.99  5150.6  425.75
  5261.1  428.34  5361.5  429.13  5451.9  430.46    5482   431.8  5562.3  432.66
#Mann= 3 ,-1 , 0
  4270.1      .1       0  4995.1     .07       0  5003.9      .1       0
Bank Sta=4995.1,5003.9
XS Rating Curve= 0 ,0
Exp/Cntr=0.3,0.1

Type RM Length L Ch R = 1 ,5621    ,478,478,478
BEGIN DESCRIPTION:
Little Calf Creek 6.0
END DESCRIPTION:
XS GIS Cut Line= 3
      2013870.66     13445977.96        2014275.       13445425.
      2014649.75     13444621.63
#Sta/Elev= 30
  4292.4  445.59  4340.8  443.87  4497.5  432.28  4512.2  430.44  4519.1  430.93
  4597.9  427.02  4698.3  423.99  4819.5  422.47  4934.6  422.13  4949.2  421.62
  4963.9   419.7  4970.1  420.19  4974.3  418.81  4991.6  417.63  4995.1  415.35
  4995.9  414.55  5003.1  414.55  5003.9  415.35    5009  416.74  5021.6  417.43
  5037.3  417.12  5054.7  419.26  5065.7  421.47  5231.3  427.52  5299.9  428.57
  5459.9  426.43  5585.2  426.23  5683.6  428.07  5722.4  429.89  5863.9  433.76
#Mann= 3 ,-1 , 0
  4292.4      .1       0  4995.1     .07       0  5003.9      .1       0
Bank Sta=4995.1,5003.9
XS Rating Curve= 0 ,0
Exp/Cntr=0.3,0.1

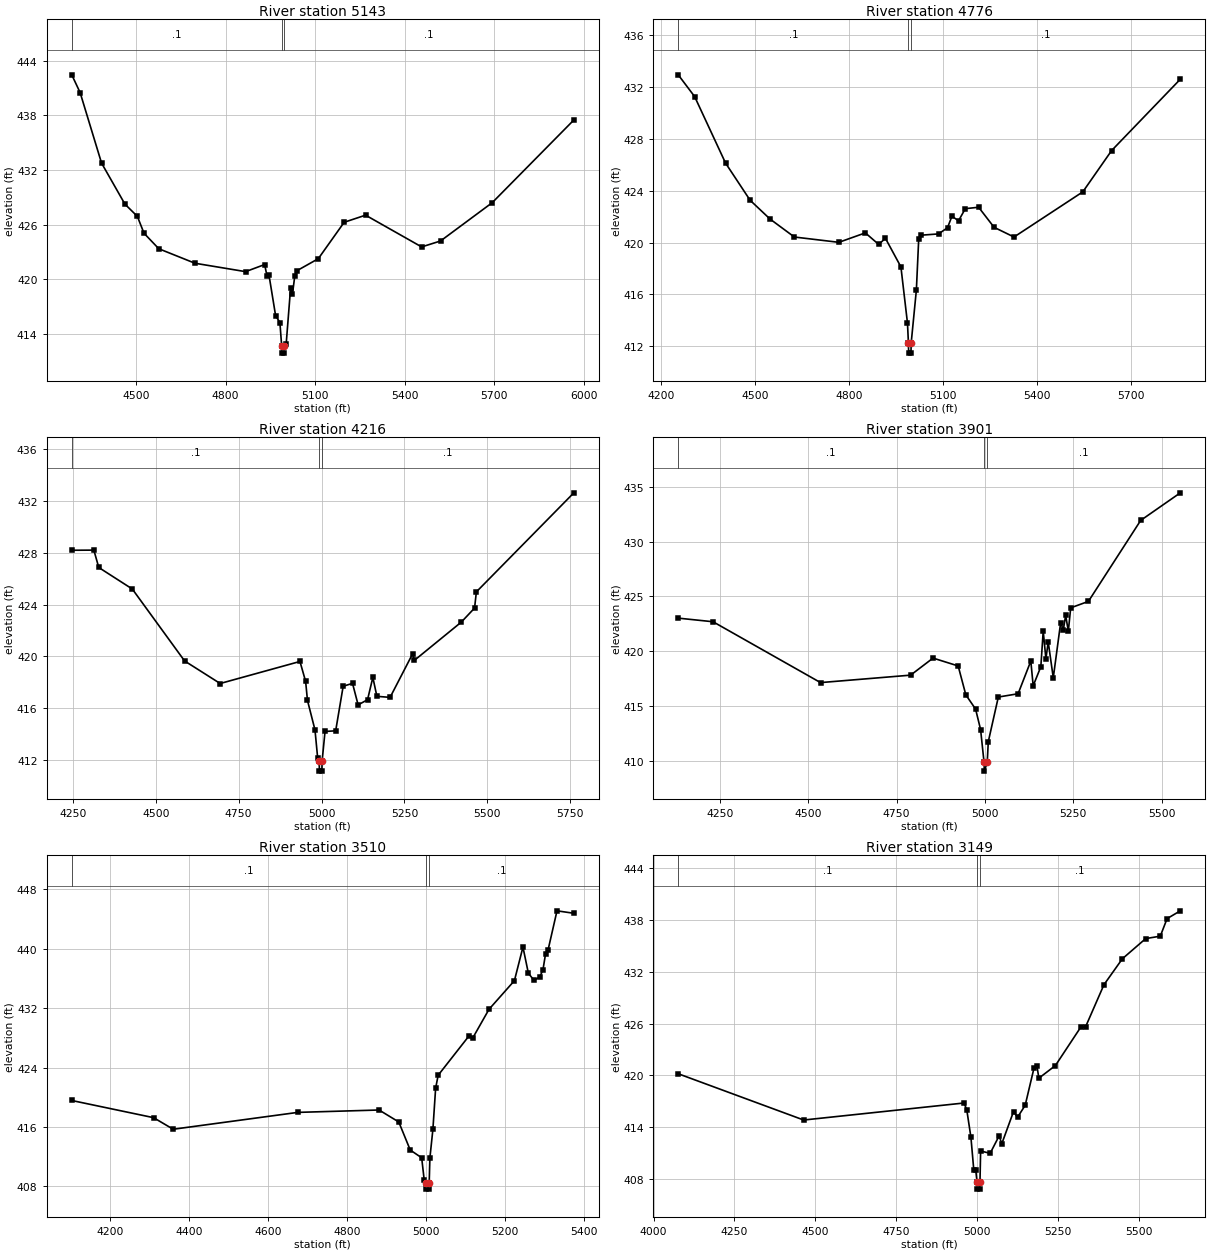
Type RM Length L Ch R = 1 ,5143    ,367,367,367
BEGIN DESCRIPTION:
Little Calf Creek 5.0
END DESCRIPTION:
XS GIS Cut Line= 3
      2014175.02     13446074.97        2014625.       13445525.
      2015174.99     13444725.02
#Sta/Elev= 30
  4284.9  442.43  4312.9  440.48  4384.6  432.76  4462.9  428.26  4504.5  426.92
  4526.8  425.07  4576.3  423.37  4697.6  421.78    4867  420.86  4930.9  421.64
  4938.8  420.35  4945.3   420.5  4967.5  416.04  4981.9  415.28  4987.8  412.73
  4988.6  411.93  4995.9  411.93  4996.7  412.73  5002.9  412.92  5017.8   419.1
  5023.9  418.38  5031.9  420.43  5038.8  420.96  5110.5  422.28  5197.1  426.27
  5268.8  427.05  5456.6  423.57  5519.8  424.22    5693  428.42  5966.3  437.48
#Mann= 3 ,-1 , 0
  4284.9      .1       0  4987.8     .07       0  4996.7      .1       0
Bank Sta=4987.8,4996.7
XS Rating Curve= 0 ,0
Exp/Cntr=0.3,0.1

Type RM Length L Ch R = 1 ,4776    ,560,560,560
BEGIN DESCRIPTION:
Mapping XS 1a1bd676
END DESCRIPTION:
XS GIS Cut Line= 2
      2014441.16     13446154.69      2015520.48     13444971.26
#Sta/Elev= 30
  4255.4  432.96  4307.7  431.28  4406.4  426.14  4484.7  423.27  4548.2  421.82
  4625.9  420.43  4767.8  420.02  4852.3  420.75  4894.8  419.86  4916.4  420.33
  4965.8  418.12  4986.7  413.78  4989.7  412.26  4990.5  411.46  4997.8  411.46
  4998.6  412.26  5015.1  416.34  5022.5  420.25  5029.3  420.57    5086  420.67
  5114.4  421.15  5128.6  422.04  5149.5  421.68  5171.2  422.62  5213.7  422.73
    5263  421.18  5326.6  420.43  5546.1  423.92    5638  427.11  5857.1  432.62
#Mann= 3 ,-1 , 0
  4255.4      .1       0  4989.7     .07       0  4998.6      .1       0
Bank Sta=4989.7,4998.6
XS Rating Curve= 0 ,0
Exp/Cntr=0.3,0.1

Type RM Length L Ch R = 1 ,4216    ,315,315,315
BEGIN DESCRIPTION:
Mapping XS ee73c05a
END DESCRIPTION:
XS GIS Cut Line= 3
      2014774.46      13446307.5      2015239.75      13445981.1
      2015648.74     13445128.48
#Sta/Elev= 30
  4246.9  428.19  4313.5   428.2  4328.3  426.86  4429.4   425.2  4587.1  419.65
  4694.4  417.91    4935  419.61  4952.1  418.07  4957.6  416.61  4980.3  414.33
  4988.4  412.16  4992.9  411.95  4993.7  411.15    5001  411.15  5001.9  411.95
  5010.6  414.21  5042.7  414.26  5065.3   417.7  5093.5  417.92  5110.4  416.26
  5138.8  416.66  5154.8  418.38    5167  416.92  5206.8  416.84  5274.7   420.2
  5280.3   419.7  5421.7  422.65  5461.5  423.73    5467  424.98  5760.9  432.62
#Mann= 3 ,-1 , 0
  4246.9      .1       0  4992.9     .07       0  5001.9      .1       0
Bank Sta=4992.9,5001.9
XS Rating Curve= 0 ,0
Exp/Cntr=0.3,0.1

Type RM Length L Ch R = 1 ,3901    ,391,391,391
BEGIN DESCRIPTION:
Mapping XS d37c87dc
END DESCRIPTION:
XS GIS Cut Line= 2
      2015024.49     13446543.59      2015968.95     13445481.07
#Sta/Elev= 30
  4131.6  423.01  4230.1  422.68  4534.5  417.12  4789.6   417.8  4853.1  419.36
  4924.2  418.64  4945.9     416  4973.5   414.7  4987.7  412.83  4997.5  409.83
  4998.3  409.03  5006.5  409.83  5009.5  411.72  5037.9   415.8  5093.9   416.1
  5129.9  419.09  5136.6  416.83  5158.3  418.57    5165  421.82  5172.6   419.3
  5179.2  420.83  5193.5  417.56  5214.4   422.6  5221.9  421.93  5228.6  423.27
  5236.1  421.81  5242.8  423.95    5293  424.54    5441  431.94  5553.2  434.46
#Mann= 3 ,-1 , 0
  4131.6      .1       0  4997.5     .07       0  5006.5      .1       0
Bank Sta=4997.5,5006.5
XS Rating Curve= 0 ,0
Exp/Cntr=0.3,0.1

Type RM Length L Ch R = 1 ,3510    ,361,361,361
BEGIN DESCRIPTION:
Mapping XS 627d7da8
END DESCRIPTION:
XS GIS Cut Line= 2
      2015213.25     13446534.08      2016216.72      13445756.3
#Sta/Elev= 30
    4104  419.57  4310.8  417.26  4360.5   415.7  4675.6  417.97  4881.1  418.29
  4930.9  416.68  4959.9   412.9  4988.8  411.86  4995.2  408.86  4998.8  408.44
  4999.7  407.64    5007  407.64  5007.8  408.44  5009.6  411.84  5017.2   415.7
  5024.1  421.23  5030.5  422.97  5109.2  428.31  5117.4  427.93    5159  431.84
  5223.3   435.7  5244.9  440.22  5258.6   436.7  5273.1  435.73  5287.6  436.22
  5295.5  437.16  5302.1  439.32  5308.4  439.83    5331   445.1  5373.6  444.77
#Mann= 3 ,-1 , 0
    4104      .1       0  4998.8     .07       0  5007.8      .1       0
Bank Sta=4998.8,5007.8
XS Rating Curve= 0 ,0
Exp/Cntr=0.3,0.1

Type RM Length L Ch R = 1 ,3149    ,481,481,481
BEGIN DESCRIPTION:
Mapping XS 4488584c
END DESCRIPTION:
XS GIS Cut Line= 3
        2015182.      13446579.2      2015758.42     13446485.45
      2016563.98     13445947.25
#Sta/Elev= 30
  4076.4  420.19  4464.4  414.84  4960.6  416.81    4969  415.97  4981.6  412.85
  4990.6  409.01  4996.6  409.02  5000.6  407.65  5001.4  406.85  5008.7  406.85
  5009.6  407.65  5011.6  411.26  5041.1  410.99  5068.7     413  5077.2  412.11
  5113.3  415.81  5125.8  415.16  5149.4  416.54  5176.8  420.87  5185.5  421.14
  5191.8  419.68  5242.9  421.14    5321  425.56    5336   425.6  5393.1  430.49
  5450.1  433.49  5522.2  435.82  5567.3   436.1  5588.3  438.13  5629.2  439.03
#Mann= 3 ,-1 , 0
  4076.4      .1       0  5000.6     .07       0  5009.6      .1       0
Bank Sta=5000.6,5009.6
XS Rating Curve= 0 ,0
Exp/Cntr=0.3,0.1

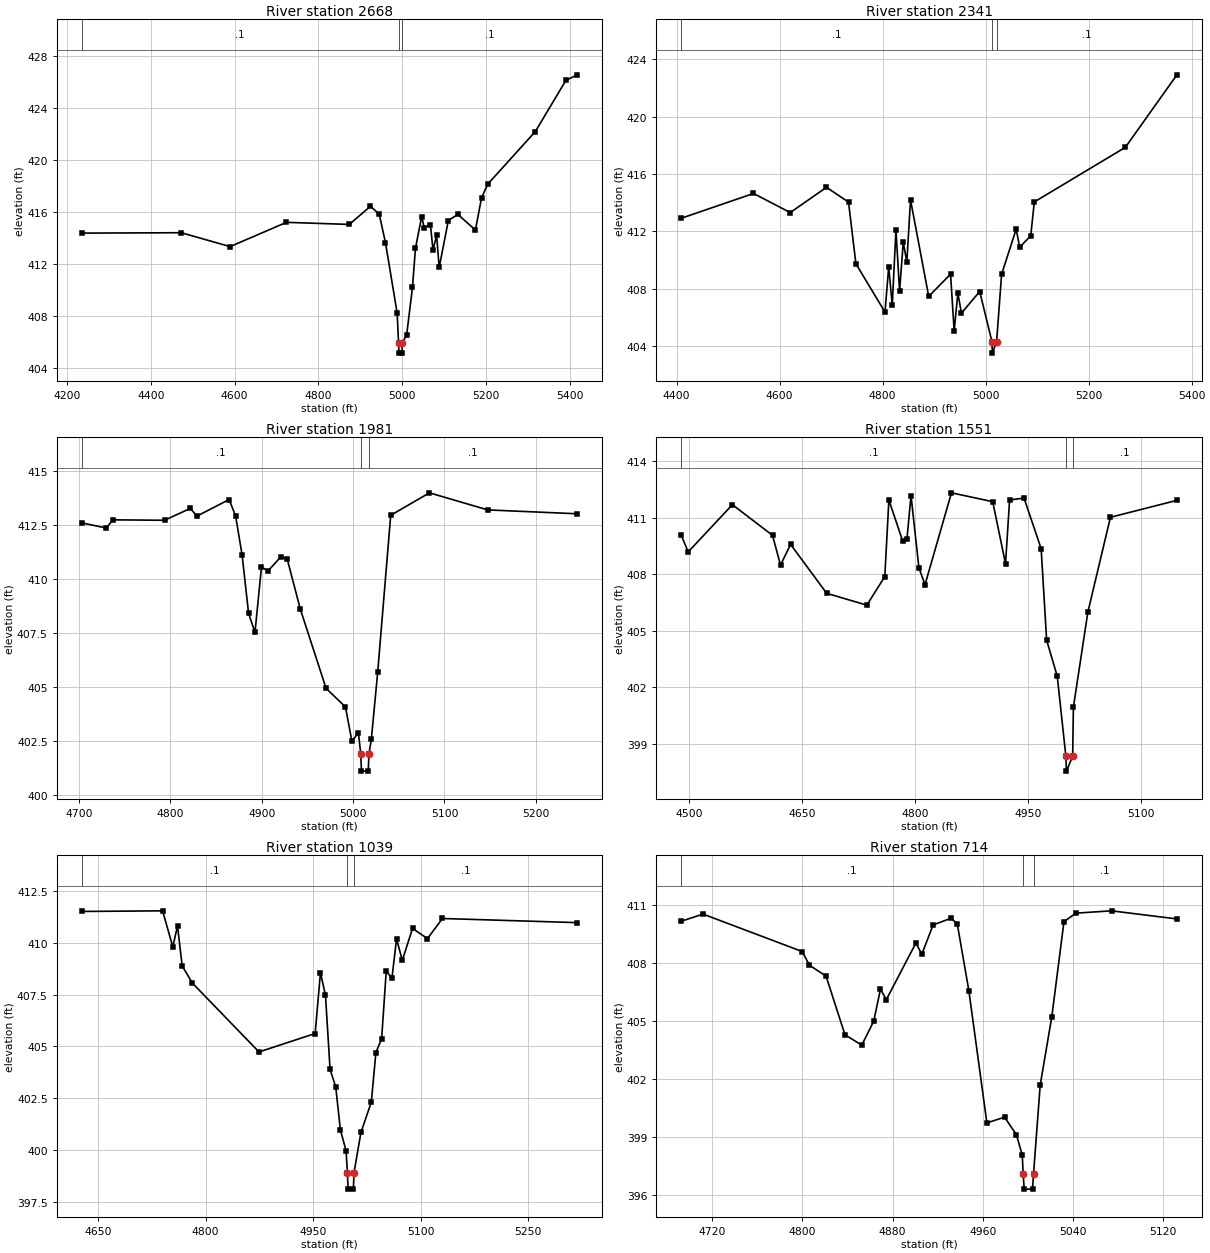
Type RM Length L Ch R = 1 ,2668    ,327,327,327
BEGIN DESCRIPTION:
Mapping XS 20d3e88c
END DESCRIPTION:
XS GIS Cut Line= 3
      2015677.12       13446872.      2016199.71     13446644.56
      2016551.05     13446142.64
#Sta/Elev= 30
  4235.4  414.37    4473   414.4  4589.4  413.33  4723.9   415.2  4873.8  415.04
  4924.3  416.44  4945.3  415.82  4960.1  413.63  4987.9  408.21  4991.3  405.92
  4992.2  405.12  4999.5  405.12  5000.3  405.92  5010.6  406.52  5024.5  410.19
  5031.6   413.2  5046.4  415.64  5052.5  414.79  5067.3  415.02  5073.4  413.08
  5082.1  414.19  5088.2  411.72    5110  415.34  5132.7  415.81  5174.6  414.61
  5189.4  417.11  5204.2  418.15  5317.6   422.2  5390.7  426.15    5418  426.57
#Mann= 3 ,-1 , 0
  4235.4      .1       0  4991.3     .07       0  5000.3      .1       0
Bank Sta=4991.3,5000.3
XS Rating Curve= 0 ,0
Exp/Cntr=0.3,0.1

Type RM Length L Ch R = 1 ,2341    ,360,360,360
BEGIN DESCRIPTION:
Mapping XS aff570dc
END DESCRIPTION:
XS GIS Cut Line= 3
      2016152.84     13447010.88       2016425.4     13446778.24
      2016843.84     13446342.45
#Sta/Elev= 30
  4408.9  412.92  4549.3  414.65  4620.7  413.32    4691  415.08  4733.8  414.05
  4748.1  409.75  4804.6  406.37  4811.8  409.52  4818.7  406.87  4825.9  412.11
  4832.9  407.84  4840.1  411.25    4847  409.87  4854.2   414.2  4889.5  407.47
  4931.9  409.02  4938.9  405.06  4946.1   407.7    4953   406.3  4988.5  407.81
  5012.3  404.31  5013.1  403.51  5021.3  404.31    5031  409.01  5059.3  412.16
  5066.2   410.9  5087.6   411.7  5094.5  414.06  5271.3  417.87  5371.4  422.93
#Mann= 3 ,-1 , 0
  4408.9      .1       0  5012.3     .07       0  5021.3      .1       0
Bank Sta=5012.3,5021.3
XS Rating Curve= 0 ,0
Exp/Cntr=0.3,0.1

Type RM Length L Ch R = 1 ,1981    ,430,430,430
BEGIN DESCRIPTION:
Mapping XS b13ac248
END DESCRIPTION:
XS GIS Cut Line= 2
       2016454.9     13447023.05      2016841.02     13446642.12
#Sta/Elev= 30
  4703.1  412.59  4730.1  412.35  4737.1  412.73  4793.7  412.71    4822  413.26
  4829.1   412.9  4864.4  413.67  4871.5  412.91  4878.6   411.1  4885.7   408.4
  4892.7  407.52  4899.8  410.55  4906.9  410.36    4921  411.02    4928  410.91
  4942.2  408.61  4970.5  404.93  4991.7  404.07  4998.7  402.49  5005.9  402.87
  5008.4   401.9  5009.2   401.1  5016.6   401.1  5017.4   401.9    5020  402.57
    5027   405.7  5041.2  412.94  5083.6  413.98  5147.3  413.19  5245.5  413.01
#Mann= 3 ,-1 , 0
  4703.1      .1       0  5008.4     .07       0  5017.4      .1       0
Bank Sta=5008.4,5017.4
XS Rating Curve= 0 ,0
Exp/Cntr=0.3,0.1

Type RM Length L Ch R = 1 ,1551    ,512,512,512
BEGIN DESCRIPTION:
Mapping XS 3fde0717
END DESCRIPTION:
XS GIS Cut Line= 3
      2016533.06     13447094.21      2016895.89     13446944.91
      2016991.36     13446696.68
#Sta/Elev= 30
  4489.4  410.08  4498.7  409.19  4557.4   411.7  4610.7  410.07  4621.3  408.49
  4634.7  409.59  4682.6  406.99  4735.9  406.36  4759.8  407.88  4765.2  411.95
  4783.5  409.77  4789.2  409.88  4794.6  412.18  4805.1  408.34  4813.2  407.45
  4848.3  412.33  4903.1  411.86  4920.1  408.56  4925.5  411.95  4944.7  412.05
  4967.4  409.36  4974.7   404.5  4988.8  402.58  5000.2  398.34    5001  397.54
  5009.3  398.34  5010.2  400.93  5029.4  405.98  5059.4  411.03  5147.7  411.93
#Mann= 3 ,-1 , 0
  4489.4      .1       0  5000.2     .07       0  5009.3      .1       0
Bank Sta=5000.2,5009.3
XS Rating Curve= 0 ,0
Exp/Cntr=0.3,0.1

Type RM Length L Ch R = 1 ,1039    ,325,325,325
BEGIN DESCRIPTION:
Mapping XS 697bab78
END DESCRIPTION:
XS GIS Cut Line= 2
      2016696.27     13447344.19      2017233.46     13446909.24
#Sta/Elev= 30
  4627.3  411.51  4740.1  411.54  4754.3   409.8  4760.9  410.81  4767.4  408.88
  4781.7  408.05  4874.5  404.73  4952.8  405.62  4960.2  408.56  4967.2  407.46
  4973.6  403.89  4981.5  403.04    4988  400.97  4995.9  399.96  4997.8  398.91
  4998.7  398.11  5006.1  398.11    5007  398.91  5016.7  400.85  5031.1  402.31
  5037.5   404.7  5045.5  405.36  5051.9  408.63  5059.9   408.3  5066.3  410.19
  5074.3  409.15  5088.6  410.69  5109.4   410.2  5130.3  411.17  5318.5  410.97
#Mann= 3 ,-1 , 0
  4627.3      .1       0  4997.8     .07       0    5007      .1       0
Bank Sta=4997.8,5007
XS Rating Curve= 0 ,0
Exp/Cntr=0.3,0.1

Type RM Length L Ch R = 1 ,714     ,367,367,367
BEGIN DESCRIPTION:
Mapping XS a61f0aa6
END DESCRIPTION:
XS GIS Cut Line= 2
      2017163.25      13447366.8      2017303.88     13446950.09
#Sta/Elev= 30
  4692.4  410.16  4711.8  410.53  4799.8  408.59  4806.2  407.88  4820.9  407.32
  4837.7  404.28  4852.6  403.74  4863.2  404.98  4869.2  406.64  4874.4   406.1
  4900.6  409.03  4905.9  408.45  4915.9  409.97  4932.1  410.32  4937.4     410
  4947.6  406.57  4963.6  399.71  4979.3  400.01  4989.8   399.1    4995  398.04
  4995.8  397.08  4996.7  396.28  5004.1  396.28    5005  397.08  5010.9  401.67
  5021.2  405.21    5032  410.14  5042.6  410.58  5074.2   410.7  5132.2  410.28
#Mann= 3 ,-1 , 0
  4692.4      .1       0  4995.8     .07       0    5005      .1       0
Bank Sta=4995.8,5005
XS Rating Curve= 0 ,0
Exp/Cntr=0.3,0.1

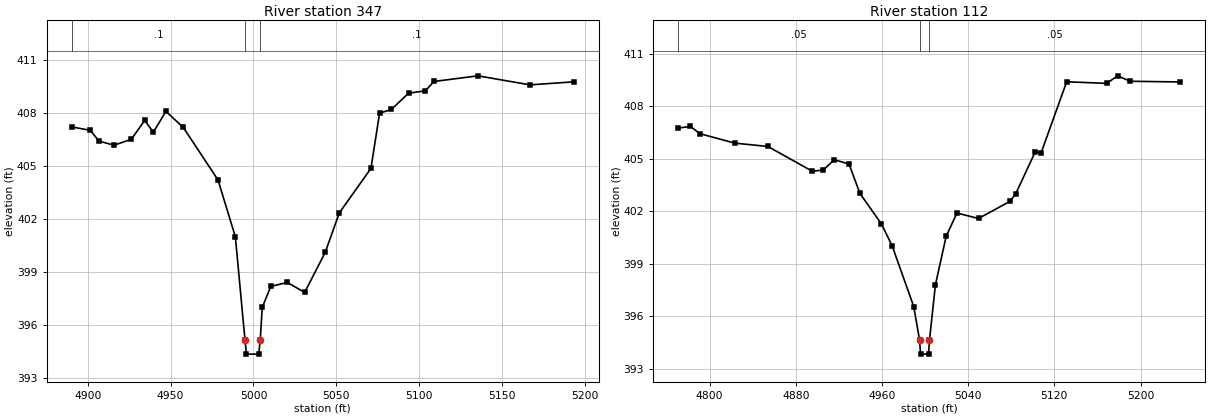
Type RM Length L Ch R = 1 ,347     ,235,235,235
BEGIN DESCRIPTION:
Mapping XS bcdd96c6
END DESCRIPTION:
XS GIS Cut Line= 2
       2017406.3     13447389.36      2017494.77     13447099.67
#Sta/Elev= 30
  4890.4   407.2  4901.6  407.01  4906.8   406.4  4915.9  406.17  4926.3   406.5
  4934.4  407.57  4939.6   406.9  4947.2  408.08  4957.7  407.17  4978.6  404.21
  4989.1  400.99  4994.9  395.16  4995.8  394.36  5003.2  394.36  5004.1  395.16
  5005.3     397  5010.5  398.19  5020.4  398.41  5030.9  397.85  5043.3  400.11
  5051.8  402.34  5070.9  404.86  5076.1  407.98  5083.2  408.19  5093.6  409.11
  5103.7  409.24  5108.9  409.77  5135.4  410.09  5166.8  409.58  5193.3  409.75
#Mann= 3 ,-1 , 0
  4890.4      .1       0  4994.9     .07       0  5004.1      .1       0
Bank Sta=4994.9,5004.1
XS Rating Curve= 0 ,0
Exp/Cntr=0.3,0.1

Type RM Length L Ch R = 1 ,112     ,0,0,0
BEGIN DESCRIPTION:
Little Calf Creek 1.0
END DESCRIPTION:
XS GIS Cut Line= 4
      2017503.97     13447415.39      2017652.83     13447380.67
      2017659.78     13447248.73       2017589.3       13447082.
#Sta/Elev= 30
  4770.9  406.75  4782.2  406.84    4791  406.43  4823.3  405.89  4854.1   405.7
  4895.2  404.29  4905.4  404.35  4915.7  404.94  4929.4   404.7  4939.5  403.02
  4959.5  401.28  4969.5  400.02  4989.5  396.56  4994.9  394.65  4995.8  393.85
  5003.2  393.85  5004.1  394.65  5009.6   397.8  5019.6  400.58  5029.6   401.9
  5049.6  401.59  5078.6  402.56    5084  402.98  5102.3   405.4  5107.7  405.33
  5131.4  409.39  5168.5   409.3  5178.8  409.73  5190.2  409.42  5236.9  409.38
#Mann= 3 ,-1 , 0
  4770.9     .05       0  4994.9     .03       0  5004.1     .05       0
Bank Sta=4994.9,5004.1
XS Rating Curve= 0 ,0
Exp/Cntr=0.3,0.1
LCMann Table=0

Chan Stop Cuts=-1
Use User Specified Reach Order=0
Composite Channel Slope=5