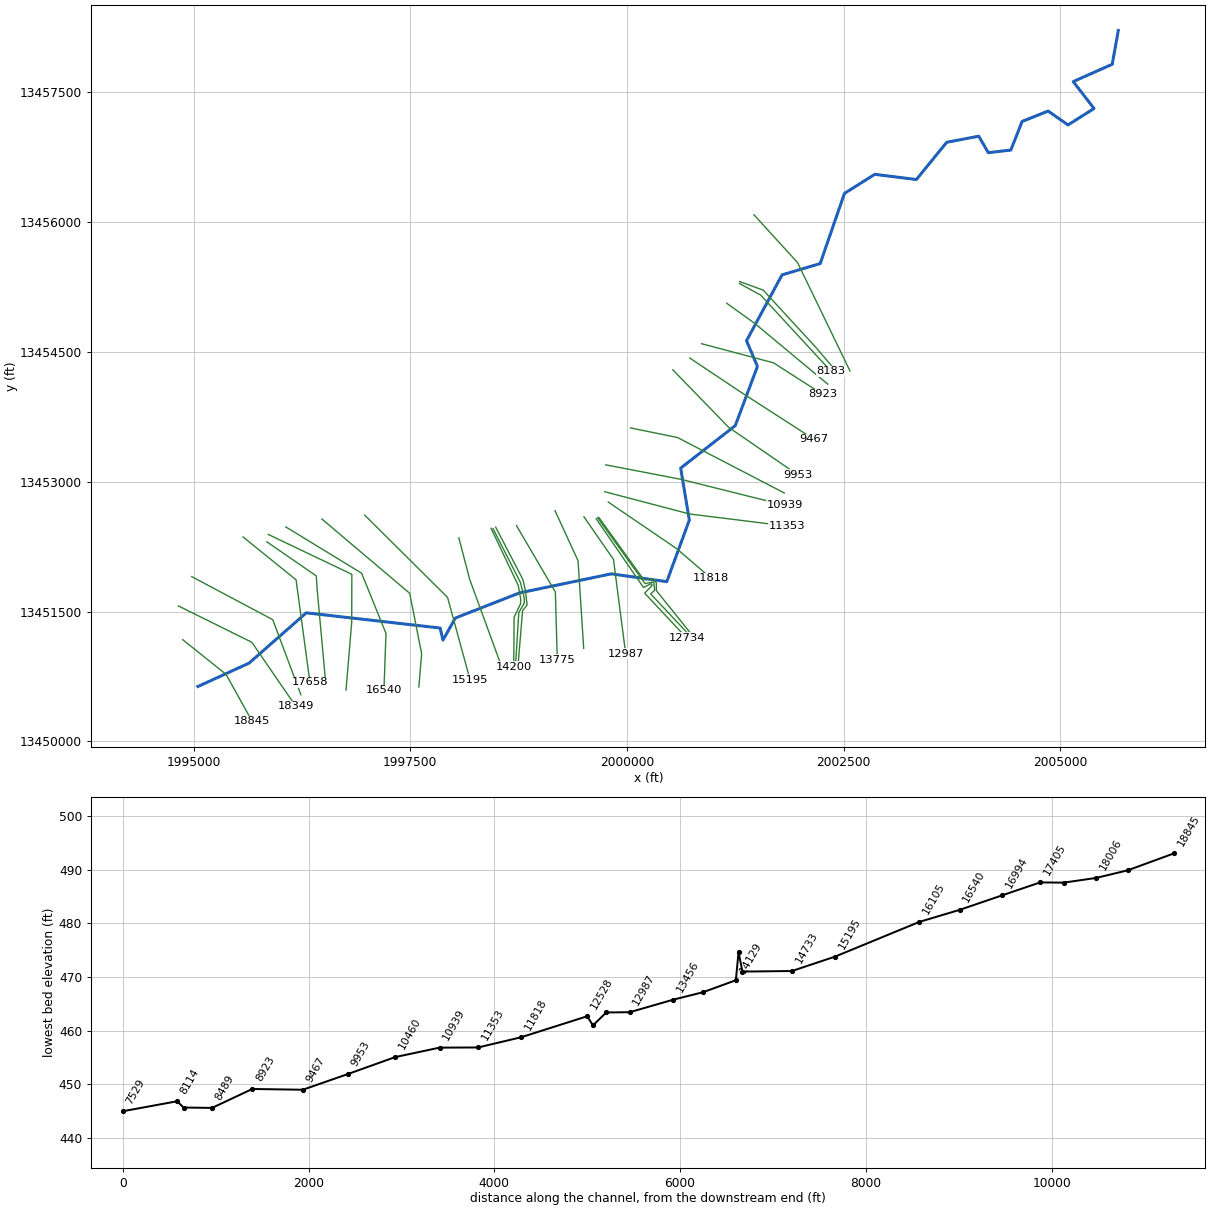
--- Live Oak Creek 2.prj (project) ---

Proj Title=Live Oak Creek 2 Base Level Engineering
Current Plan=p01
Default Exp/Contr=0.3,0.1
English Units
Geom File=g01
Flow File=f01
Plan File=p01
BEGIN DESCRIPTION:
Live Oak Creek 2
END DESCRIPTION:

--- Live Oak Creek 2.p01 (plan) ---

Plan Title=Multiple Run
Short Identifier=Multiple
Geom File=g01
Flow File=f01
Subcritical Flow
K Sum by GR= 0
Std Step Tol= 0.01
Critical Tol= 0.01
Num of Std Step Trials= 20
Max Error Tol= 0.3
Flow Tol Ratio= 0.001
Split Flow NTrial= 30
Split Flow Tol= 0.02
Split Flow Ratio= 0.02
Log Output Level= 0
Friction Slope Method= 1
Unsteady Friction Slope Method= 2
Unsteady Bridges Friction Slope Method= 1
Parabolic Critical Depth
Global Vel Dist=  1 , 1 , 1
Global Log Level= 0
CheckData=True
Encroach Param= -1, 0, 0, 0
BEGIN DESCRIPTION:
Multiple Run
END DESCRIPTION:

--- Live Oak Creek 2.f01 (steady flow) ---

Flow Title=Multiple
Number of Profiles=7
Profile Names=10-year,25-year,50-year,1pct_min,100-year,1pct_plu,500-year
River Rch & RM= Live Oak Creek 2,Reach-1,18845
     154     208     252     152     304     606     447
River Rch & RM= Live Oak Creek 2,Reach-1,17658
     254     353     435     267     533    1063     813
River Rch & RM= Live Oak Creek 2,Reach-1,12591
     316     444     550     339     677    1350    1042
River Rch & RM= Live Oak Creek 2,Reach-1,4721
     358     504     626     387     772    1540    1193
Boundary for River Rch & Prof#=Live Oak Creek 2,Reach-1,1
Up Type=0
Dn Type=3
Dn Slope=0.005
Boundary for River Rch & Prof#=Live Oak Creek 2,Reach-1,2
Up Type=0
Dn Type=3
Dn Slope=0.005
Boundary for River Rch & Prof#=Live Oak Creek 2,Reach-1,3
Up Type=0
Dn Type=3
Dn Slope=0.005
Boundary for River Rch & Prof#=Live Oak Creek 2,Reach-1,4
Up Type=0
Dn Type=3
Dn Slope=0.005
Boundary for River Rch & Prof#=Live Oak Creek 2,Reach-1,5
Up Type=0
Dn Type=3
Dn Slope=0.005
Boundary for River Rch & Prof#=Live Oak Creek 2,Reach-1,6
Up Type=0
Dn Type=3
Dn Slope=0.005
Boundary for River Rch & Prof#=Live Oak Creek 2,Reach-1,7
Up Type=0
Dn Type=3
Dn Slope=0.005

--- Live Oak Creek 2.g01 (geometry) ---

Geom Title=Existing Conditions

River Reach=Live Oak Creek 2,Reach-1
Reach XY= 30
      1995050.80     13450634.54      1995640.80     13450904.54
      1996300.80     13451484.54      1997845.61     13451309.19
      1997877.90     13451169.61      1998020.80     13451424.54
      1998760.83     13451714.50      1999820.80     13451934.54
      2000460.80     13451844.54      2000720.80     13452554.54
      2000620.80     13453154.54      2001250.80     13453644.54
      2001506.90     13454328.06      2001380.80     13454624.54
      2001790.80     13455384.54      2002230.80     13455514.54
      2002510.80     13456324.54      2002860.80     13456544.54
      2003340.80     13456484.54      2003690.80     13456914.54
      2004060.80     13456984.54      2004170.80     13456794.54
      2004430.80     13456824.54      2004560.80     13457154.54
      2004860.80     13457274.54      2005090.80     13457114.54
      2005390.80     13457304.54      2005150.80     13457614.54
      2005600.80     13457814.54      2005670.80     13458204.54

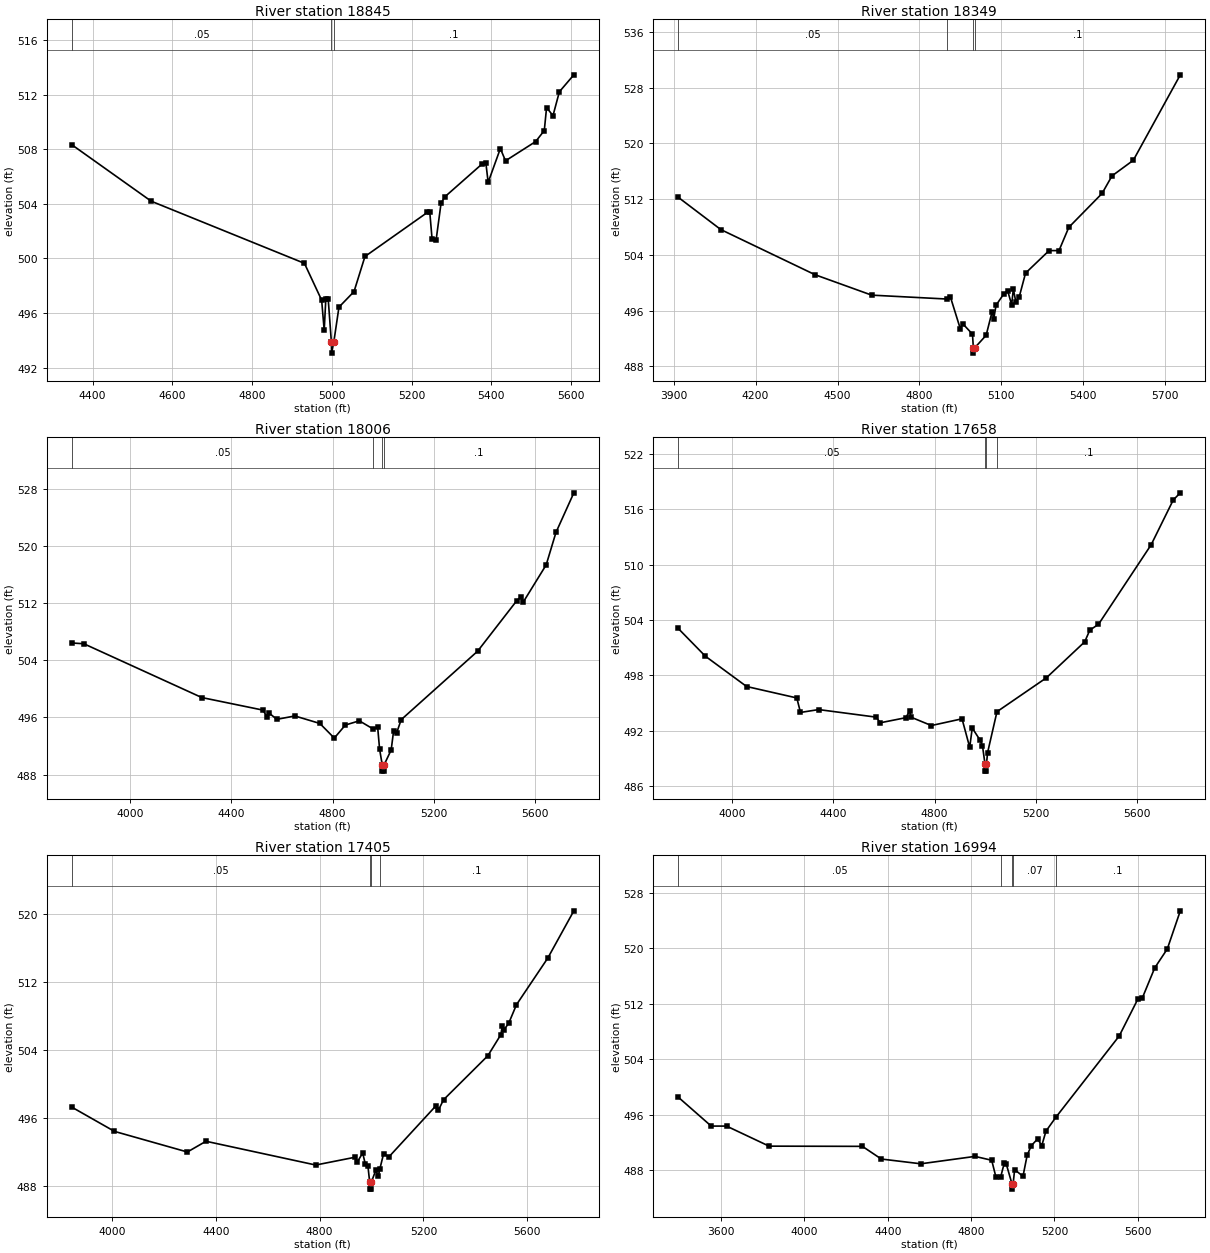
Type RM Length L Ch R = 1,18845,496,496,496
BEGIN DESCRIPTION:
Live Oak Creek 2 26.0
END DESCRIPTION:
XS GIS Cut Line= 3
      1994874.98     13451175.02      1995375.00     13450775.00
      1995675.13     13450233.78
#Sta/Elev= 30
  4347.7  508.33  4547.0  504.19  4931.2  499.64  4974.4  496.94  4980.8  494.73
  4984.8  497.00  4990.9  497.00  4998.8  493.86  4999.3  493.06  5004.8  493.86
  5017.8  496.43  5055.6  497.57  5083.0  500.14  5239.6  503.37  5245.6  503.38
  5251.3  501.43  5261.6  501.38  5273.9  504.05  5283.3  504.51  5376.8  506.92
  5386.3  506.98  5392.0  505.57  5422.6  508.05  5435.5  507.15  5511.1  508.56
  5532.8  509.37  5538.5  511.05  5554.6  510.46  5570.6  512.21  5606.9  513.45
#Mann=3,-1,0
  4347.7    0.05       0  4998.8    0.03       0  5004.8     0.1       0
Bank Sta=4998.8,5004.8
Exp/Cntr=0.3,0.1

Type RM Length L Ch R = 1,18349,343,343,343
BEGIN DESCRIPTION:
Live Oak Creek 2 25.0
END DESCRIPTION:
XS GIS Cut Line= 3
      1994825.33     13451564.08      1995672.94     13451144.83
      1996177.71     13450408.69
#Sta/Elev= 30
  3916.7  512.27  4072.5  507.64  4417.5  501.16  4624.9  498.23  4900.7  497.67
  4913.4  497.94  4949.3  493.42  4958.1  494.14  4994.0  492.63  4997.1  490.71
  4997.6  489.91  5003.1  490.71  5044.0  492.47  5065.8  495.85  5071.8  494.84
  5080.4  496.79  5107.7  498.35  5122.6  498.87  5137.5  496.86  5143.6  499.14
  5152.4  497.30  5165.2  497.99  5188.3  501.39  5274.4  504.62  5310.7  504.62
  5346.7  507.96  5468.4  512.82  5504.8  515.34  5582.8  517.58  5754.9  529.84
#Mann=4,-1,0
  3916.7    0.05       0  4900.7     0.1       0  4997.1    0.07       0
  5003.1     0.1       0
Bank Sta=4997.1,5003.1
Exp/Cntr=0.3,0.1

Type RM Length L Ch R = 1,18006,348,348,348
BEGIN DESCRIPTION:
Live Oak Creek 2 24.0
END DESCRIPTION:
XS GIS Cut Line= 3
      1994978.46     13451902.66      1995913.83     13451405.68
      1996238.90     13450538.83
#Sta/Elev= 30
  3768.7  506.44  3816.4  506.33  4282.9  498.79  4524.7  497.03  4541.0  496.04
  4546.7  496.68  4579.3  495.74  4650.9  496.21  4749.5  495.16  4806.6  493.11
  4850.4  494.94  4905.6  495.53  4960.6  494.38  4978.1  494.63  4985.7  491.56
  4996.5  489.28  4997.0  488.48  5002.0  488.48  5002.5  489.28  5031.5  491.45
  5040.9  494.06  5052.9  493.82  5071.1  495.69  5373.3  505.29  5528.6  512.39
  5544.2  512.91  5553.5  512.16  5644.3  517.38  5683.0  521.93  5753.7  527.48
#Mann=4,-1,0
  3768.7    0.05       0  4960.6     0.1       0  4996.5    0.07       0
  5002.5     0.1       0
Bank Sta=4996.5,5002.5
Exp/Cntr=0.3,0.1

Type RM Length L Ch R = 1,17658,253,253,253
BEGIN DESCRIPTION:
Mapping XS 41f15435
END DESCRIPTION:
XS GIS Cut Line= 3
      1995570.98     13452360.52      1996182.93     13451865.75
      1996343.52     13450680.82
#Sta/Elev= 30
  3787.3  503.07  3894.2  500.07  4057.3  496.78  4255.6  495.54  4270.0  493.97
  4341.9  494.28  4569.0  493.46  4585.1  492.85  4686.0  493.40  4701.3  494.14
  4706.3  493.46  4786.9  492.55  4908.0  493.28  4938.3  490.19  4948.4  492.28
  4978.7  490.99  4988.7  490.38  4998.5  488.41  4999.0  487.61  5004.1  487.61
  5004.6  488.41  5008.9  489.61  5046.0  494.05  5241.0  497.72  5392.4  501.62
  5412.6  502.89  5446.9  503.52  5654.8  512.14  5742.2  517.00  5770.0  517.77
#Mann=4,-1,0
  3787.3    0.05       0  4998.5    0.03       0  5004.6    0.05       0
  5046.0     0.1       0
Bank Sta=4998.5,5004.6
Exp/Cntr=0.3,0.1

Type RM Length L Ch R = 1,17405,411,411,411
BEGIN DESCRIPTION:
Live Oak Creek 2 23.0
END DESCRIPTION:
XS GIS Cut Line= 4
      1995845.57     13452304.10      1996416.35     13451910.71
      1996425.98     13451759.41      1996525.00     13450675.04
#Sta/Elev= 30
  3845.7  497.28  4010.2  494.43  4290.9  492.01  4362.6  493.27  4785.3  490.48
  4935.9  491.39  4946.0  490.87  4966.1  491.89  4976.1  490.61  4986.2  490.41
  4993.1  488.45  4993.6  487.65  4998.7  487.65  4999.2  488.45  5016.3  489.84
  5026.3  489.15  5032.1  490.00  5046.4  491.78  5068.1  491.47  5247.2  497.40
  5257.3  496.89  5277.4  498.14  5448.1  503.31  5498.3  505.79  5503.9  506.83
  5508.9  506.31  5528.4  507.12  5558.5  509.31  5679.0  514.78  5779.4  520.33
#Mann=4,-1,0
  3845.7    0.05       0  4993.1    0.03       0  4999.2    0.05       0
  5032.1     0.1       0
Bank Sta=4993.1,4999.2
Exp/Cntr=0.3,0.1

Type RM Length L Ch R = 1,16994,454,454,454
BEGIN DESCRIPTION:
Live Oak Creek 2 22.0
END DESCRIPTION:
XS GIS Cut Line= 4
      1995861.20     13452390.03      1996826.69     13451929.06
      1996825.00     13451375.00      1996759.31     13450592.70
#Sta/Elev= 30
  3394.9  498.52  3553.1  494.34  3626.7  494.34  3830.8  491.44  4278.5  491.41
  4369.2  489.58  4558.8  488.89  4818.8  489.96  4898.9  489.40  4918.9  487.01
  4941.7  486.95  4958.9  488.97  4968.9  488.85  4995.8  486.03  4996.3  485.23
  5001.9  486.03  5008.9  488.05  5049.0  487.08  5069.0  490.12  5089.1  491.52
  5119.2  492.48  5139.3  491.53  5159.3  493.61  5206.0  495.58  5510.6  507.35
  5600.9  512.73  5621.0  512.80  5681.2  517.20  5741.4  519.93  5803.9  525.44
#Mann=5,-1,0
  3394.9    0.05       0  4941.7    0.07       0  4995.8    0.07       0
  5001.9    0.07       0  5206.0     0.1       0
Bank Sta=4995.8,5001.9
Exp/Cntr=0.3,0.1

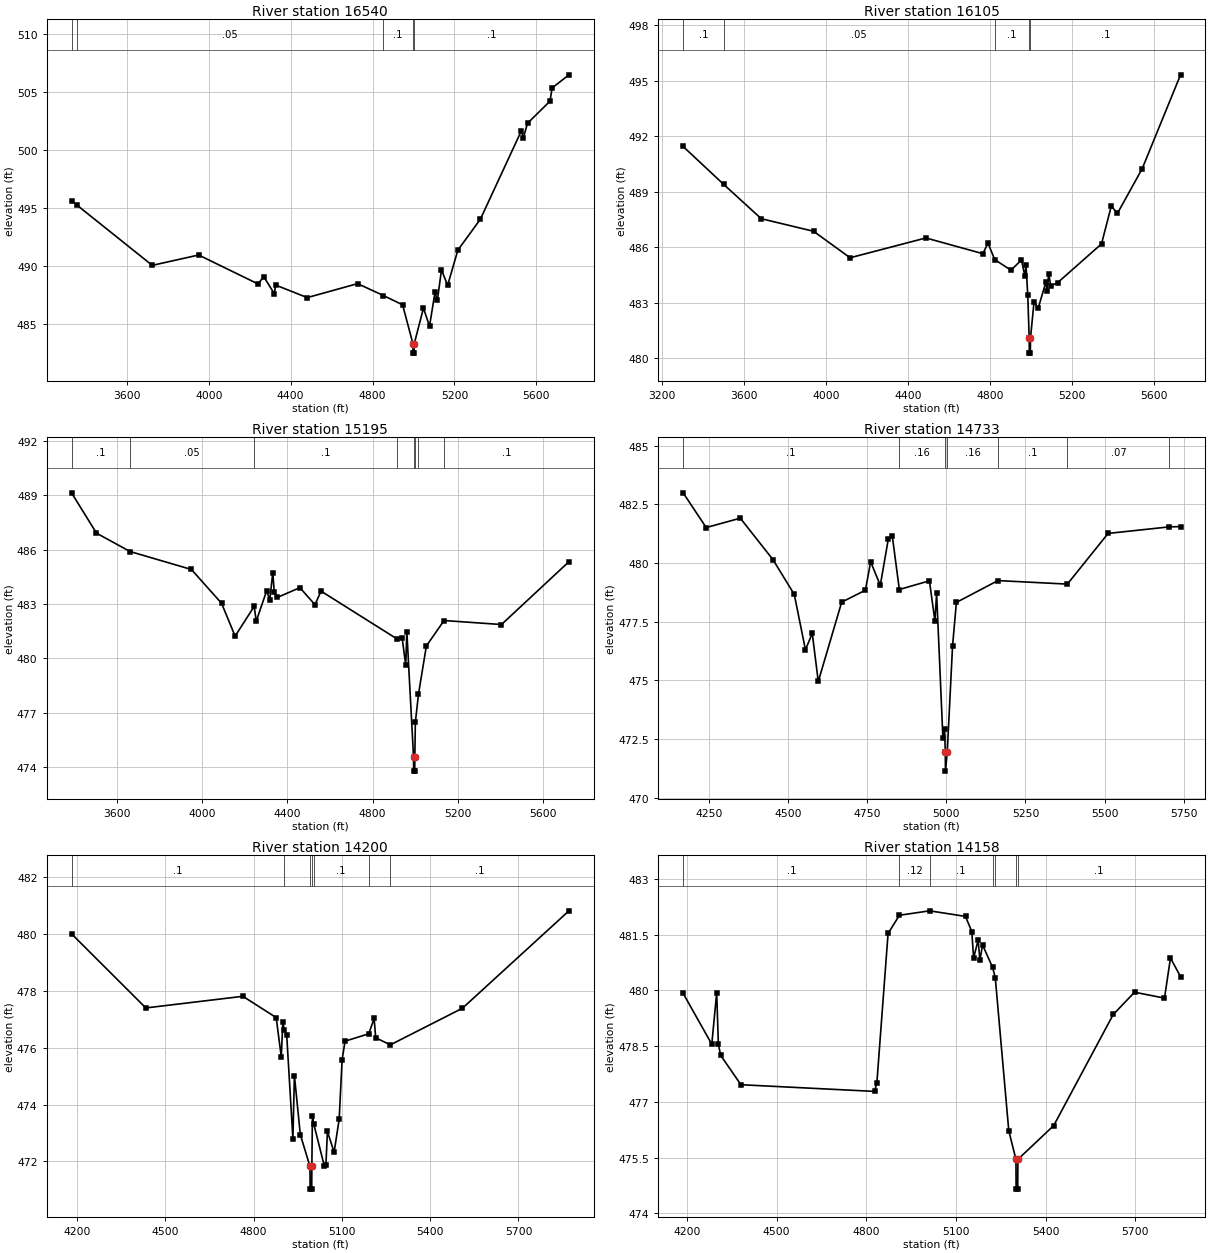
Type RM Length L Ch R = 1,16540,435,435,435
BEGIN DESCRIPTION:
Live Oak Creek 2 21.0
END DESCRIPTION:
XS GIS Cut Line= 4
      1996064.33     13452475.97      1996939.35     13451942.10
      1997220.60     13451246.79      1997196.82     13450592.78
#Sta/Elev= 30
  3329.9  495.64  3356.1  495.26  3724.2  490.08  3950.7  490.97  4241.1  488.48
  4268.3  489.12  4320.5  487.64  4326.4  488.39  4481.2  487.31  4727.0  488.51
  4852.9  487.49  4946.9  486.69  4997.4  483.34  4997.9  482.54  5003.1  482.54
  5003.6  483.34  5048.8  486.41  5078.3  484.85  5105.0  487.75  5116.7  487.07
  5136.8  489.70  5166.8  488.36  5216.8  491.39  5326.9  494.05  5527.0  501.64
  5537.0  501.06  5557.1  502.29  5667.0  504.19  5677.1  505.32  5759.4  506.45
#Mann=5,-1,0
  3329.9     0.1       0  3356.1    0.05       0  4852.9     0.1       0
  4997.4    0.07       0  5003.6     0.1       0
Bank Sta=4997.4,5003.6
Exp/Cntr=0.3,0.1

Type RM Length L Ch R = 1,16105,910,910,910
BEGIN DESCRIPTION:
Live Oak Creek 2 20.0
END DESCRIPTION:
XS GIS Cut Line= 4
      1996481.00     13452567.12      1997494.04     13451710.33
      1997632.06     13451012.41      1997599.70     13450628.78
#Sta/Elev= 30
  3305.1  491.45  3501.9  489.41  3685.7  487.55  3940.5  486.87  4118.6  485.44
  4487.8  486.51  4765.2  485.66  4790.2  486.23  4823.1  485.34  4902.3  484.77
  4953.3  485.32  4970.2  484.44  4975.3  485.04  4983.9  483.45  4991.0  481.09
  4991.5  480.29  4996.7  480.29  4997.2  481.09  5014.5  483.05  5034.9  482.72
  5072.7  484.14  5077.8  483.62  5085.8  484.58  5096.0  483.93  5129.1  484.09
  5343.3  486.19  5390.9  488.23  5421.0  487.84  5541.4  490.25  5728.3  495.32
#Mann=5,-1,0
  3305.1     0.1       0  3501.9    0.05       0  4823.1     0.1       0
  4991.0    0.07       0  4997.2     0.1       0
Bank Sta=4991,4997.2
Exp/Cntr=0.3,0.1

Type RM Length L Ch R = 1,15195,462,462,462
BEGIN DESCRIPTION:
Mapping XS 8e5455e8
END DESCRIPTION:
XS GIS Cut Line= 3
      1996975.80     13452611.38      1997931.19     13451662.19
      1998191.47     13450709.55
#Sta/Elev= 30
  3386.8  489.12  3503.9  486.90  3661.2  485.89  3949.4  484.90  4090.8  483.04
  4154.4  481.23  4244.1  482.87  4253.4  482.05  4302.9  483.74  4317.0  483.20
  4331.2  484.73  4338.3  483.64  4352.4  483.36  4458.5  483.90  4529.2  482.96
  4557.5  483.71  4913.7  481.08  4938.0  481.15  4955.1  479.65  4960.3  481.48
  4991.7  474.60  4992.2  473.80  4997.4  473.80  4997.9  474.60  5000.2  476.48
  5015.0  478.04  5052.0  480.69  5135.0  482.09  5404.5  481.87  5721.1  485.33
#Mann=8,-1,0
  3386.8     0.1       0  3661.2    0.05       0  4244.1     0.1       0
  4913.7    0.16       0  4991.7    0.07       0  4997.9    0.16       0
  5015.0    0.07       0  5135.0     0.1       0
Bank Sta=4991.7,4997.9
Exp/Cntr=0.3,0.1

Type RM Length L Ch R = 1,14733,533,533,533
BEGIN DESCRIPTION:
Mapping XS d2ac3f0a
END DESCRIPTION:
XS GIS Cut Line= 3
      1998061.39     13452349.73      1998186.40     13451870.52
      1998556.19     13450860.11
#Sta/Elev= 30
  4168.9  482.99  4241.8  481.51  4349.5  481.91  4452.8  480.14  4520.0  478.66
  4555.3  476.30  4576.8  477.00  4595.8  474.95  4669.7  478.33  4744.6  478.84
  4761.2  480.05  4791.7  479.05  4816.9  481.01  4829.8  481.13  4851.8  478.87
  4946.9  479.24  4964.2  477.53  4969.6  478.71  4989.4  472.56  4994.7  472.93
  4997.0  471.93  4997.5  471.13  5003.2  471.93  5019.9  476.46  5032.1  478.32
  5163.3  479.25  5382.6  479.10  5511.3  481.26  5704.9  481.54  5740.1  481.55
#Mann=7,-1,0
  4168.9     0.1       0  4851.8    0.16       0  4997.0    0.07       0
  5003.2    0.16       0  5163.3     0.1       0  5382.6    0.07       0
  5704.9     0.1       0
Bank Sta=4997,5003.2
Exp/Cntr=0.3,0.1

Type RM Length L Ch R = 1,14200,42,42,42
BEGIN DESCRIPTION:
Live Oak Creek 2 19.0
END DESCRIPTION:
XS GIS Cut Line= 6
      1998432.94     13452460.76      1998746.73     13451800.64
      1998774.94     13451644.39      1998772.77     13451587.97
      1998698.99     13451433.89      1998694.65     13450863.16
#Sta/Elev= 30
  4181.8  480.01  4434.2  477.40  4763.9  477.81  4877.0  477.06  4894.2  475.68
  4899.7  476.91  4904.1  476.64  4912.7  476.44  4933.7  472.80  4938.8  475.02
  4958.9  472.94  4991.7  471.82  4992.2  471.02  4997.6  471.02  4998.1  471.82
  5000.0  473.59  5004.2  473.33  5040.3  471.84  5045.9  471.88  5051.0  473.05
  5073.7  472.32  5090.9  473.48  5100.9  475.58  5110.9  476.23  5191.4  476.49
  5209.6  477.03  5215.0  476.35  5264.7  476.10  5509.6  477.39  5871.4  480.82
#Mann=7,-1,0
  4181.8     0.1       0  4904.1    0.12       0  4991.7    0.07       0
  4998.1    0.12       0  5004.2     0.1       0  5191.4    0.16       0
  5264.7     0.1       0
Bank Sta=4991.7,4998.1
Exp/Cntr=0.3,0.1

Type RM Length L Ch R = 1,14158,29,29,29
BEGIN DESCRIPTION:
Mapping XS dfdda6f8
END DESCRIPTION:
XS GIS Cut Line= 6
      1998455.91     13452456.06      1998772.77     13451833.20
      1998816.17     13451653.07      1998816.17     13451596.65
      1998753.24     13451488.14      1998716.35     13450891.38
#Sta/Elev= 30
  4187.1  479.92  4283.0  478.55  4299.4  479.94  4305.0  478.55  4312.7  478.25
  4380.5  477.46  4827.5  477.28  4835.3  477.51  4872.8  481.53  4910.7  482.02
  5011.8  482.14  5131.9  481.99  5153.0  481.58  5158.9  480.87  5174.2  481.35
  5180.1  480.81  5189.0  481.22  5222.5  480.62  5231.5  480.34  5276.7  476.22
  5300.7  475.45  5301.2  474.65  5306.6  474.65  5307.1  475.45  5427.0  476.36
  5626.2  479.35  5697.5  479.95  5797.7  479.79  5817.7  480.87  5851.4  480.37
#Mann=7,-1,0
  4187.1     0.1       0  4910.7    0.12       0  5011.8     0.1       0
  5222.5    0.16       0  5231.5     0.1       0  5300.7    0.07       0
  5307.1     0.1       0
Bank Sta=5300.7,5307.1
Exp/Cntr=0.3,0.1

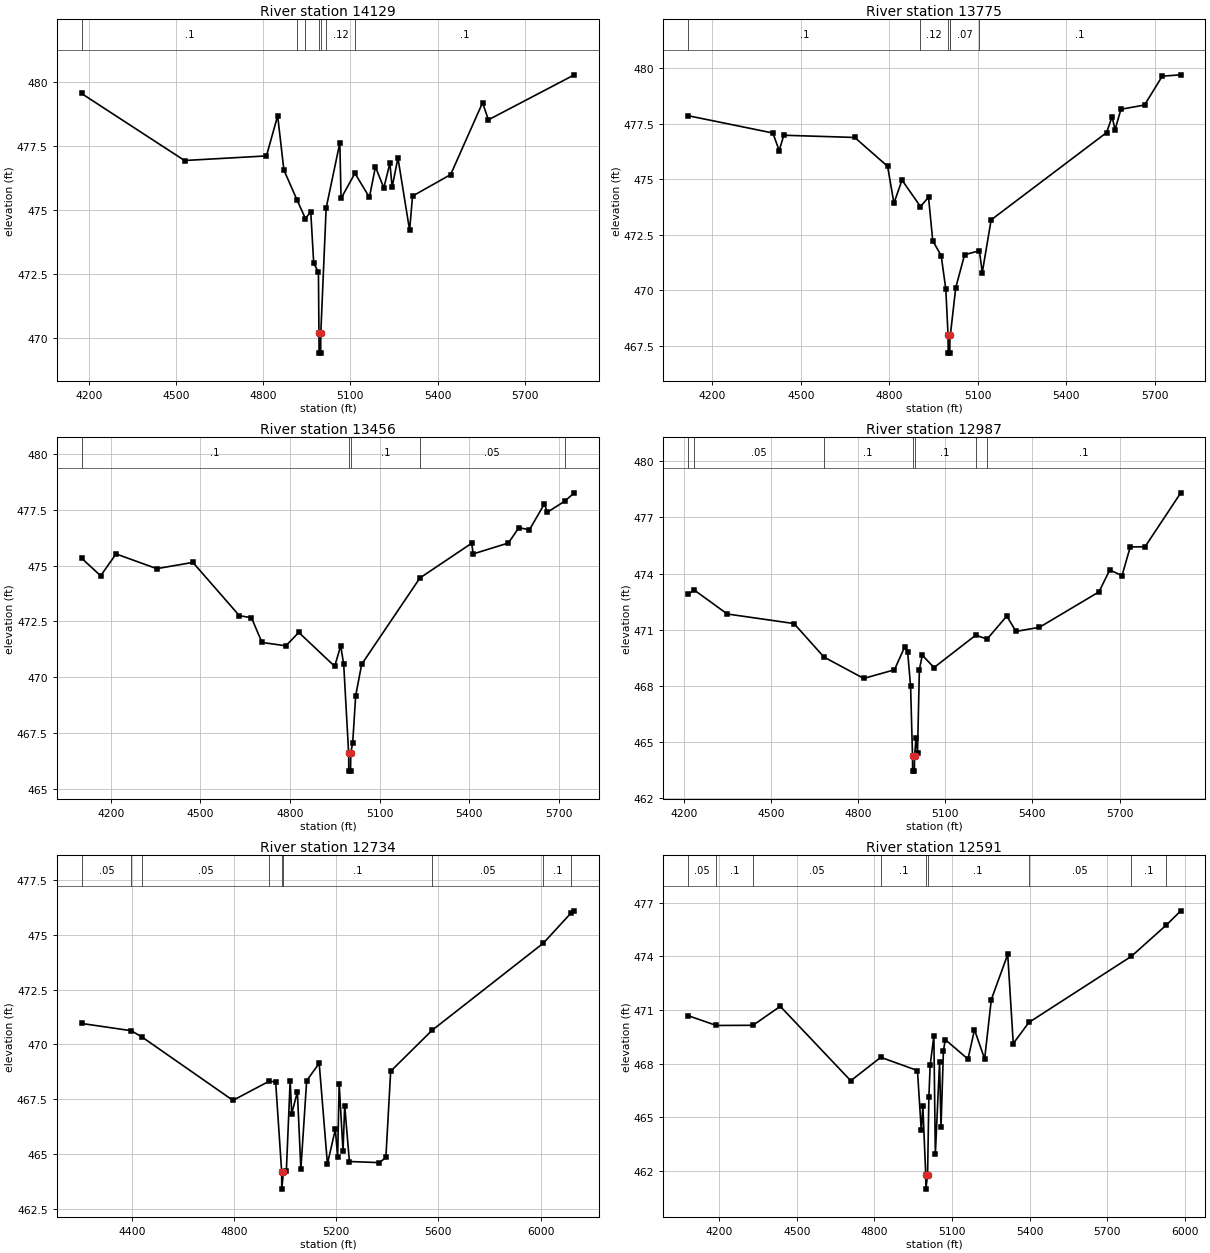
Type RM Length L Ch R = 1,14129,354,354,354
BEGIN DESCRIPTION:
Mapping XS 8a4e8867
END DESCRIPTION:
XS GIS Cut Line= 6
      1998486.31     13452473.39      1998800.98     13451867.92
      1998829.19     13451744.22      1998848.72     13451574.95
      1998796.64     13451509.84      1998744.56     13450880.54
#Sta/Elev= 30
  4175.6  479.56  4529.7  476.94  4811.5  477.12  4850.0  478.69  4871.4  476.57
  4917.3  475.38  4945.5  474.67  4963.8  474.94  4974.0  472.92  4990.2  472.58
  4992.0  470.21  4992.5  469.41  4997.9  469.41  4998.4  470.21  5016.8  475.08
  5063.8  477.63  5068.0  475.46  5115.8  476.44  5165.5  475.50  5186.3  476.69
  5215.2  475.87  5236.0  476.84  5243.7  475.90  5263.7  477.04  5303.8  474.21
  5313.8  475.55  5444.9  476.39  5554.7  479.20  5574.7  478.53  5870.2  480.29
#Mann=7,-1,0
  4175.6     0.1       0  4917.3    0.12       0  4945.5    0.16       0
  4992.0    0.07       0  4998.4    0.16       0  5016.8    0.12       0
  5115.8     0.1       0
Bank Sta=4992,4998.4
Exp/Cntr=0.3,0.1

Type RM Length L Ch R = 1,13775,319,319,319
BEGIN DESCRIPTION:
Live Oak Creek 2 18.0
END DESCRIPTION:
XS GIS Cut Line= 3
      1998726.34     13452491.16      1999175.00     13451725.00
      1999197.25     13450942.18
#Sta/Elev= 30
  4117.2  477.86  4404.9  477.08  4426.4  476.29  4442.0  476.98  4682.5  476.88
  4794.0  475.58  4815.5  473.92  4842.8  474.96  4905.5  473.77  4932.8  474.19
  4947.1  472.23  4975.7  471.56  4991.4  470.05  4999.0  467.97  4999.5  467.17
  5004.9  467.17  5005.4  467.97  5006.7  467.97  5025.1  470.12  5055.1  471.60
  5105.2  471.78  5115.1  470.80  5145.1  473.17  5536.7  477.10  5555.3  477.82
  5565.3  477.23  5585.3  478.15  5665.3  478.34  5725.4  479.64  5788.2  479.70
#Mann=6,-1,0
  4117.2     0.1       0  4905.5    0.12       0  4999.0    0.07       0
  5005.4    0.12       0  5006.7    0.07       0  5105.2     0.1       0
Bank Sta=4999,5005.4
Exp/Cntr=0.3,0.1

Type RM Length L Ch R = 1,13456,469,469,469
BEGIN DESCRIPTION:
Live Oak Creek 2 17.0
END DESCRIPTION:
XS GIS Cut Line= 3
      1999171.21     13452663.49      1999436.83     13452085.37
      1999501.93     13451074.99
#Sta/Elev= 30
  4102.4  475.34  4166.3  474.55  4217.8  475.53  4353.9  474.87  4474.9  475.15
  4630.5  472.76  4670.9  472.67  4706.0  471.56  4786.0  471.41  4829.2  472.01
  4949.4  470.49  4969.5  471.41  4979.5  470.58  4996.1  466.59  4996.6  465.79
  5002.5  465.79  5003.0  466.59  5009.6  467.06  5019.6  469.17  5039.6  470.58
  5234.4  474.45  5407.7  476.01  5412.7  475.53  5530.6  476.02  5565.6  476.71
  5600.8  476.61  5650.9  477.77  5660.9  477.40  5718.4  477.89  5751.1  478.27
#Mann=5,-1,0
  4102.4     0.1       0  4996.1    0.07       0  5003.0     0.1       0
  5234.4    0.05       0  5718.4     0.1       0
Bank Sta=4996.1,5003
Exp/Cntr=0.3,0.1

Type RM Length L Ch R = 1,12987,253,253,253
BEGIN DESCRIPTION:
Live Oak Creek 2 16.0
END DESCRIPTION:
XS GIS Cut Line= 3
      1999504.53     13452593.20      1999845.69     13452100.99
      1999986.32     13451012.42
#Sta/Elev= 30
  4214.3  472.89  4235.7  473.12  4349.4  471.84  4579.1  471.33  4682.4  469.54
  4819.2  468.40  4925.0  468.86  4960.4  470.09  4970.5  469.81  4980.6  467.98
  4987.2  464.25  4987.7  463.45  4993.6  463.45  4994.1  464.25  4999.3  465.21
  5004.4  464.42  5010.8  468.87  5020.9  469.64  5061.2  468.98  5205.0  470.71
  5244.0  470.50  5311.7  471.73  5343.5  470.91  5424.2  471.13  5629.1  473.02
  5666.2  474.19  5708.5  473.89  5736.8  475.42  5787.8  475.43  5910.8  478.31
#Mann=7,-1,0
  4214.3     0.1       0  4235.7    0.05       0  4682.4     0.1       0
  4987.2    0.07       0  4994.1     0.1       0  5205.0    0.05       0
  5244.0     0.1       0
Bank Sta=4987.2,4994.1
Exp/Cntr=0.3,0.1

Type RM Length L Ch R = 1,12734,143,143,143
BEGIN DESCRIPTION:
Mapping XS 7a183f51
END DESCRIPTION:
XS GIS Cut Line= 6
      1999645.84     13452570.57      2000192.72     13451776.30
      2000279.52     13451821.87      2000292.54     13451802.34
      2000205.74     13451711.20      2000690.94     13451193.50
#Sta/Elev= 30
  4203.5  470.96  4397.7  470.63  4440.3  470.34  4795.9  467.45  4936.8  468.32
  4963.0  468.30  4986.5  464.20  4987.0  463.40  4993.6  464.20  5004.9  464.24
  5019.8  468.34  5025.9  466.84  5048.0  467.84  5061.7  464.31  5084.4  468.35
  5133.4  469.14  5165.6  464.55  5196.6  466.13  5205.6  464.87  5211.6  468.19
  5226.6  465.14  5233.2  467.21  5251.6  464.66  5369.3  464.61  5394.4  464.85
  5413.1  468.78  5575.3  470.65  6011.1  474.63  6119.6  476.01  6131.7  476.10
#Mann=9,-1,0
  4203.5    0.05       0  4397.7     0.1       0  4440.3    0.05       0
  4936.8     0.1       0  4986.5    0.07       0  4993.6     0.1       0
  5575.3    0.05       0  6011.1     0.1       0  6119.6    0.05       0
Bank Sta=4986.5,4993.6
Exp/Cntr=0.3,0.1

Type RM Length L Ch R = 1,12591,63,63,63
BEGIN DESCRIPTION:
Mapping XS 4c18ee66
END DESCRIPTION:
XS GIS Cut Line= 6
      1999663.22     13452581.39      2000210.08     13451821.87
      2000309.90     13451841.40      2000320.76     13451745.92
      2000275.18     13451702.52      2000751.32     13451196.08
#Sta/Elev= 30
  4079.7  470.69  4189.4  470.14  4330.7  470.15  4436.2  471.21  4708.6  467.05
  4824.6  468.36  4966.4  467.62  4981.1  464.28  4987.3  465.61  4998.4  461.79
  4998.9  460.99  5005.5  461.79  5010.5  466.13  5015.5  467.92  5029.8  469.55
  5035.5  462.94  5051.8  468.10  5057.4  464.44  5066.6  468.69  5073.7  469.35
  5161.6  468.26  5186.8  469.90  5226.0  468.27  5251.8  471.59  5315.2  474.11
  5336.6  469.13  5397.0  470.31  5793.4  474.01  5928.6  475.76  5984.0  476.55
#Mann=9,-1,0
  4079.7    0.05       0  4189.4     0.1       0  4330.7    0.05       0
  4824.6     0.1       0  4998.4    0.07       0  5005.5     0.1       0
  5397.0    0.05       0  5793.4     0.1       0  5928.6    0.05       0
Bank Sta=4998.4,5005.5
Exp/Cntr=0.3,0.1

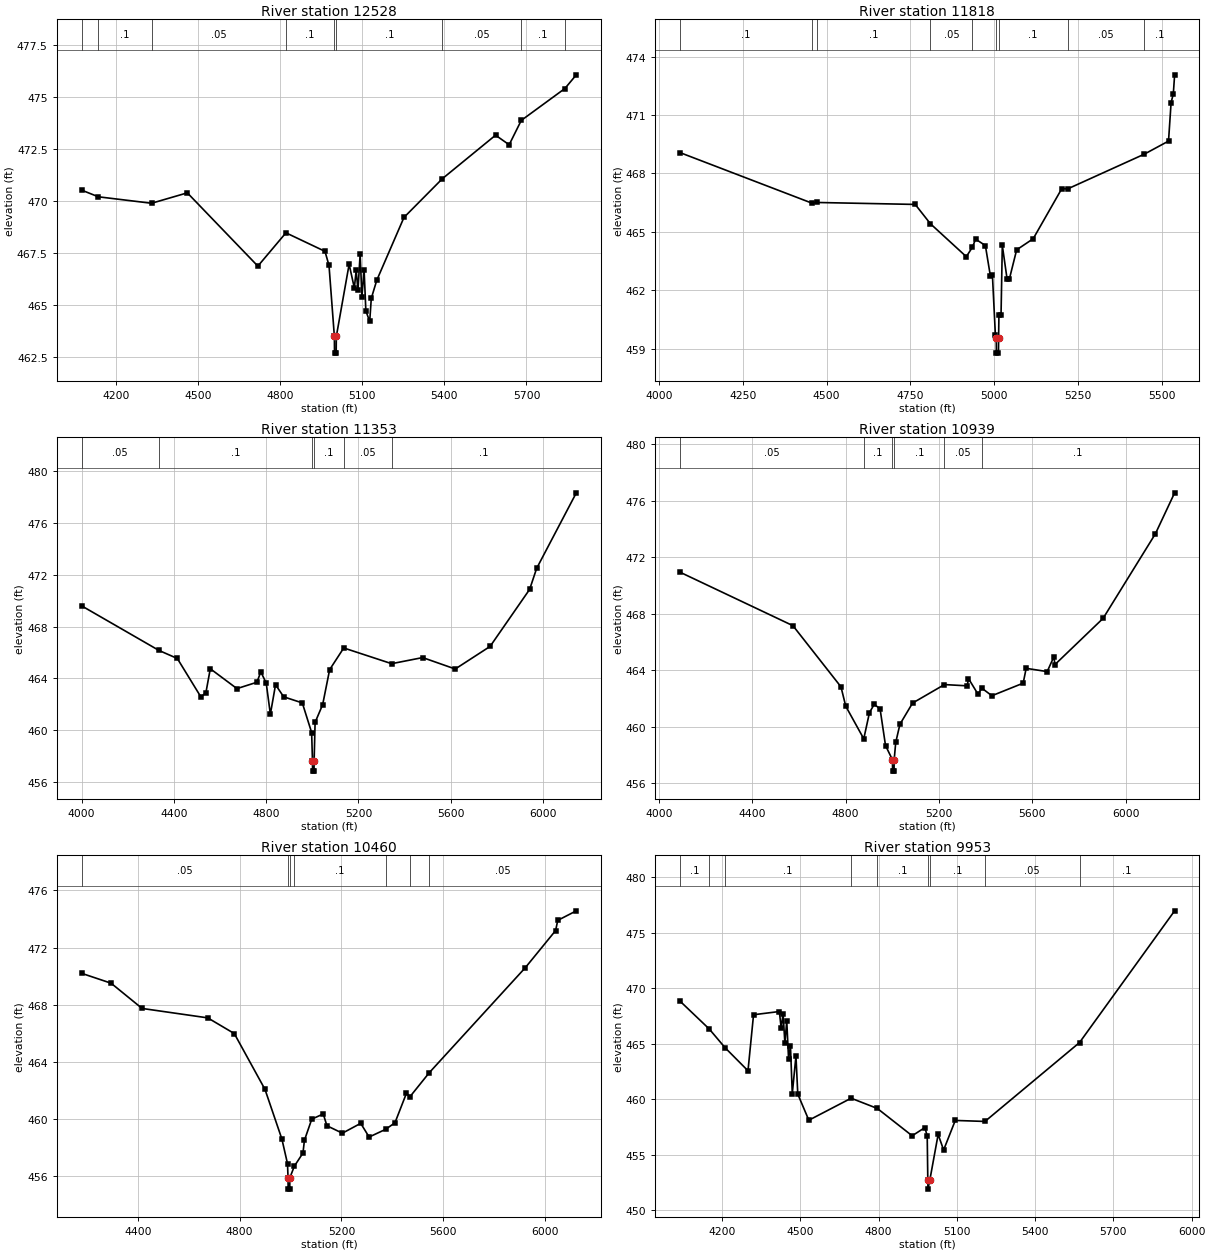
Type RM Length L Ch R = 1,12528,710,710,710
BEGIN DESCRIPTION:
Mapping XS 996ef9d3
END DESCRIPTION:
XS GIS Cut Line= 6
      1999676.21     13452585.78      2000194.89     13451867.45
      2000307.73     13451871.79      2000340.29     13451830.55
      2000340.29     13451741.58      2000756.92     13451222.95
#Sta/Elev= 30
  4075.7  470.52  4136.8  470.20  4331.0  469.89  4461.6  470.39  4719.2  466.87
  4821.7  468.47  4964.3  467.58  4979.0  466.90  4998.6  463.49  4999.1  462.69
  5005.2  462.69  5005.7  463.49  5052.5  466.96  5071.5  465.82  5078.3  466.67
  5084.7  465.70  5092.7  467.45  5099.1  465.40  5107.2  466.67  5113.6  464.72
  5127.6  464.21  5133.4  465.32  5153.4  466.19  5252.8  469.21  5393.0  471.07
  5587.2  473.16  5636.9  472.70  5681.1  473.87  5840.2  475.40  5882.1  476.06
#Mann=9,-1,0
  4075.7    0.05       0  4136.8     0.1       0  4331.0    0.05       0
  4821.7     0.1       0  4998.6    0.07       0  5005.7     0.1       0
  5393.0    0.05       0  5681.1     0.1       0  5840.2    0.05       0
Bank Sta=4998.6,5005.7
Exp/Cntr=0.3,0.1

Type RM Length L Ch R = 1,11818,465,465,465
BEGIN DESCRIPTION:
Live Oak Creek 2 15.0
END DESCRIPTION:
XS GIS Cut Line= 3
      1999785.83     13452762.42      2000575.00     13452225.00
      2000970.32     13451885.16
#Sta/Elev= 30
  4062.4  469.07  4455.6  466.48  4471.8  466.51  4764.4  466.41  4809.7  465.42
  4916.9  463.73  4935.3  464.22  4944.6  464.63  4973.8  464.30  4988.7  462.74
  4994.8  462.79  5003.7  459.69  5006.2  459.58  5006.7  458.78  5012.8  458.78
  5013.3  459.58  5014.2  460.72  5020.5  460.72  5024.3  464.31  5038.6  462.58
  5045.2  462.57  5067.1  464.08  5116.5  464.65  5201.8  467.22  5219.7  467.21
  5448.1  468.99  5520.3  469.66  5528.0  471.64  5534.6  472.08  5538.5  473.06
#Mann=9,-1,0
  4062.4     0.1       0  4455.6    0.05       0  4471.8     0.1       0
  4809.7    0.05       0  4935.3     0.1       0  5006.2    0.07       0
  5013.3     0.1       0  5219.7    0.05       0  5448.1     0.1       0
Bank Sta=5006.2,5013.3
Exp/Cntr=0.3,0.1

Type RM Length L Ch R = 1,11353,414,414,414
BEGIN DESCRIPTION:
Live Oak Creek 2 14.0
END DESCRIPTION:
XS GIS Cut Line= 3
      1999744.09     13452882.25      2000725.00     13452625.00
      2001845.68     13452486.41
#Sta/Elev= 30
  4000.6  469.59  4335.5  466.16  4415.1  465.54  4517.6  462.57  4539.1  462.92
  4558.0  464.75  4673.5  463.22  4759.9  463.71  4776.9  464.51  4800.3  463.65
  4818.3  461.25  4840.7  463.52  4875.9  462.59  4956.7  462.12  4997.1  459.84
  5000.7  457.67  5001.3  456.87  5007.4  456.87  5007.9  457.67  5012.1  460.62
  5044.9  461.99  5075.1  464.68  5136.2  466.35  5343.8  465.14  5478.2  465.61
  5619.3  464.73  5770.4  466.47  5941.7  470.86  5971.9  472.47  6143.9  478.29
#Mann=6,-1,0
  4000.6    0.05       0  4335.5     0.1       0  5000.7    0.07       0
  5007.9     0.1       0  5136.2    0.05       0  5343.8     0.1       0
Bank Sta=5000.7,5007.9
Exp/Cntr=0.3,0.1

Type RM Length L Ch R = 1,10939,479,479,479
BEGIN DESCRIPTION:
Live Oak Creek 2 13.0
END DESCRIPTION:
XS GIS Cut Line= 3
      1999757.14     13453192.14      2000625.00     13453025.00
      2001824.96     13452725.01
#Sta/Elev= 30
  4089.6  470.93  4574.0  467.14  4779.9  462.81  4800.3  461.44  4877.6  459.13
  4902.1  460.99  4922.5  461.57  4947.5  461.25  4970.9  458.65  5000.7  457.64
  5001.2  456.84  5007.4  456.84  5008.0  457.64  5014.6  458.87  5032.7  460.16
  5086.8  461.66  5223.5  462.97  5321.3  462.88  5326.4  463.40  5367.7  462.28
  5383.4  462.72  5426.9  462.18  5561.0  463.07  5573.8  464.12  5664.0  463.89
  5692.4  464.93  5697.5  464.39  5903.7  467.66  6127.9  473.65  6210.3  476.55
#Mann=6,-1,0
  4089.6    0.05       0  4877.6     0.1       0  5000.7    0.07       0
  5008.0     0.1       0  5223.5    0.05       0  5383.4     0.1       0
Bank Sta=5000.7,5008
Exp/Cntr=0.3,0.1

Type RM Length L Ch R = 1,10460,507,507,507
BEGIN DESCRIPTION:
Live Oak Creek 2 12.0
END DESCRIPTION:
XS GIS Cut Line= 3
      2000041.82     13453618.36      2000584.40     13453507.67
      2001817.02     13452867.50
#Sta/Elev= 30
  4179.6  470.19  4295.1  469.50  4417.0  467.73  4674.8  467.07  4779.1  465.97
  4899.6  462.06  4966.0  458.58  4988.1  456.85  4990.1  455.87  4990.6  455.07
  4996.8  455.07  4997.4  455.87  5015.0  456.68  5048.8  457.60  5054.5  458.49
  5083.3  459.97  5128.4  460.34  5142.9  459.51  5203.6  458.99  5275.6  459.68
  5308.6  458.72  5373.4  459.26  5410.1  459.72  5455.2  461.79  5469.2  461.55
  5544.9  463.23  5922.2  470.59  6041.1  473.19  6049.3  473.90  6122.3  474.57
#Mann=7,-1,0
  4179.6    0.05       0  4990.1    0.03       0  4997.4    0.05       0
  5015.0     0.1       0  5373.4    0.05       0  5469.2     0.1       0
  5544.9    0.05       0
Bank Sta=4990.1,4997.4
Exp/Cntr=0.3,0.1

Type RM Length L Ch R = 1,9953,486,486,486
BEGIN DESCRIPTION:
Live Oak Creek 2 11.0
END DESCRIPTION:
XS GIS Cut Line= 3
      2000530.12     13454288.95      2001175.00     13453625.00
      2001975.00     13453075.00
#Sta/Elev= 30
  4038.3  468.84  4150.5  466.33  4211.4  464.64  4299.1  462.57  4320.4  467.61
  4419.4  467.90  4426.4  466.38  4433.6  467.71  4440.6  465.04  4447.7  467.06
  4454.7  463.63  4461.9  464.81  4468.9  460.51  4483.0  463.90  4490.0  460.47
  4532.4  458.12  4694.5  460.10  4794.9  459.18  4928.5  456.72  4977.4  457.46
  4986.2  456.69  4988.5  452.72  4989.1  451.92  4996.1  452.72  5028.1  456.84
  5049.1  455.44  5093.8  458.10  5207.6  458.01  5570.2  465.11  5934.7  476.96
#Mann=9,-1,0
  4038.3     0.1       0  4150.5    0.05       0  4211.4     0.1       0
  4694.5    0.05       0  4794.9     0.1       0  4988.5    0.07       0
  4996.1     0.1       0  5207.6    0.05       0  5570.2     0.1       0
Bank Sta=4988.5,4996.1
Exp/Cntr=0.3,0.1

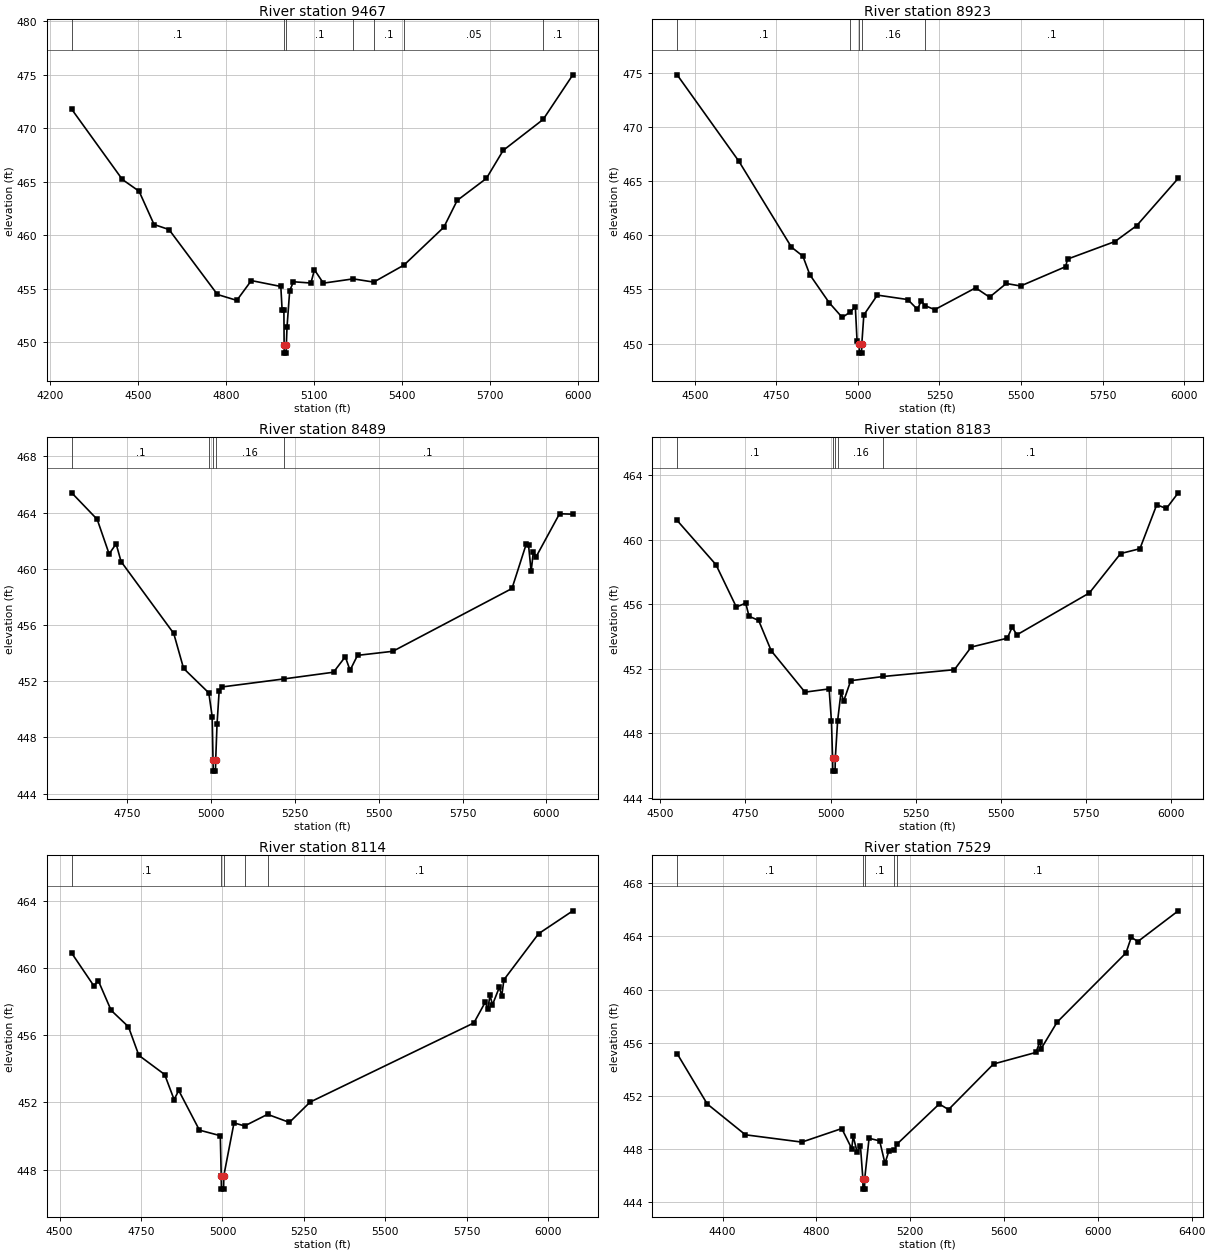
Type RM Length L Ch R = 1,9467,544,544,544
BEGIN DESCRIPTION:
Live Oak Creek 2 10.0
END DESCRIPTION:
XS GIS Cut Line= 3
      2000724.97     13454425.02      2001325.00     13454025.00
      2002156.28     13453489.09
#Sta/Elev= 30
  4273.6  471.78  4446.4  465.22  4503.5  464.12  4554.6  461.01  4605.6  460.54
  4770.9  454.47  4837.0  453.92  4886.6  455.77  4987.2  455.22  4991.7  452.98
  4997.7  452.98  4998.5  449.79  4999.1  448.99  5005.5  448.99  5006.1  449.79
  5008.3  451.40  5017.5  454.83  5030.4  455.66  5089.9  455.54  5102.0  456.78
  5132.4  455.53  5234.2  455.93  5304.3  455.63  5407.6  457.22  5543.6  460.76
  5589.1  463.26  5688.8  465.32  5746.2  467.94  5882.5  470.83  5983.8  475.00
#Mann=7,-1,0
  4273.6     0.1       0  4998.5    0.07       0  5006.1     0.1       0
  5234.2    0.05       0  5304.3     0.1       0  5407.6    0.05       0
  5882.5     0.1       0
Bank Sta=4998.5,5006.1
Exp/Cntr=0.3,0.1

Type RM Length L Ch R = 1,8923,434,434,434
BEGIN DESCRIPTION:
Live Oak Creek 2 9.0
END DESCRIPTION:
XS GIS Cut Line= 3
      2000862.17     13454590.14      2001692.04     13454369.65
      2002261.61     13454004.37
#Sta/Elev= 30
  4446.2  474.79  4635.4  466.82  4796.5  458.90  4831.5  458.07  4852.7  456.36
  4911.8  453.79  4952.0  452.42  4974.6  452.88  4992.2  453.40  4997.5  450.22
  5003.9  449.93  5004.6  449.13  5011.2  449.13  5011.9  449.93  5018.2  452.65
  5059.6  454.48  5152.8  454.07  5182.6  453.16  5194.1  453.98  5204.7  453.52
  5235.5  453.14  5360.8  455.15  5403.4  454.29  5454.6  455.55  5498.5  455.32
  5636.4  457.10  5642.3  457.80  5787.7  459.42  5854.4  460.89  5981.5  465.25
#Mann=5,-1,0
  4446.2     0.1       0  4974.6    0.16       0  5003.9    0.07       0
  5011.9    0.16       0  5204.7     0.1       0
Bank Sta=5003.9,5011.9
Exp/Cntr=0.3,0.1

Type RM Length L Ch R = 1,8489,306,306,306
BEGIN DESCRIPTION:
Live Oak Creek 2 8.0
END DESCRIPTION:
XS GIS Cut Line= 3
      2001152.14     13455057.14      2001475.00     13454825.00
      2002318.79     13454123.12
#Sta/Elev= 30
  4583.7  465.41  4659.7  463.52  4695.3  461.06  4716.2  461.78  4730.9  460.52
  4888.1  455.40  4917.5  452.91  4992.7  451.17  5002.8  449.48  5005.3  446.40
  5006.0  445.60  5012.6  445.60  5013.3  446.40  5017.2  448.92  5023.7  451.33
  5031.5  451.59  5215.6  452.16  5364.8  452.64  5399.9  453.74  5414.2  452.78
  5436.4  453.84  5541.8  454.13  5897.3  458.60  5940.2  461.79  5946.7  461.69
  5954.5  459.81  5961.0  461.21  5968.9  460.84  6039.2  463.92  6078.9  463.89
#Mann=5,-1,0
  4583.7     0.1       0  4992.7    0.16       0  5005.3    0.07       0
  5013.3    0.16       0  5215.6     0.1       0
Bank Sta=5005.3,5013.3
Exp/Cntr=0.3,0.1

Type RM Length L Ch R = 1,8183,69,69,69
BEGIN DESCRIPTION:
Mapping XS 051c20f2
END DESCRIPTION:
XS GIS Cut Line= 3
      2001299.65     13455284.60      2001544.47     13455150.90
      2002353.48     13454274.19
#Sta/Elev= 30
  4549.3  461.19  4663.4  458.45  4723.2  455.83  4750.7  456.07  4760.5  455.26
  4788.7  455.00  4825.7  453.12  4924.8  450.56  4995.7  450.76  5002.5  448.79
  5005.9  446.47  5006.5  445.67  5013.2  445.67  5013.9  446.47  5020.7  448.79
  5030.8  450.58  5038.2  449.99  5059.2  451.27  5155.2  451.53  5363.7  451.95
  5413.0  453.35  5519.1  453.90  5533.3  454.58  5547.4  454.11  5760.1  456.70
  5851.9  459.14  5908.6  459.44  5958.0  462.16  5986.3  461.93  6021.2  462.90
#Mann=5,-1,0
  4549.3     0.1       0  5005.9    0.07       0  5013.9     0.1       0
  5020.7    0.16       0  5155.2     0.1       0
Bank Sta=5005.9,5013.9
Exp/Cntr=0.3,0.1

Type RM Length L Ch R = 1,8114,585,585,585
BEGIN DESCRIPTION:
Live Oak Creek 2 7.0
END DESCRIPTION:
XS GIS Cut Line= 4
      2001301.39     13455307.16      2001573.99     13455208.20
      2002179.89     13454548.47      2002409.06     13454281.10
#Sta/Elev= 30
  4537.3  460.88  4605.0  458.94  4618.9  459.24  4658.2  457.48  4711.4  456.50
  4743.3  454.80  4822.5  453.66  4851.5  452.17  4865.7  452.71  4929.2  450.35
  4993.3  450.02  4996.1  447.64  4996.7  446.84  5003.4  446.84  5004.1  447.64
  5035.3  450.78  5068.0  450.60  5138.3  451.29  5205.4  450.81  5268.9  452.02
  5771.5  456.73  5806.6  457.97  5814.3  457.54  5820.9  458.38  5828.6  457.81
  5849.4  458.84  5857.1  458.35  5863.7  459.30  5970.2  462.04  6075.2  463.40
#Mann=5,-1,0
  4537.3     0.1       0  4996.1    0.07       0  5004.1     0.1       0
  5068.0    0.16       0  5138.3     0.1       0
Bank Sta=4996.1,5004.1
Exp/Cntr=0.3,0.1

Type RM Length L Ch R = 1,7529,490,490,490
BEGIN DESCRIPTION:
Live Oak Creek 2 6.0
END DESCRIPTION:
XS GIS Cut Line= 3
      2001466.32     13456078.02      2001969.82     13455525.90
      2002574.99     13454275.03
#Sta/Elev= 30
  4206.1  455.18  4334.5  451.39  4497.3  449.07  4738.0  448.52  4908.1  449.54
  4950.6  448.03  4956.8  448.97  4973.8  447.75  4987.7  448.24  4998.0  445.78
  4998.6  444.98  5005.3  444.98  5006.0  445.78  5024.6  448.81  5069.8  448.61
  5092.3  446.92  5109.4  447.87  5132.3  447.89  5142.5  448.35  5323.8  451.39
  5363.4  450.97  5555.3  454.40  5736.0  455.27  5753.0  456.09  5758.6  455.56
  5826.3  457.55  6120.0  462.76  6142.6  463.94  6170.7  463.62  6342.9  465.93
#Mann=5,-1,0
  4206.1     0.1       0  4998.0    0.07       0  5006.0     0.1       0
  5132.3    0.16       0  5142.5     0.1       0
Bank Sta=4998,5006
Exp/Cntr=0.3,0.1