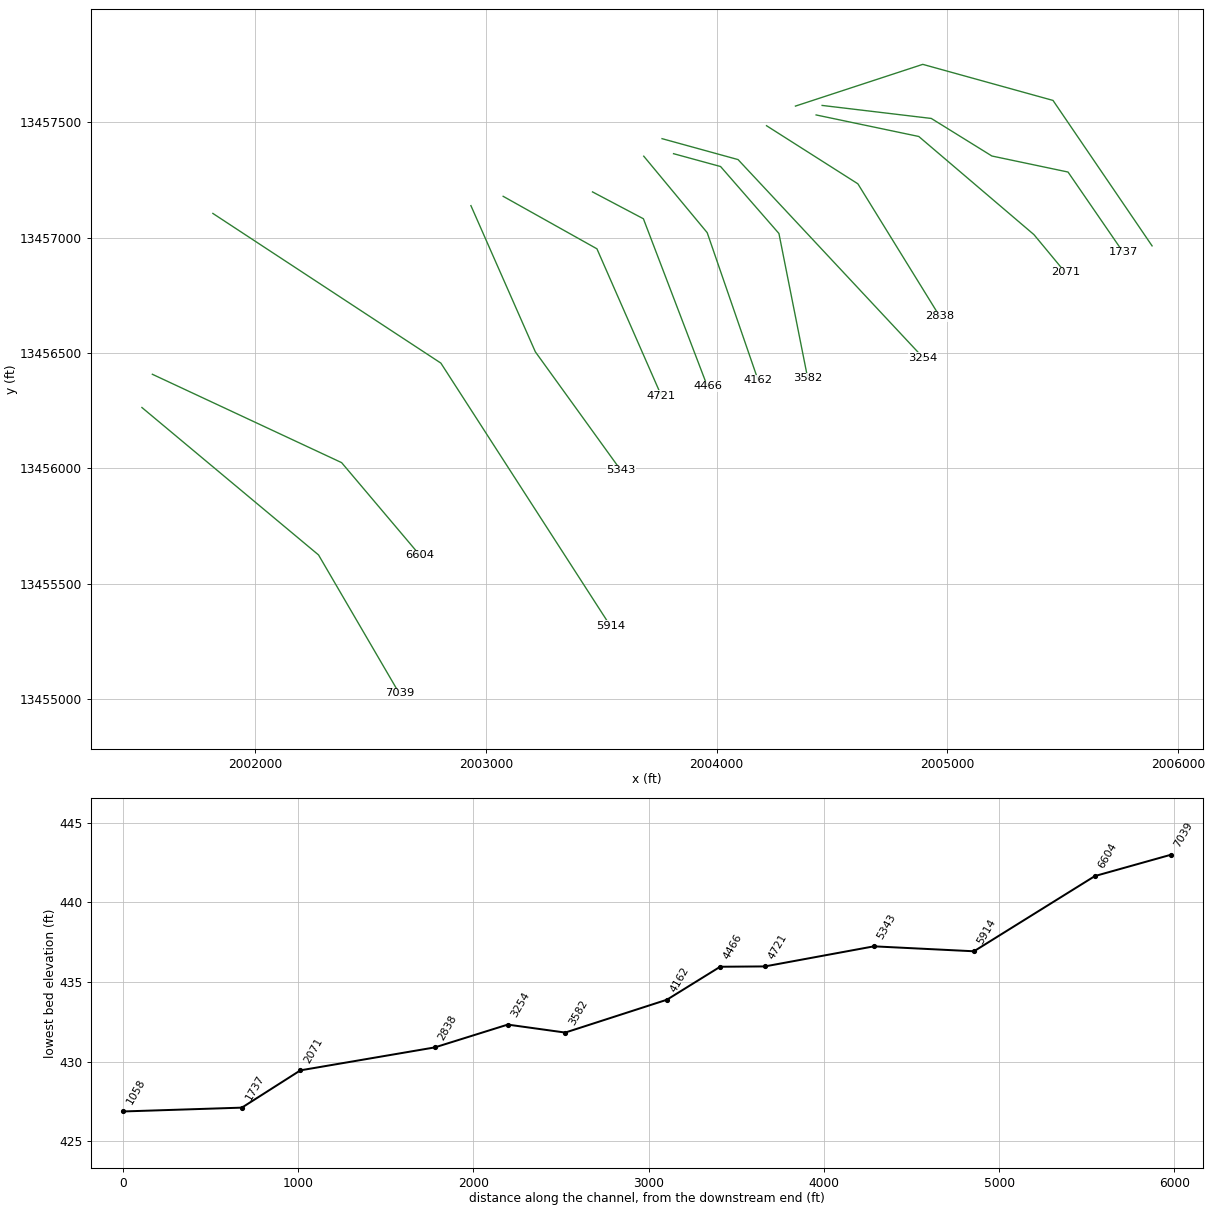
HEC-RAS study Live Oak Creek 2.prj: Live Oak Creek 2 Base Level Engineering

--- Live Oak Creek 2.g01 (geometry) --- (continued)

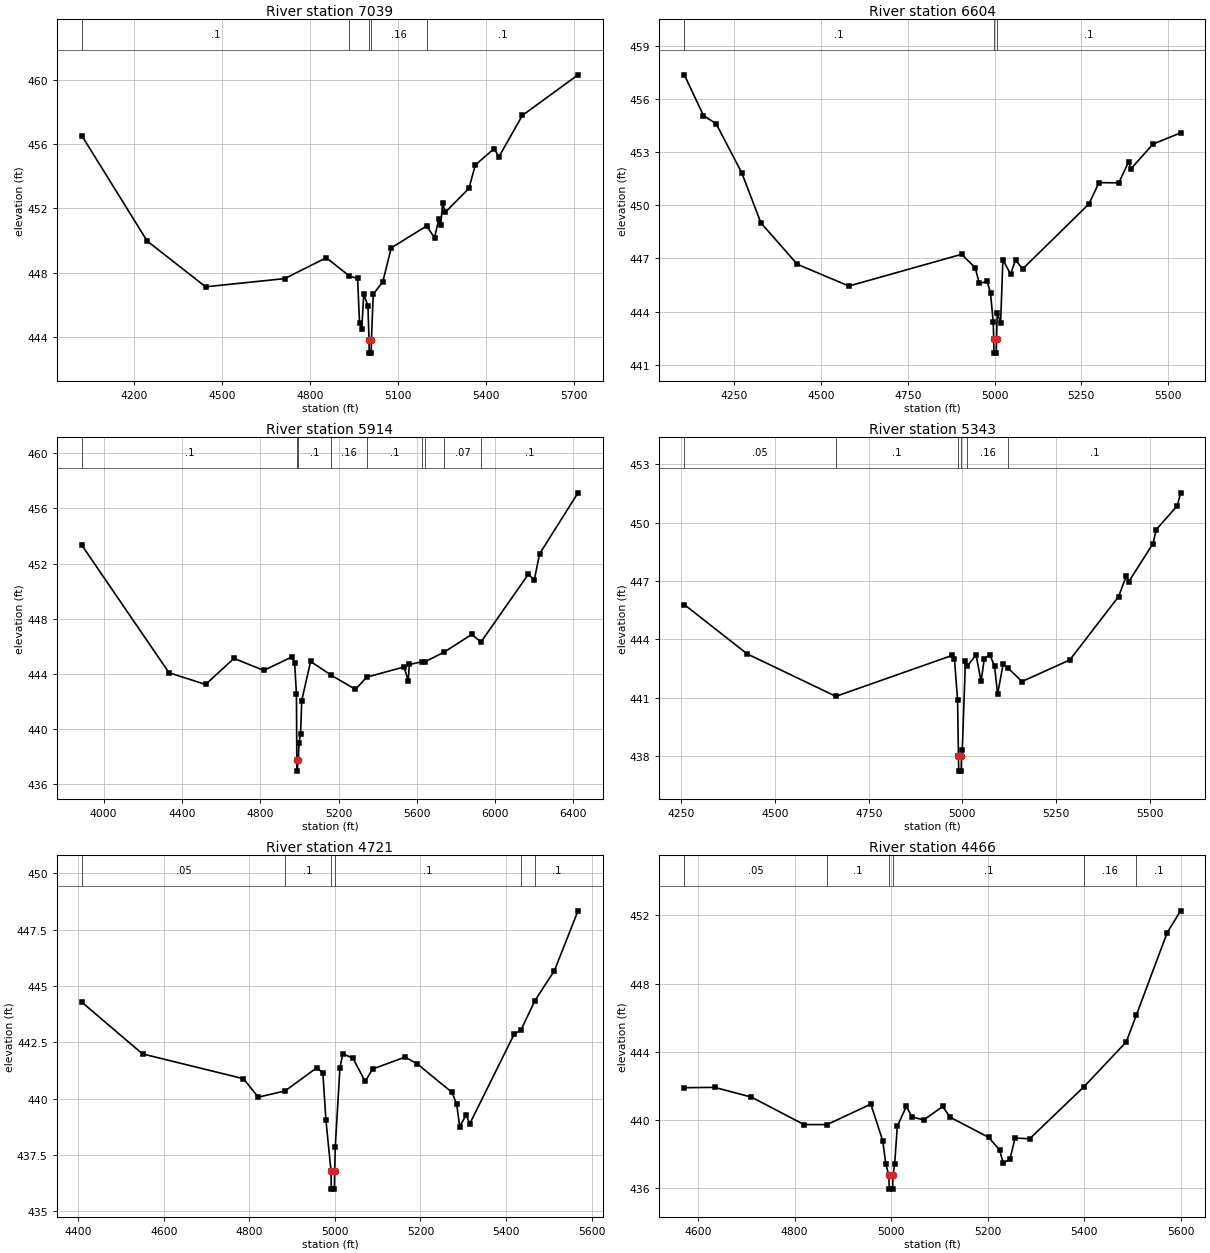
Type RM Length L Ch R = 1,7039,435,435,435
BEGIN DESCRIPTION:
Live Oak Creek 2 5.0
END DESCRIPTION:
XS GIS Cut Line= 3
      2001509.75     13456263.75      2002275.00     13455625.00
      2002624.99     13455025.02
#Sta/Elev= 30
  4021.7  456.54  4244.7  449.97  4443.9  447.12  4713.3  447.63  4855.2  448.93
  4933.5  447.80  4961.9  447.64  4968.4  444.89  4976.2  444.49  4982.7  446.66
  4997.0  445.95  5000.8  443.79  5001.5  442.99  5008.2  442.99  5008.9  443.79
  5015.2  446.66  5047.9  447.44  5076.4  449.54  5197.1  450.91  5224.0  450.18
  5238.5  451.32  5245.5  450.96  5251.3  452.31  5261.2  451.77  5341.4  453.25
  5362.9  454.70  5427.4  455.73  5443.1  455.20  5523.3  457.79  5713.1  460.32
#Mann=5,-1,0
  4021.7     0.1       0  4933.5    0.16       0  5000.8    0.07       0
  5008.9    0.16       0  5197.1     0.1       0
Bank Sta=5000.8,5008.9
Exp/Cntr=0.3,0.1

Type RM Length L Ch R = 1,6604,690,690,690
BEGIN DESCRIPTION:
Live Oak Creek 2 4.0
END DESCRIPTION:
XS GIS Cut Line= 3
      2001554.92     13456407.83      2002375.00     13456025.00
      2002714.62     13455623.12
#Sta/Elev= 30
  4105.3  457.37  4160.6  455.07  4197.0  454.61  4271.1  451.83  4326.1  449.01
  4431.0  446.67  4579.9  445.44  4904.7  447.23  4944.1  446.48  4956.0  445.59
  4978.8  445.70  4988.3  445.04  4996.1  443.41  4997.6  442.45  4998.3  441.65
  5005.0  441.65  5005.7  442.45  5007.6  443.92  5017.5  443.38  5024.0  446.93
  5046.1  446.11  5060.4  446.90  5081.2  446.41  5272.4  450.08  5300.9  451.28
  5358.1  451.27  5386.7  452.46  5393.2  452.06  5457.0  453.46  5536.5  454.09
#Mann=3,-1,0
  4105.3     0.1       0  4997.6    0.07       0  5005.7     0.1       0
Bank Sta=4997.6,5005.7
Exp/Cntr=0.3,0.1

Type RM Length L Ch R = 1,5914,571,571,571
BEGIN DESCRIPTION:
Live Oak Creek 2 3.0
END DESCRIPTION:
XS GIS Cut Line= 3
      2001817.22     13457104.73      2002805.06     13456456.24
      2003538.76     13455318.59
#Sta/Elev= 30
  3888.1  453.34  4334.0  444.07  4520.8  443.22  4665.5  445.11  4818.5  444.24
  4962.0  445.22  4975.9  444.77  4985.0  442.53  4986.9  437.73  4987.6  436.93
  4995.0  437.73  4997.9  438.99  5006.1  439.65  5012.1  442.05  5057.3  444.89
  5163.0  443.89  5286.6  442.86  5343.5  443.75  5534.8  444.49  5555.9  443.49
  5561.8  444.67  5627.6  444.87  5639.8  444.85  5739.7  445.57  5880.4  446.85
  5927.7  446.30  6169.7  451.22  6200.1  450.81  6227.1  452.70  6423.5  457.13
#Mann=9,-1,0
  3888.1     0.1       0  4986.9    0.07       0  4995.0     0.1       0
  5163.0    0.16       0  5343.5     0.1       0  5627.6    0.07       0
  5639.8    0.12       0  5739.7    0.07       0  5927.7     0.1       0
Bank Sta=4986.9,4995
Exp/Cntr=0.3,0.1

Type RM Length L Ch R = 1,5343,622,622,622
BEGIN DESCRIPTION:
Live Oak Creek 2 2.0
END DESCRIPTION:
XS GIS Cut Line= 3
      2002935.27     13457138.57      2003214.35     13456505.29
      2003584.57     13455992.27
#Sta/Elev= 30
  4257.7  445.79  4425.5  443.26  4662.2  441.08  4972.5  443.18  4978.7  443.02
  4987.1  440.90  4989.4  438.04  4990.1  437.24  4996.8  437.24  4997.5  438.04
  4999.6  438.31  5008.1  442.89  5012.9  442.63  5036.4  443.21  5049.9  441.85
  5058.4  443.02  5073.1  443.22  5085.8  442.63  5094.0  441.19  5108.7  442.74
  5122.3  442.52  5159.0  441.84  5286.7  442.95  5416.7  446.20  5437.5  447.26
  5443.7  446.96  5508.7  448.92  5517.3  449.64  5573.7  450.87  5582.4  451.53
#Mann=6,-1,0
  4257.7    0.05       0  4662.2     0.1       0  4989.4    0.07       0
  4997.5     0.1       0  5012.9    0.16       0  5122.3     0.1       0
Bank Sta=4989.4,4997.5
Exp/Cntr=0.3,0.1

Type RM Length L Ch R = 1,4721,255,255,255
BEGIN DESCRIPTION:
Mapping XS 76edf481
END DESCRIPTION:
XS GIS Cut Line= 3
      2003075.04     13457178.89      2003481.28     13456951.47
      2003760.38     13456315.26
#Sta/Elev= 30
  4408.1  444.28  4550.2  441.98  4786.2  440.88  4820.8  440.06  4883.7  440.34
  4957.2  441.36  4971.8  441.15  4979.0  439.05  4990.9  436.78  4991.6  435.98
  4998.7  435.98  4999.5  436.78  5000.8  437.84  5011.8  441.37  5018.5  441.98
  5041.9  441.80  5070.7  440.76  5088.2  441.31  5164.2  441.84  5193.0  441.53
  5274.0  440.27  5284.8  439.74  5291.9  438.75  5306.6  439.28  5315.3  438.88
  5419.7  442.88  5434.8  443.03  5467.7  444.35  5513.1  445.67  5568.4  448.33
#Mann=6,-1,0
  4408.1    0.05       0  4883.7     0.1       0  4990.9    0.07       0
  4999.5     0.1       0  5434.8    0.16       0  5467.7     0.1       0
Bank Sta=4990.9,4999.5
Exp/Cntr=0.3,0.1

Type RM Length L Ch R = 1,4466,304,304,304
BEGIN DESCRIPTION:
Mapping XS 3ade6299
END DESCRIPTION:
XS GIS Cut Line= 3
      2003462.18     13457198.00      2003682.67     13457081.68
      2003960.21     13456354.86
#Sta/Elev= 30
  4571.8  441.90  4634.5  441.92  4710.7  441.35  4819.6  439.74  4867.4  439.74
  4957.9  440.94  4982.6  438.78  4988.8  437.44  4995.2  436.76  4996.0  435.96
  5003.1  435.96  5003.8  436.76  5007.3  437.46  5012.7  439.65  5031.6  440.81
  5042.8  440.19  5067.5  440.01  5106.5  440.80  5122.3  440.17  5201.8  438.99
  5224.3  438.26  5231.9  437.50  5245.7  437.70  5256.4  438.95  5286.7  438.91
  5399.5  441.97  5486.5  444.58  5507.5  446.15  5571.3  450.98  5599.1  452.26
#Mann=6,-1,0
  4571.8    0.05       0  4867.4     0.1       0  4995.2    0.07       0
  5003.8     0.1       0  5399.5    0.16       0  5507.5     0.1       0
Bank Sta=4995.2,5003.8
Exp/Cntr=0.3,0.1

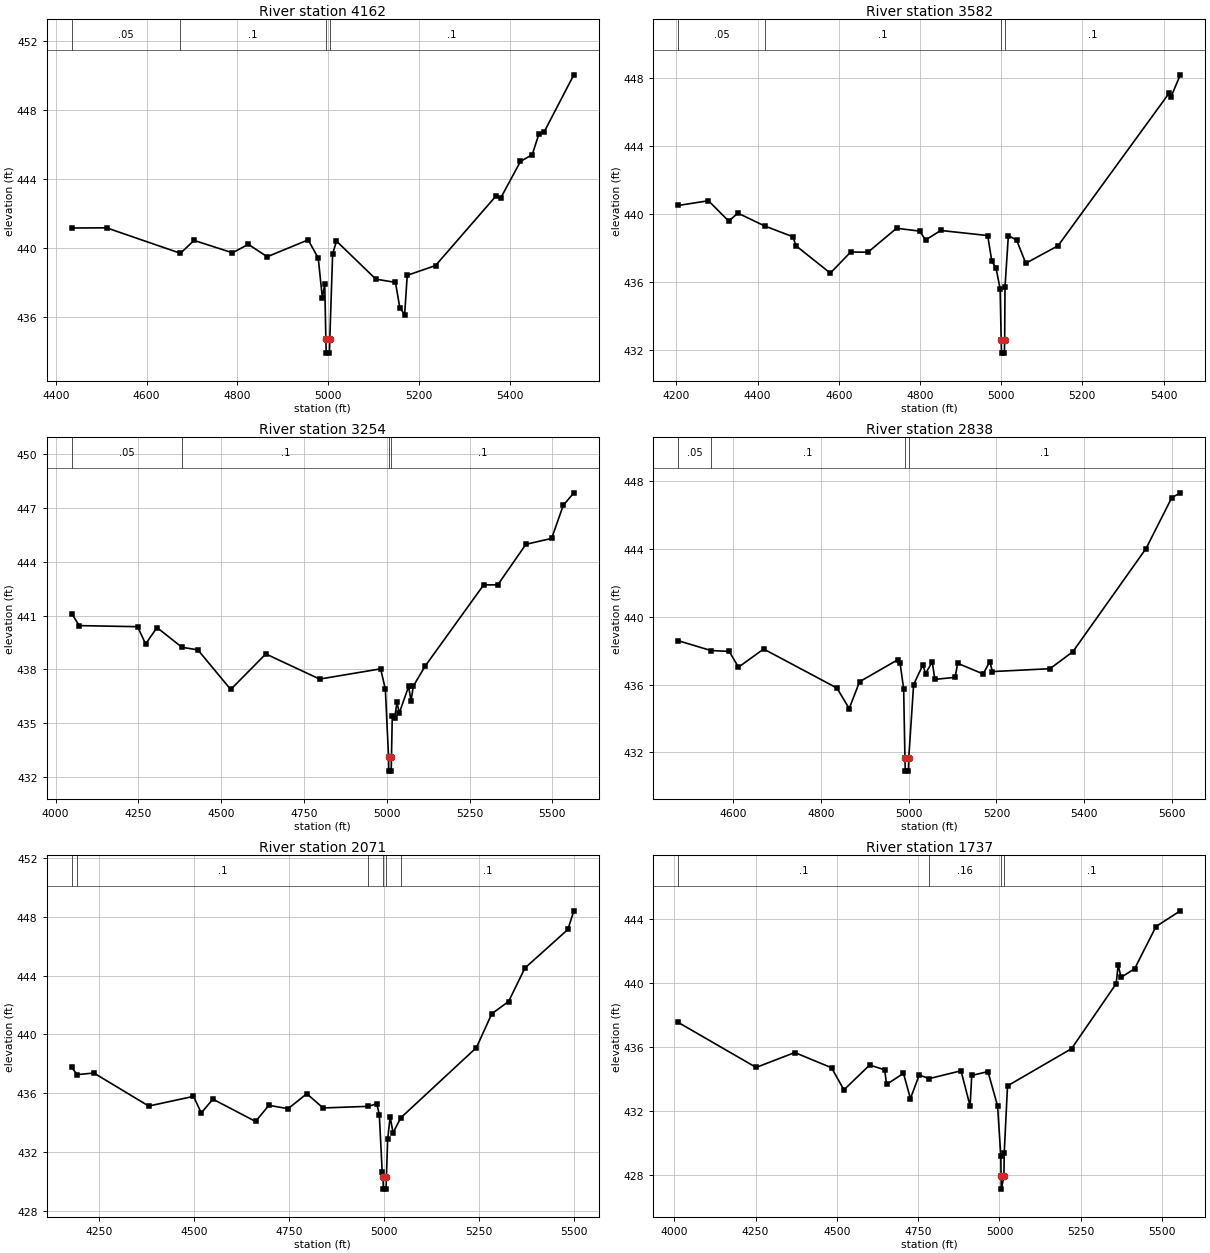
Type RM Length L Ch R = 1,4162,580,580,580
BEGIN DESCRIPTION:
Mapping XS 2dd66fa2
END DESCRIPTION:
XS GIS Cut Line= 3
      2003684.17     13457352.79      2003959.14     13457021.35
      2004179.62     13456382.47
#Sta/Elev= 30
  4435.2  441.16  4511.9  441.17  4674.8  439.69  4704.6  440.44  4789.3  439.72
  4824.4  440.21  4865.9  439.49  4956.2  440.47  4978.4  439.41  4987.4  437.12
  4992.7  437.88  4995.2  434.69  4996.0  433.89  5003.1  433.89  5003.8  434.69
  5010.1  439.65  5018.6  440.40  5105.3  438.19  5148.6  438.00  5158.2  436.52
  5168.8  436.13  5174.5  438.41  5236.9  438.98  5369.8  443.01  5380.3  442.89
  5424.1  445.03  5450.0  445.42  5465.0  446.65  5475.6  446.71  5541.7  450.06
#Mann=4,-1,0
  4435.2    0.05       0  4674.8     0.1       0  4995.2    0.07       0
  5003.8     0.1       0
Bank Sta=4995.2,5003.8
Exp/Cntr=0.3,0.1

Type RM Length L Ch R = 1,3582,328,328,328
BEGIN DESCRIPTION:
Mapping XS 50bf6eeb
END DESCRIPTION:
XS GIS Cut Line= 4
      2003813.26     13457363.65      2004017.07     13457307.98
      2004269.91     13457017.87      2004394.85     13456389.68
#Sta/Elev= 30
  4204.7  440.52  4279.1  440.80  4329.1  439.60  4351.6  440.07  4417.9  439.31
  4487.1  438.68  4494.7  438.15  4579.2  436.54  4629.5  437.78  4672.0  437.77
  4742.5  439.18  4799.4  439.01  4813.9  438.49  4851.1  439.05  4966.9  438.75
  4977.1  437.23  4987.3  436.85  4997.5  435.61  5000.1  432.63  5000.9  431.83
  5008.0  431.83  5008.7  432.63  5009.5  435.71  5017.8  438.75  5038.2  438.48
  5060.7  437.12  5140.2  438.15  5413.4  447.12  5418.5  446.92  5441.3  448.21
#Mann=4,-1,0
  4204.7    0.05       0  4417.9     0.1       0  5000.1    0.07       0
  5008.7     0.1       0
Bank Sta=5000.1,5008.7
Exp/Cntr=0.3,0.1

Type RM Length L Ch R = 1,3254,416,416,416
BEGIN DESCRIPTION:
Mapping XS fad5498b
END DESCRIPTION:
XS GIS Cut Line= 3
      2003763.39     13457428.74      2004092.71     13457338.12
      2004894.78     13456479.81
#Sta/Elev= 30
  4048.8  441.11  4071.2  440.44  4247.5  440.38  4271.8  439.42  4306.2  440.33
  4381.7  439.23  4429.6  439.09  4528.8  436.88  4634.8  438.86  4797.4  437.46
  4981.6  438.03  4995.8  436.90  5005.5  433.13  5006.3  432.33  5013.5  432.33
  5014.3  433.13  5016.8  435.43  5024.1  435.31  5030.9  436.16  5037.9  435.57
  5066.1  437.05  5073.4  436.24  5080.3  437.07  5115.9  438.18  5292.8  442.71
  5335.3  442.71  5420.3  444.97  5498.0  445.30  5533.1  447.14  5565.1  447.84
#Mann=4,-1,0
  4048.8    0.05       0  4381.7     0.1       0  5005.5    0.07       0
  5014.3     0.1       0
Bank Sta=5005.5,5014.3
Exp/Cntr=0.3,0.1

Type RM Length L Ch R = 1,2838,767,767,767
BEGIN DESCRIPTION:
Mapping XS 5f4440cf
END DESCRIPTION:
XS GIS Cut Line= 3
      2004216.09     13457484.88      2004611.92     13457233.15
      2004966.82     13456658.39
#Sta/Elev= 30
  4474.6  438.59  4549.2  438.01  4590.7  437.96  4611.9  437.03  4669.4  438.10
  4836.3  435.80  4864.4  434.59  4887.9  436.17  4974.5  437.46  4980.4  437.26
  4988.5  435.75  4991.4  431.70  4992.2  430.90  4999.4  430.90  5000.2  431.70
  5011.2  436.00  5032.4  437.17  5038.3  436.65  5053.7  437.34  5059.6  436.31
  5105.8  436.43  5111.6  437.26  5169.6  436.63  5185.0  437.36  5190.8  436.77
  5322.1  436.94  5374.2  437.94  5540.9  444.02  5599.7  447.02  5619.2  447.31
#Mann=4,-1,0
  4474.6    0.05       0  4549.2     0.1       0  4991.4    0.07       0
  5000.2     0.1       0
Bank Sta=4991.4,5000.2
Exp/Cntr=0.3,0.1

Type RM Length L Ch R = 1,2071,334,334,334
BEGIN DESCRIPTION:
Mapping XS 06214391
END DESCRIPTION:
XS GIS Cut Line= 4
      2004431.01     13457531.51      2004875.88     13457438.19
      2005375.01     13457012.85      2005510.86     13456848.96
#Sta/Elev= 30
  4177.6  437.75  4191.8  437.26  4235.8  437.37  4380.4  435.12  4498.4  435.78
  4518.9  434.65  4549.5  435.59  4662.0  434.07  4697.1  435.17  4747.7  434.94
  4797.1  435.96  4839.9  434.99  4959.3  435.10  4981.6  435.28  4988.1  434.52
  4995.8  430.61  4998.0  430.26  4998.8  429.46  5006.0  429.46  5006.8  430.26
  5010.1  432.86  5016.7  434.38  5024.4  433.30  5044.7  434.32  5244.0  439.10
  5284.6  441.41  5328.8  442.24  5371.8  444.52  5485.1  447.15  5500.8  448.42
#Mann=6,-1,0
  4177.6    0.05       0  4191.8     0.1       0  4959.3    0.16       0
  4998.0    0.07       0  5006.8    0.16       0  5044.7     0.1       0
Bank Sta=4998,5006.8
Exp/Cntr=0.3,0.1

Type RM Length L Ch R = 1,1737,679,679,679
BEGIN DESCRIPTION:
Mapping XS e960d215
END DESCRIPTION:
XS GIS Cut Line= 5
      2004457.04     13457572.74      2004930.13     13457516.32
      2005192.72     13457353.56      2005522.58     13457284.11
      2005761.27     13456936.92
#Sta/Elev= 30
  4012.2  437.53  4251.8  434.72  4370.4  435.65  4483.5  434.70  4521.7  433.32
  4600.8  434.87  4647.0  434.57  4652.8  433.66  4704.8  434.35  4726.1  432.77
  4753.2  434.25  4783.4  434.02  4881.7  434.51  4909.6  432.31  4914.7  434.22
  4964.5  434.46  4994.1  432.32  5004.1  429.18  5004.8  427.92  5005.6  427.12
  5013.7  427.92  5014.5  429.36  5024.7  433.57  5221.5  435.89  5358.8  439.95
  5364.9  441.13  5373.7  440.34  5415.7  440.89  5481.3  443.52  5556.0  444.50
#Mann=4,-1,0
  4012.2     0.1       0  4783.4    0.16       0  5004.8    0.07       0
  5013.7     0.1       0
Bank Sta=5004.8,5013.7
Exp/Cntr=0.3,0.1

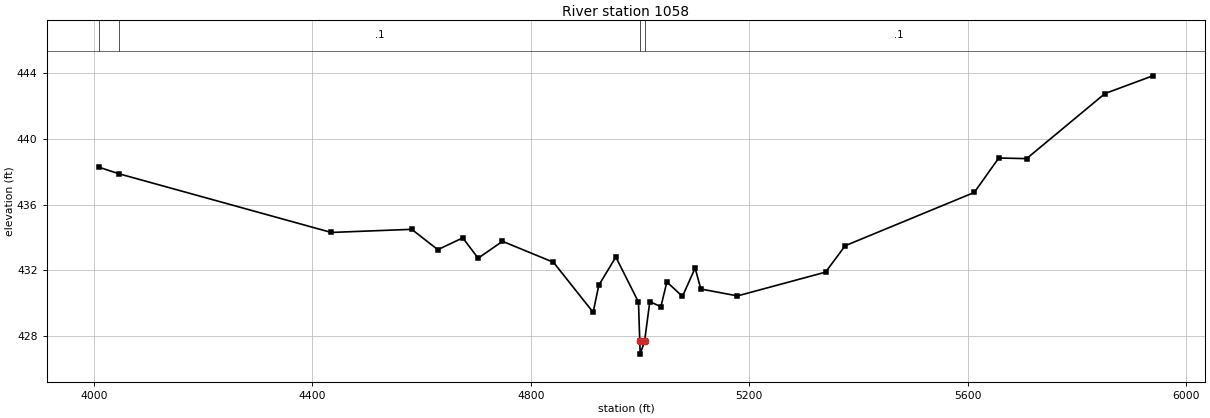
Type RM Length L Ch R = 1,1058,0,0,0
BEGIN DESCRIPTION:
Mapping XS b2b4d1e0
END DESCRIPTION:
XS GIS Cut Line= 4
      2004341.52     13457569.91      2004893.24     13457750.69
      2005457.47     13457594.44      2005886.75     13456964.20
#Sta/Elev= 30
  4010.1  438.27  4045.7  437.88  4434.7  434.30  4582.0  434.49  4629.8  433.25
  4675.5  433.97  4703.6  432.73  4748.2  433.76  4841.5  432.48  4914.2  429.43
  4924.5  431.08  4955.7  432.80  4997.2  430.05  4999.5  427.68  5000.3  426.88
  5008.4  427.68  5017.9  430.08  5038.2  429.77  5049.1  431.28  5077.7  430.40
  5100.9  432.13  5111.3  430.85  5178.4  430.43  5339.7  431.88  5375.6  433.49
  5612.0  436.74  5656.8  438.84  5707.7  438.80  5851.3  442.77  5938.7  443.85
#Mann=4,-1,0
  4010.1    0.05       0  4045.7     0.1       0  4999.5    0.07       0
  5008.4     0.1       0
Bank Sta=4999.5,5008.4
Exp/Cntr=0.3,0.1

Chan Stop Cuts=-1