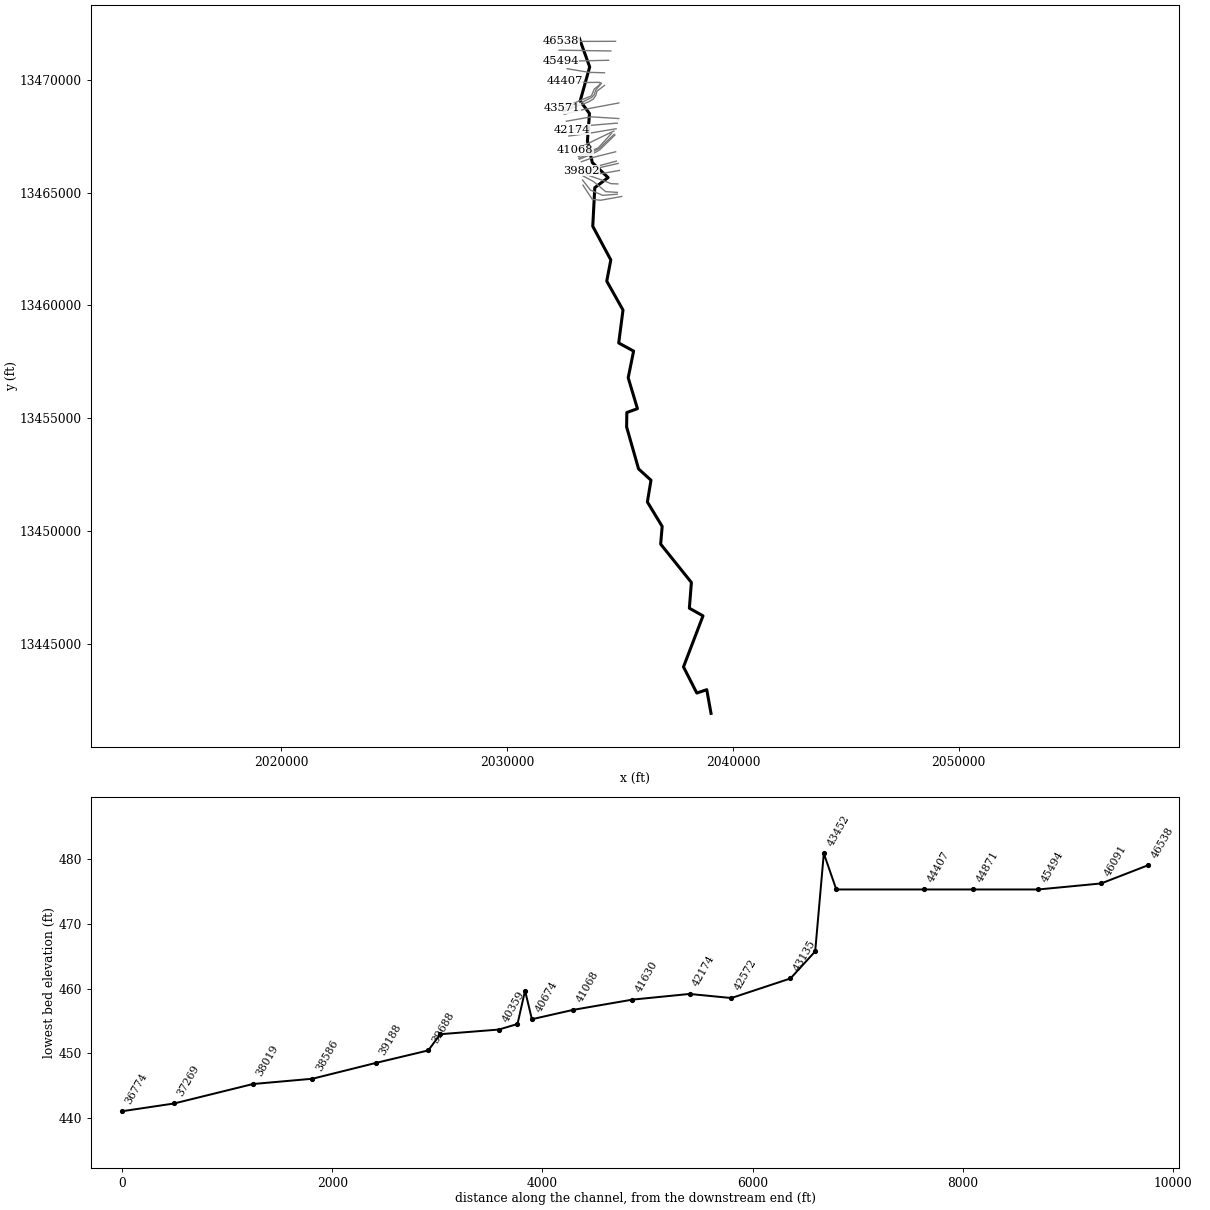
--- Liveoak Creek.prj (project) ---

Proj Title=Liveoak Creek Base Level Engineering
Current Plan=p02
Default Exp/Contr=0.3,0.1
English Units
Geom File=g01
Flow File=f01
Plan File=p01
Plan File=p02
Y Axis Title=Elevation
X Axis Title(PF)=Main Channel Distance
X Axis Title(XS)=Station
BEGIN DESCRIPTION:
Liveoak Creek
END DESCRIPTION:
DSS Export Rating Curves= 0
DSS Export Rating Curve Sorted= 0
DSS Export Volume Flow Curves= 0
DXF OffsetX= 0
DXF OffsetY= 0
DXF ScaleX= 1
DXF ScaleY= 10

--- Liveoak Creek.p02 (plan) ---

Plan Title=Plan 02
Program Version=5.05
Short Identifier=Plan 02
Geom File=g01
Flow File=f01
Subcritical Flow
K Sum by GR= 0
Std Step Tol= 0.01
Critical Tol= 0.01
Num of Std Step Trials= 20
Max Error Tol= 0.3
Flow Tol Ratio= 0.001
Split Flow NTrial= 30
Split Flow Tol= 0.02
Split Flow Ratio= 0.02
Log Output Level= 0
Friction Slope Method= 1
Unsteady Friction Slope Method= 2
Unsteady Bridges Friction Slope Method= 1
Parabolic Critical Depth
Global Vel Dist= 1 , 1 , 1
Global Log Level= 0
CheckData=True
Encroach Param=-1 ,0,0, 0
BEGIN DESCRIPTION:
Multiple Run
END DESCRIPTION:
Computation Interval=1MIN
Output Interval=1HOUR
Instantaneous Interval=1HOUR
Mapping Interval=1HOUR
Computation Time Step Use Courant=        0
Computation Time Step Use Time Series=    0
Computation Time Step Count To Double=0
Computation Time Step Max Doubling=0
Computation Time Step Max Halving=0
Computation Time Step Residence Courant=0
Run HTab= 0
Run UNet= 0
Run Sediment= 0
Run PostProcess= 0
Run WQNet= 0
Run RASMapper= 0
UNET Theta= 1
UNET Theta Warmup= 1
UNET ZTol= 0.02
UNET ZSATol= 0.02
UNET MxIter= 20
UNET Max Iter WO Improvement= 0
UNET MaxInSteps= 0
UNET DtIC= 0
UNET DtMin= 0
UNET MaxCRTS= 20
UNET WFStab= 2
UNET SFStab= 1
UNET WFX= 1
UNET SFX= 1
UNET 1D Methodology=Finite Difference
UNET DSS MLevel= 4
UNET Pardiso=0
UNET DZMax Abort= 100
UNET Use Existing IB Tables=-1
UNET Froude Reduction=False
UNET Froude Limit= 0.8
UNET Froude Power= 4
UNET D1 Cores= 0
UNET D2 Coriolis=0
UNET D2 Cores= 0
UNET D2 Theta= 1
UNET D2 Theta Warmup= 1
UNET D2 Z Tol= 0.01
UNET D2 Volume Tol= 0.01
UNET D2 Max Iterations= 20
UNET D2 Equation= 0
UNET D2 RampUpFraction=0.1
UNET D2 TimeSlices= 1
UNET D2 BCVolumeCheck=0
UNET D1D2 MaxIter= 0
UNET D1D2 ZTol=0.01
UNET D1D2 QTol=0.1
UNET D1D2 MinQTol=1
Write IC File= 0
Write IC File at Fixed DateTime=0
Write IC File at Sim End=0
Echo Input=False
Echo Parameters=False
Echo Output=False
Write Detailed= 0
HDF Write Warmup=0
HDF Write Time Slices=0
HDF Flush=0
HDF Face Node Velocities=0
HDF Compression= 1
HDF Chunk Size= 1
HDF Spatial Parts= 1
HDF Use Max Rows=0
HDF Fixed Rows= 1
Calibration Method= 0
Calibration Iterations= 20
Calibration Max Change=0.05
Calibration Tolerance=0.2
Calibration Maximum=1.5
Calibration Minimum=0.5
Calibration Optimization Method= 1
WQ AD Non Conservative
WQ ULTIMATE=-1
WQ Max Comp Step=1HOUR
WQ Output Interval=15MIN
WQ Output Selected Increments= 0
WQ Output face flow=0
WQ Output face velocity=0
WQ Output face area=0
WQ Output face dispersion=0
WQ Output cell volume=0
WQ Output cell surface area=0
WQ Output cell continuity=0
WQ Output cumulative cell continuity=0
WQ Output face conc=0
WQ Output face dconc_dx=0
WQ Output face courant=0
WQ Output face peclet=0
WQ Output face adv mass=0
WQ Output face disp mass=0
WQ Output cell mass=0
WQ Output cell source sink temp=0
WQ Output nsm pathways=0
WQ Output nsm derived pathways=0
WQ Output MaxMinRange=-1
WQ Daily Max Min Mean=-1
WQ Daily Range=0
WQ Daily Time=0
WQ Create Restart=0
WQ Fixed Restart=0
WQ System Summary=0
WQ Write To DSS=0
WQ Use Fixed Temperature=0
Sorting and Armoring Iterations= 10
XS Update Threshold= 0.02
Bed Roughness Predictor= 0
Hydraulics Update Threshold= 0.02
Energy Slope Method= 1
Volume Change Method= 1
Sediment Retention Method= 0
XS Weighting Method= 0
Number of US Weighted Cross Sections= 1
Number of DS Weighted Cross Sections= 1
Upstream XS Weight=0
Main XS Weight=1
Downstream XS Weight=0
Number of DS XS's Weighted with US Boundary= 1
Upstream Boundary Weight= 1
Weight of XSs Associated with US Boundary= 0
Number of US XS's Weighted with DS Boundary= 1
Downstream Boundary Weight= 0.5
Weight of XSs Associated with DS Boundary= 0.5
Percentile Method= 0
Sediment Output Level= 3
Mass or Volume Output= 0
Output Increment Type= 1
Profile and TS Output Increment= 1
XS Output Flag= 0
XS Output Increment= 10
Write Gradation File= 0
Read Gradation Hotstart= 0
Write HDF5 File= 1
Write Binary Output= 1
Write DSS Sediment File= 0
SV Curve= 0
Specific Gage Flag= 0

--- Liveoak Creek.p01 (plan) ---

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Plan Title=Multiple Run
Short Identifier=Multiple
Geom File=g01
Flow File=f01
Global Vel Dist=  1 , 1 , 1
Encroach Param= -1, 0, 0, 0

--- Liveoak Creek.f01 (steady flow) ---

Flow Title=Multiple
Program Version=5.05
Number of Profiles= 7
Profile Names=10-year,25-year,50-year,1pct_min,100-year,1pct_plu,500-year
River Rch & RM=Liveoak Creek,Reach-1         ,46538
     161     218     263     159     318     634     469
River Rch & RM=Liveoak Creek,Reach-1         ,44871
     279     388     479     295     588    1173     898
River Rch & RM=Liveoak Creek,Reach-1         ,42572
     341     478     592     366     730    1456    1124
River Rch & RM=Liveoak Creek,Reach-1         ,36622
     456     648     810     504    1005    2005    1573
River Rch & RM=Liveoak Creek,Reach-1         ,31998
     603     864    1087     679    1355    2704    2142
River Rch & RM=Liveoak Creek,Reach-1         ,24834
     619     886    1114     696    1389    2771    2192
River Rch & RM=Liveoak Creek,Reach-1         ,24428
     619     886    1114     696    1389    2771    2192
River Rch & RM=Liveoak Creek,Reach-1         ,24324
    1194    1757    2250    1430    2852    5691    4656
River Rch & RM=Liveoak Creek,Reach-1         ,20263
    1194    1757    2250    1430    2852    5691    4656
River Rch & RM=Liveoak Creek,Reach-1         ,16480
    1194    1757    2250    1430    2852    5691    4656
River Rch & RM=Liveoak Creek,Reach-1         ,15921
    1194    1757    2250    1430    2852    5691    4656
River Rch & RM=Liveoak Creek,Reach-1         ,12409
    1183    1737    2221    1409    2812    5610    4577
River Rch & RM=Liveoak Creek,Reach-1         ,8266
    1295    1904    2438    1548    3089    6164    5038
River Rch & RM=Liveoak Creek,Reach-1         ,7030
    1327    1956    2508    1595    3182    6349    5203
River Rch & RM=Liveoak Creek,Reach-1         ,6132
    1327    1956    2508    1595    3182    6349    5203
River Rch & RM=Liveoak Creek,Reach-1         ,4109
    1324    1950    2500    1589    3170    6325    5179
River Rch & RM=Liveoak Creek,Reach-1         ,3440
    1446    2136    2743    1747    3485    6953    5712
River Rch & RM=Liveoak Creek,Reach-1         ,2688
    1421    2095    2686    1707    3406    6796    5566
Boundary for River Rch & Prof#=Liveoak Creek,Reach-1         , 1
Up Type= 0
Dn Type= 3
Dn Slope=0.00174
Boundary for River Rch & Prof#=Liveoak Creek,Reach-1         , 2
Up Type= 0
Dn Type= 3
Dn Slope=0.00174
Boundary for River Rch & Prof#=Liveoak Creek,Reach-1         , 3
Up Type= 0
Dn Type= 3
Dn Slope=0.00174
Boundary for River Rch & Prof#=Liveoak Creek,Reach-1         , 4
Up Type= 0
Dn Type= 3
Dn Slope=0.00174
Boundary for River Rch & Prof#=Liveoak Creek,Reach-1         , 5
Up Type= 0
Dn Type= 3
Dn Slope=0.00174
Boundary for River Rch & Prof#=Liveoak Creek,Reach-1         , 6
Up Type= 0
Dn Type= 3
Dn Slope=0.00174
Boundary for River Rch & Prof#=Liveoak Creek,Reach-1         , 7
Up Type= 0
Dn Type= 3
Dn Slope=0.00174
DSS Import GetInterval= 0
DSS Import GetPeak= 0
DSS Import FillOption= 0

--- Liveoak Creek.g01 (geometry) ---

Geom Title=Existing Conditions
Program Version=5.05

River Reach=Liveoak Creek   ,Reach-1
Reach XY= 30
      2033195.87      13471831.5      2033655.22     13470564.05
      2033233.63      13469058.9      2033645.11     13468500.84
      2033555.52     13467286.77      2033771.82     13466325.44
      2034470.44     13465662.94       2033880.8     13465214.54
       2033790.8     13463504.54       2034590.8     13462014.54
       2034410.8     13461074.54       2035130.8     13459794.54
       2034940.8     13458334.54       2035600.8     13457974.54
       2035360.8     13456794.54       2035770.8     13455424.54
       2035300.8     13455254.54       2035290.8     13454614.54
       2035820.8     13452754.54       2036370.8     13452254.54
      2036210.59     13451290.82      2036866.13     13450207.55
      2036799.46     13449423.01       2038160.8     13447724.54
       2038070.8     13446584.54      2038675.74     13446244.97
       2037810.8     13443984.54       2038400.8     13442824.54
       2038840.8     13442974.54       2039030.8     13441924.54

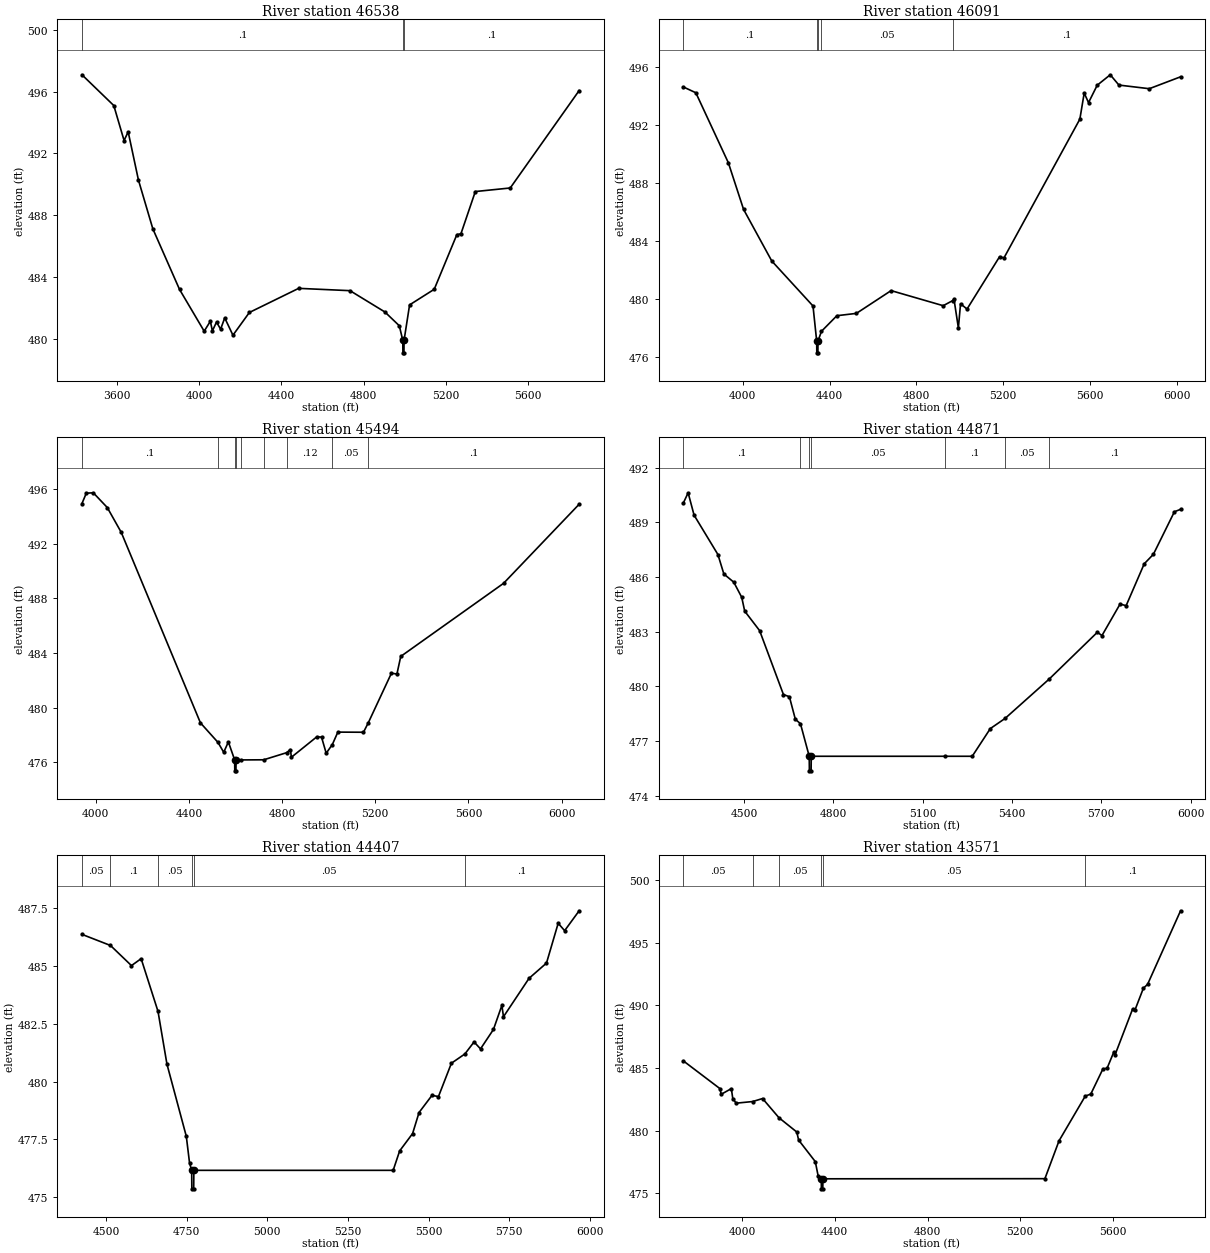
Type RM Length L Ch R = 1 ,46538   ,447,447,447
BEGIN DESCRIPTION:
Mapping XS a2d8f17c
END DESCRIPTION:
XS GIS Cut Line= 2
        2034800.       13471700.      2032379.51     13471692.99
#Sta/Elev= 30
  3428.9  497.09  3583.9   495.1  3633.9  492.84  3653.9   493.4  3703.9  490.28
  3773.9  487.13  3903.9  483.21  4023.9  480.51  4053.9  481.15  4063.9  480.53
  4083.9   481.1  4103.9  480.64  4123.9  481.37  4163.9  480.25  4243.9  481.72
  4483.9  483.28  4733.9  483.13  4903.9  481.75  4973.9  480.86  4990.9  479.91
  4991.4  479.11  4996.4  479.11  4996.9  479.91  5023.9  482.21  5143.9  483.22
  5253.9  486.75  5273.9  486.81  5343.9  489.54  5513.9  489.77  5849.4  496.07
#Mann= 3 ,-1 , 0
  3428.9      .1       0  4990.9     .07       0  4996.9      .1       0
Bank Sta=4990.9,4996.9
XS Rating Curve= 0 ,0
Exp/Cntr=0.3,0.1

Type RM Length L Ch R = 1 ,46091   ,597,597,597
BEGIN DESCRIPTION:
Mapping XS ddf1dd7d
END DESCRIPTION:
XS GIS Cut Line= 2
      2034592.51     13471271.11       2032300.9     13471307.57
#Sta/Elev= 30
  3726.1  494.62  3783.6  494.22  3933.6  489.39  4003.6  486.18  4133.7  482.62
  4323.7  479.52  4340.7  477.09  4341.2  476.29  4346.2  476.29  4346.7  477.09
  4362.4  477.77  4433.7  478.85  4523.7  479.01  4683.7  480.58  4923.8  479.54
  4967.5  479.89  4973.8  479.97  4993.8  478.01  5003.8  479.67  5033.8  479.31
  5183.8  482.92  5203.8  482.83  5553.8   492.4  5573.8   494.2  5593.8  493.54
  5633.8  494.74  5693.9  495.46  5733.9  494.75  5873.9   494.5    6018  495.32
#Mann= 5 ,-1 , 0
  3726.1      .1       0  4340.7     .07       0  4346.7      .1       0
  4362.4     .05       0  4967.5      .1       0
Bank Sta=4340.7,4346.7
XS Rating Curve= 0 ,0
Exp/Cntr=0.3,0.1

Type RM Length L Ch R = 1 ,45494   ,623,623,623
BEGIN DESCRIPTION:
Mapping XS 9aab664a
END DESCRIPTION:
XS GIS Cut Line= 2
      2034493.57     13470859.65      2032359.08      13470812.8
#Sta/Elev= 30
  3940.6  494.96  3959.2  495.72  3989.2  495.75  4049.2  494.67  4109.2  492.85
  4449.3  478.88  4524.5  477.45  4549.3  476.72  4569.3  477.48  4596.3  476.16
  4596.8  475.36  4601.8  475.36  4602.3  476.16  4622.7  476.16    4721  476.17
  4819.2  476.69  4835.2  476.92  4840.2  476.36  4949.4  477.86  4969.4  477.83
  4989.4  476.65  5015.8  477.29  5039.4   478.2  5149.5  478.19  5170.6   478.9
  5269.5  482.52  5293.1  482.46  5309.5  483.75    5751  489.11  6075.6  494.91
#Mann= 9 ,-1 , 0
  3940.6      .1       0  4524.5     .07       0  4596.3     .07       0
  4602.3     .07       0  4622.7     .05       0    4721     .07       0
  4819.2     .12       0  5015.8     .05       0  5170.6      .1       0
Bank Sta=4596.3,4602.3
XS Rating Curve= 0 ,0
Exp/Cntr=0.3,0.1

Type RM Length L Ch R = 1 ,44871   ,464,464,464
BEGIN DESCRIPTION:
Liveoak Creek 62.0
END DESCRIPTION:
XS GIS Cut Line= 3
      2034310.96     13470305.16        2033625.       13470325.
      2032654.67     13470485.72
#Sta/Elev= 30
  4296.5  490.07  4312.5  490.63  4332.5   489.4  4412.5  487.24  4432.5  486.17
  4465.8  485.72  4492.5  484.89  4502.5  484.13  4552.6  483.06  4632.6  479.55
  4652.6  479.43  4672.6  478.19  4689.7  477.95  4719.2  476.16  4719.7  475.36
  4725.5  475.36    4726  476.16  5176.8  476.16  5266.6  476.16  5327.4  477.68
  5377.1  478.24  5525.1   480.4  5686.9  482.97  5702.4  482.79  5763.2  484.52
  5783.5  484.43  5844.3  486.73    5875  487.25  5945.7  489.59  5966.3  489.72
#Mann= 7 ,-1 , 0
  4296.5      .1       0  4689.7     .05       0  4719.2    .033       0
    4726     .05       0  5176.8      .1       0  5377.1     .05       0
  5525.1      .1       0
Bank Sta=4719.2,4726
XS Rating Curve= 0 ,0
Exp/Cntr=0.3,0.1

Type RM Length L Ch R = 1 ,44407   ,836,836,836
BEGIN DESCRIPTION:
Liveoak Creek 61.0
END DESCRIPTION:
XS GIS Cut Line= 3
      2034078.35     13469881.55        2033525.       13469875.
      2032540.16     13469947.52
#Sta/Elev= 30
  4425.8  486.36  4514.2  485.88  4579.2  485.01  4609.2  485.31  4661.5  483.03
  4689.2  480.75  4749.2  477.63  4759.2  476.48  4765.8  476.16  4766.3  475.36
  4772.1  475.36  4772.6  476.16  5390.3  476.16  5410.4     477  5450.5  477.75
  5470.5  478.66  5510.6   479.4  5530.7  479.35  5570.8  480.79  5612.5  481.19
    5641  481.71    5661  481.41  5701.1  482.25  5727.2  483.29  5732.2   482.8
  5811.4  484.46  5865.5  485.12  5901.7  486.84  5921.7  486.52  5966.7  487.38
#Mann= 6 ,-1 , 0
  4425.8     .05       0  4514.2      .1       0  4661.5     .05       0
  4765.8    .033       0  4772.6     .05       0  5612.5      .1       0
Bank Sta=4765.8,4772.6
XS Rating Curve= 0 ,0
Exp/Cntr=0.3,0.1

Type RM Length L Ch R = 1 ,43571   ,119,119,119
BEGIN DESCRIPTION:
Liveoak Creek 60.0
END DESCRIPTION:
XS GIS Cut Line= 6
      2034133.37     13469861.42      2034069.87     13469750.66
      2033856.09     13469582.94      2033734.57      13469287.8
      2033256.25     13469088.89        2032425.       13468725.
#Sta/Elev= 30
  3747.2  485.56  3904.2  483.36  3910.6   482.9    3954  483.35  3960.3  482.56
  3974.8  482.19    4046  482.32  4088.7  482.56  4159.4  481.03  4236.3  479.89
  4244.2  479.25  4316.1  477.53  4328.2  476.41  4341.9  476.16  4342.4  475.36
  4348.4  475.36  4348.9  476.16  5306.2  476.17  5367.2  479.19  5480.1  482.75
  5504.2  482.92  5556.4  484.92  5574.3  484.97  5603.2  486.26  5608.6  486.04
  5684.3  489.69  5694.7  489.62    5731  491.36  5748.9  491.66  5891.2  497.53
#Mann= 6 ,-1 , 0
  3747.2     .05       0    4046      .1       0  4159.4     .05       0
  4341.9    .033       0  4348.9     .05       0  5480.1      .1       0
Bank Sta=4341.9,4348.9
XS Rating Curve= 0 ,0
Exp/Cntr=0.3,0.1

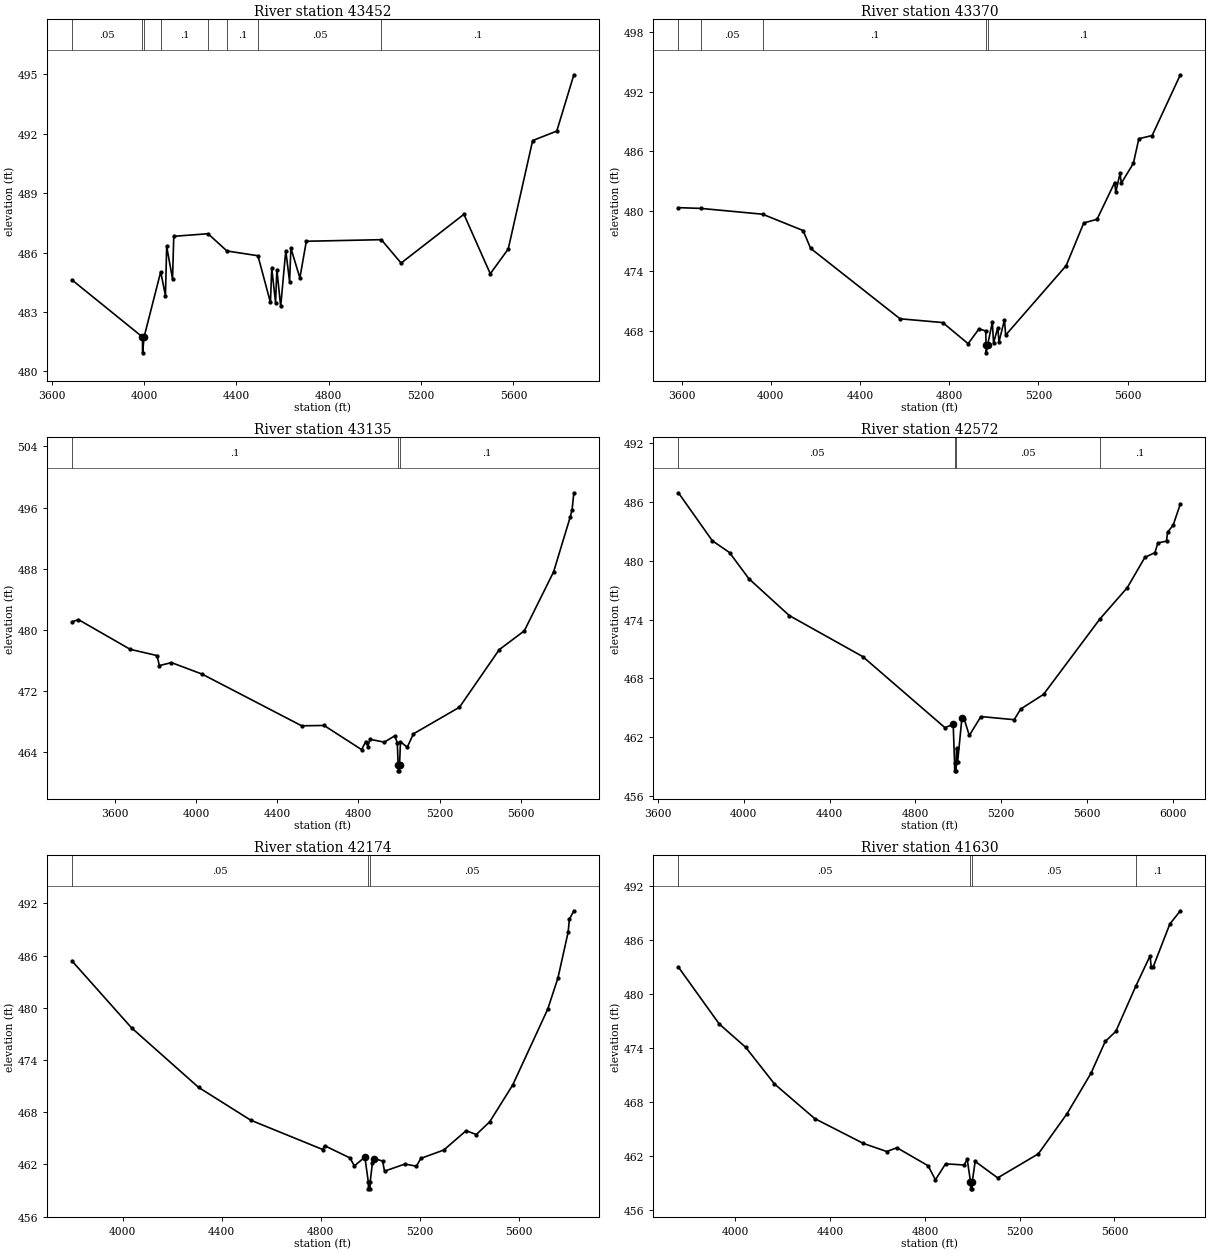
Type RM Length L Ch R = 1 ,43452   ,82,82,82
BEGIN DESCRIPTION:
Mapping XS 2beb5d62
END DESCRIPTION:
XS GIS Cut Line= 6
      2034170.82      13469834.2      2033932.48     13469551.69
      2033852.62     13469329.46      2033744.98     13469214.88
      2033172.07     13468926.69      2032463.72     13468628.07
#Sta/Elev= 30
  3688.2  484.62  3993.6  481.74  3994.1  480.94  4000.6  481.74  4072.6  485.03
  4093.1  483.82  4098.4  486.31  4123.8  484.67  4129.1  486.82  4277.4  486.95
  4359.4  486.08  4493.6  485.84  4547.8  483.48  4553.4  485.21    4570  483.47
  4575.6  485.14  4592.1  483.28  4614.2   486.1  4630.7  484.53  4636.4  486.22
  4675.2  484.72  4703.2  486.57  5027.9  486.65  5113.6  485.47  5385.6  487.93
  5499.8  484.93  5577.6  486.18  5683.2  491.65  5787.8  492.13  5861.7  494.97
#Mann= 8 ,-1 , 0
  3688.2     .05       0  3993.6    .033       0  4000.6     .05       0
  4072.6      .1       0  4277.4     .05       0  4359.4      .1       0
  4493.6     .05       0  5027.9      .1       0
Bank Sta=3993.6,4000.6
XS Rating Curve= 0 ,0
Exp/Cntr=0.3,0.1

Type RM Length L Ch R = 1 ,43370   ,235,235,235
BEGIN DESCRIPTION:
Mapping XS 9ddb594f
END DESCRIPTION:
XS GIS Cut Line= 6
      2034314.45     13469746.14      2033977.62     13469492.66
      2033922.07     13469298.21      2033821.37     13469145.44
      2033613.04     13469020.44        2032495.     13468582.94
#Sta/Elev= 30
  3585.9  480.36    3688  480.28  3963.3   479.7  4144.9  478.06  4178.7  476.27
  4579.5   469.2  4770.9  468.82  4884.8   466.7  4933.7  468.19  4963.6  467.98
  4965.4  466.58  4965.9  465.78  4972.4  466.58  4993.4  468.87  4998.8  466.77
  5017.9  468.31  5023.2  466.87  5047.7   469.1  5053.1  467.56  5324.5  474.54
  5403.2  478.82  5462.9  479.19  5541.7  482.88    5547  481.92  5566.1  483.82
  5571.5  482.81  5625.8  484.81  5650.2  487.28  5709.9   487.6  5836.2   493.7
#Mann= 5 ,-1 , 0
  3585.9      .1       0    3688     .05       0  3963.3      .1       0
  4965.4     .07       0  4972.4      .1       0
Bank Sta=4965.4,4972.4
XS Rating Curve= 0 ,0
Exp/Cntr=0.3,0.1

Type RM Length L Ch R = 1 ,43135   ,563,563,563
BEGIN DESCRIPTION:
Liveoak Creek 59.0
END DESCRIPTION:
XS GIS Cut Line= 3
      2034946.36     13468968.35        2033375.       13468675.
      2032528.15     13468468.82
#Sta/Elev= 30
    3390  481.07  3421.9  481.36  3676.2  477.48  3808.5  476.66  3820.3  475.35
  3879.7  475.74    4031  474.23  4520.4  467.48  4630.8  467.52  4815.6  464.36
  4835.9  465.42  4846.1  464.77  4856.8  465.71  4927.5  465.34  4978.3  466.16
  4991.1  465.29  4995.3  462.39  4995.8  461.59  5001.8  461.59  5002.3  462.39
  5006.8  465.39    5040  464.68  5070.8  466.43  5297.3  469.91  5492.8  477.43
  5616.3  479.89  5760.4   487.6  5842.8  494.82  5851.5  495.75  5860.1  497.94
#Mann= 3 ,-1 , 0
    3390      .1       0  4995.3     .07       0  5002.3      .1       0
Bank Sta=4995.3,5002.3
XS Rating Curve= 0 ,0
Exp/Cntr=0.3,0.1

Type RM Length L Ch R = 1 ,42572   ,398,398,398
BEGIN DESCRIPTION:
Liveoak Creek 58.0
END DESCRIPTION:
XS GIS Cut Line= 3
      2034942.85     13468277.38      2033727.62     13468353.77
      2032621.96     13468159.67
#Sta/Elev= 30
  3695.1  486.94  3853.3  482.04  3933.4  480.84  4023.6  478.17    4212  474.41
  4554.6  470.22  4937.6  462.97  4976.3   463.3  4982.7  459.36  4983.3  458.56
  4989.6  458.56  4990.2  459.36  4991.9  460.88    4997  459.48  5016.9  463.93
  5027.1  463.89  5051.3  462.17  5105.6   464.1  5260.6  463.78  5291.1  464.87
  5397.4  466.36  5660.3  474.06  5788.5  477.27  5869.8  480.34  5916.6  480.83
  5930.7  481.81  5970.9  482.01    5976  482.93  6001.8  483.62  6035.3   485.8
#Mann= 4 ,-1 , 0
  3695.1     .05       0  4982.7     .03       0  4990.2     .05       0
  5660.3      .1       0
Bank Sta=4976.3,5016.9
XS Rating Curve= 0 ,0
Exp/Cntr=0.3,0.1

Type RM Length L Ch R = 1 ,42174   ,544,544,544
BEGIN DESCRIPTION:
Liveoak Creek 57.0
END DESCRIPTION:
XS GIS Cut Line= 3
      2034875.02       13468075.        2033675.       13467975.
        2032875.       13467775.
#Sta/Elev= 30
  3794.8  485.38  4035.7  477.69  4306.6  470.85  4517.3  467.08  4808.3  463.71
  4815.8  464.15  4918.7  462.74  4936.3  461.82  4978.9  462.84  4992.7  459.99
  4993.3  459.19  4999.7  459.19  5000.2  459.99  5009.3  462.13    5017  462.67
  5050.5  462.38  5058.3  461.22  5140.7  462.04  5187.1  461.79  5205.1  462.69
  5297.9  463.65  5388.1  465.87  5429.3  465.43  5483.4  466.89  5576.2  471.11
  5717.9  479.83  5759.2  483.41  5800.4  488.67  5805.6  490.17  5823.6  491.14
#Mann= 3 ,-1 , 0
  3794.8     .05       0  4992.7     .03       0  5000.2     .05       0
Bank Sta=4978.9,5017
XS Rating Curve= 0 ,0
Exp/Cntr=0.3,0.1

Type RM Length L Ch R = 1 ,41630   ,562,562,562
BEGIN DESCRIPTION:
Liveoak Creek 56.0
END DESCRIPTION:
XS GIS Cut Line= 3
      2034825.03       13467825.        2033625.       13467625.
      2032731.06     13467503.07
#Sta/Elev= 30
  3759.1  482.96  3931.5  476.63    4043  474.05  4164.6  469.97  4334.5  466.12
  4539.7  463.36  4638.6  462.46  4681.7  462.88  4813.5  460.87  4843.9  459.31
    4887  461.09  4965.5  460.96  4978.2  461.61  4992.1  459.11  4992.7  458.31
  4999.1  458.31  4999.7  459.11  5011.8  461.36  5106.9  459.53  5278.5   462.2
  5399.6  466.66  5500.5  471.14    5561   474.7  5605.5  475.81  5689.6  480.82
  5750.2  484.21  5755.2  482.94  5762.9  482.95  5833.5  487.74  5877.9  489.22
#Mann= 4 ,-1 , 0
  3759.1     .05       0  4992.1     .03       0  4999.7     .05       0
  5689.6      .1       0
Bank Sta=4992.1,4999.7
XS Rating Curve= 0 ,0
Exp/Cntr=0.3,0.1

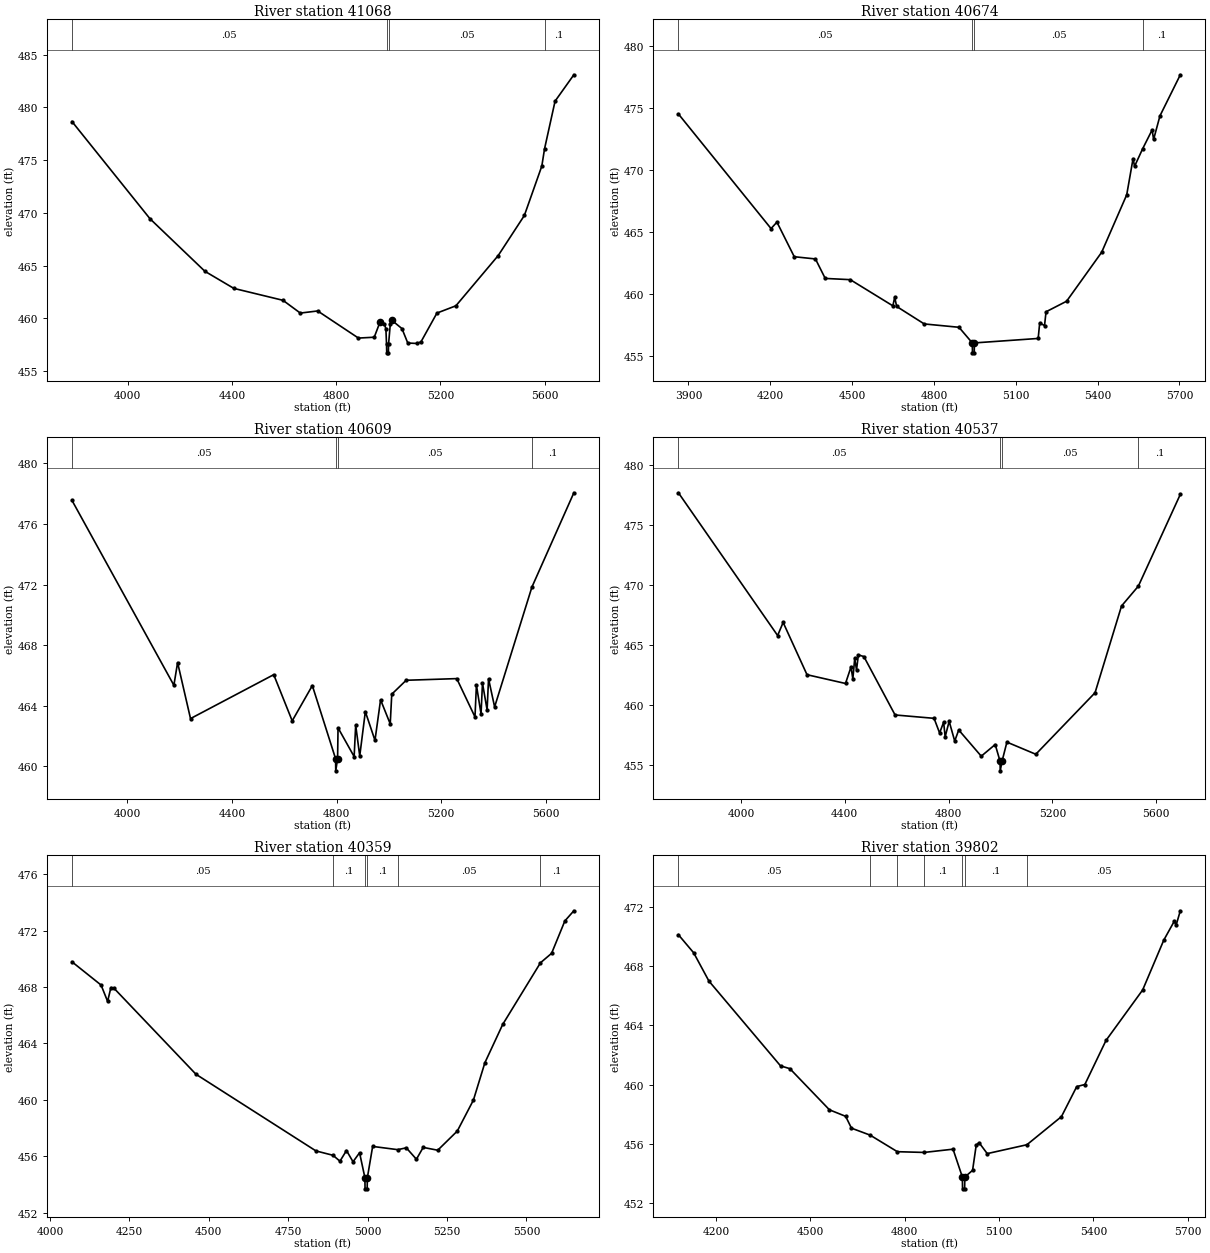
Type RM Length L Ch R = 1 ,41068   ,394,394,394
BEGIN DESCRIPTION:
Liveoak Creek 55.0
END DESCRIPTION:
XS GIS Cut Line= 3
      2034725.02     13467725.01      2033894.29     13467325.99
      2032994.96     13466878.06
#Sta/Elev= 30
  3785.8  478.66  4085.4  469.44  4296.1  464.46  4407.1  462.84  4595.7  461.71
  4662.2   460.5  4728.9   460.7  4885.3  458.13    4946  458.21  4968.3  459.66
  4985.1  459.48  4990.7     459  4993.2  457.53  4993.9  456.73  5000.3  456.73
  5000.9  457.53  5007.5  459.43  5013.1  459.82  5052.3  459.03  5074.7  457.66
  5108.8  457.62  5125.1  457.76  5186.6   460.5  5259.4  461.19  5421.7  465.95
  5522.1  469.75  5589.2  474.44  5599.5  476.06    5640  480.59  5712.1  483.09
#Mann= 4 ,-1 , 0
  3785.8     .05       0  4993.2     .03       0  5000.9     .05       0
  5599.5      .1       0
Bank Sta=4968.3,5013.1
XS Rating Curve= 0 ,0
Exp/Cntr=0.3,0.1

Type RM Length L Ch R = 1 ,40674   ,65,65,65
BEGIN DESCRIPTION:
Liveoak Creek 54.0
END DESCRIPTION:
XS GIS Cut Line= 3
      2034625.03     13467625.03      2034036.65     13466982.24
      2033151.39     13466589.95
#Sta/Elev= 30
  3863.4  474.54  4202.9   465.3  4224.5  465.82    4288  463.03  4365.7  462.85
  4401.5  461.28  4493.4  461.18  4649.4  459.07  4656.2  459.76  4663.3  459.02
  4764.5  457.61  4891.8  457.34  4940.6  456.08  4941.2  455.28  4947.7  455.28
  4948.3  456.08  5182.1  456.44  5187.6  457.68  5205.4  457.48  5210.9  458.59
  5286.2  459.44  5414.8  463.39  5506.6  468.02  5529.9  470.94  5535.4  470.32
  5564.9  471.73  5599.7  473.25  5605.2  472.49  5628.5  474.39  5703.1   477.7
#Mann= 4 ,-1 , 0
  3863.4     .05       0  4940.6    .033       0  4948.3     .05       0
  5564.9      .1       0
Bank Sta=4940.6,4948.3
XS Rating Curve= 0 ,0
Exp/Cntr=0.3,0.1

Type RM Length L Ch R = 1 ,40609   ,72,72,72
BEGIN DESCRIPTION:
Mapping XS 4d76a336
END DESCRIPTION:
XS GIS Cut Line= 6
      2034741.53     13467579.48      2034290.12     13467155.85
      2034078.32     13466950.99      2033946.37     13466891.96
       2033755.4     13466777.38      2033172.07     13466516.96
#Sta/Elev= 30
    3788  477.56  4177.9  465.35  4192.1  466.85  4241.5  463.15  4559.8  466.05
  4630.5     463  4707.5  465.33  4796.4   460.5    4797   459.7  4804.1   460.5
  4805.8  462.54  4867.4  460.64  4873.3  462.72  4888.8  460.68  4910.2  463.61
  4947.1  461.71  4968.5  464.39  5005.4   462.8  5011.3  464.76  5066.4  465.68
  5259.9  465.79  5329.6  463.26  5335.1  465.36  5352.8  463.46  5358.3  465.49
    5376  463.72  5381.5  465.78  5404.7  463.92  5547.3  471.83  5707.8  478.06
#Mann= 4 ,-1 , 0
    3788     .05       0  4796.4    .033       0  4804.1     .05       0
  5547.3      .1       0
Bank Sta=4796.4,4804.1
XS Rating Curve= 0 ,0
Exp/Cntr=0.3,0.1

Type RM Length L Ch R = 1 ,40537   ,178,178,178
BEGIN DESCRIPTION:
Mapping XS 7bde3d82
END DESCRIPTION:
XS GIS Cut Line= 5
      2034772.75     13467548.21      2034113.04     13466902.38
      2033946.37     13466801.69      2033748.46     13466697.52
      2033198.15     13466476.01
#Sta/Elev= 30
  3758.6  477.68  4141.1   465.8  4162.3  466.89  4254.3  462.54  4402.7  461.81
    4424  463.19    4431  462.19  4438.2  463.89  4445.2  462.94  4452.3  464.19
  4473.5  464.05  4593.8  459.19  4744.1  458.91  4765.5  457.69    4781  458.59
  4786.8  457.37  4802.3  458.66  4823.7  457.02  4839.2  457.94    4926  455.76
  4979.8  456.73  4998.5  455.34  4999.1  454.54  5006.2  455.34  5024.9  456.93
  5136.3  455.92  5364.7  461.04  5466.8  468.26  5531.6  469.91  5693.4  477.55
#Mann= 4 ,-1 , 0
  3758.6     .05       0  4998.5    .033       0  5006.2     .05       0
  5531.6      .1       0
Bank Sta=4998.5,5006.2
XS Rating Curve= 0 ,0
Exp/Cntr=0.3,0.1

Type RM Length L Ch R = 1 ,40359   ,557,557,557
BEGIN DESCRIPTION:
Liveoak Creek 53.0
END DESCRIPTION:
XS GIS Cut Line= 3
      2034804.05     13466805.17        2033875.       13466575.
      2033288.36      13466364.8
#Sta/Elev= 30
  4069.1  469.79  4160.8  468.14  4181.4  466.98  4191.7  467.96    4202   467.9
  4459.6  461.81  4837.4  456.37  4891.1  456.06  4912.9  455.64  4933.5   456.4
  4954.1   455.6  4974.7  456.24  4991.4  454.48    4992  453.68  4998.6  453.68
  4999.3  454.48  5015.9  456.69  5094.8  456.46  5121.8  456.59  5153.7  455.78
    5175  456.62  5220.8  456.42  5282.4  457.78  5333.2  459.98  5369.3  462.63
  5425.5  465.35  5544.3  469.72  5579.3  470.39  5621.1  472.69  5649.4  473.41
#Mann= 6 ,-1 , 0
  4069.1     .05       0  4891.1      .1       0  4991.4     .07       0
  4999.3      .1       0  5094.8     .05       0  5544.3      .1       0
Bank Sta=4991.4,4999.3
XS Rating Curve= 0 ,0
Exp/Cntr=0.3,0.1

Type RM Length L Ch R = 1 ,39802   ,114,114,114
BEGIN DESCRIPTION:
Liveoak Creek 52.0
END DESCRIPTION:
XS GIS Cut Line= 3
      2034838.76     13466391.97      2033609.57     13466065.57
      2033298.58     13465975.73
#Sta/Elev= 30
  4080.5  470.13    4129  468.91  4177.5     467  4405.1  461.27  4434.9  461.08
  4560.6   458.3  4612.1  457.86  4630.6  457.06  4689.9  456.59  4776.5  455.47
  4861.6  455.42  4953.5  455.64  4983.1  453.76  4983.7  452.96  4990.3  452.96
    4991  453.76  5015.6  454.21  5027.2  455.92  5036.3  456.08  5062.2  455.34
  5188.3  455.94  5298.1  457.84  5346.7  459.87  5372.5  460.01  5439.8  462.99
  5556.3   466.4  5623.5  469.77  5657.2  471.06  5662.4  470.76    5676  471.75
#Mann= 7 ,-1 , 0
  4080.5     .05       0  4689.9      .1       0  4776.5     .05       0
  4861.6      .1       0  4983.1     .07       0    4991      .1       0
  5188.3     .05       0
Bank Sta=4983.1,4991
XS Rating Curve= 0 ,0
Exp/Cntr=0.3,0.1

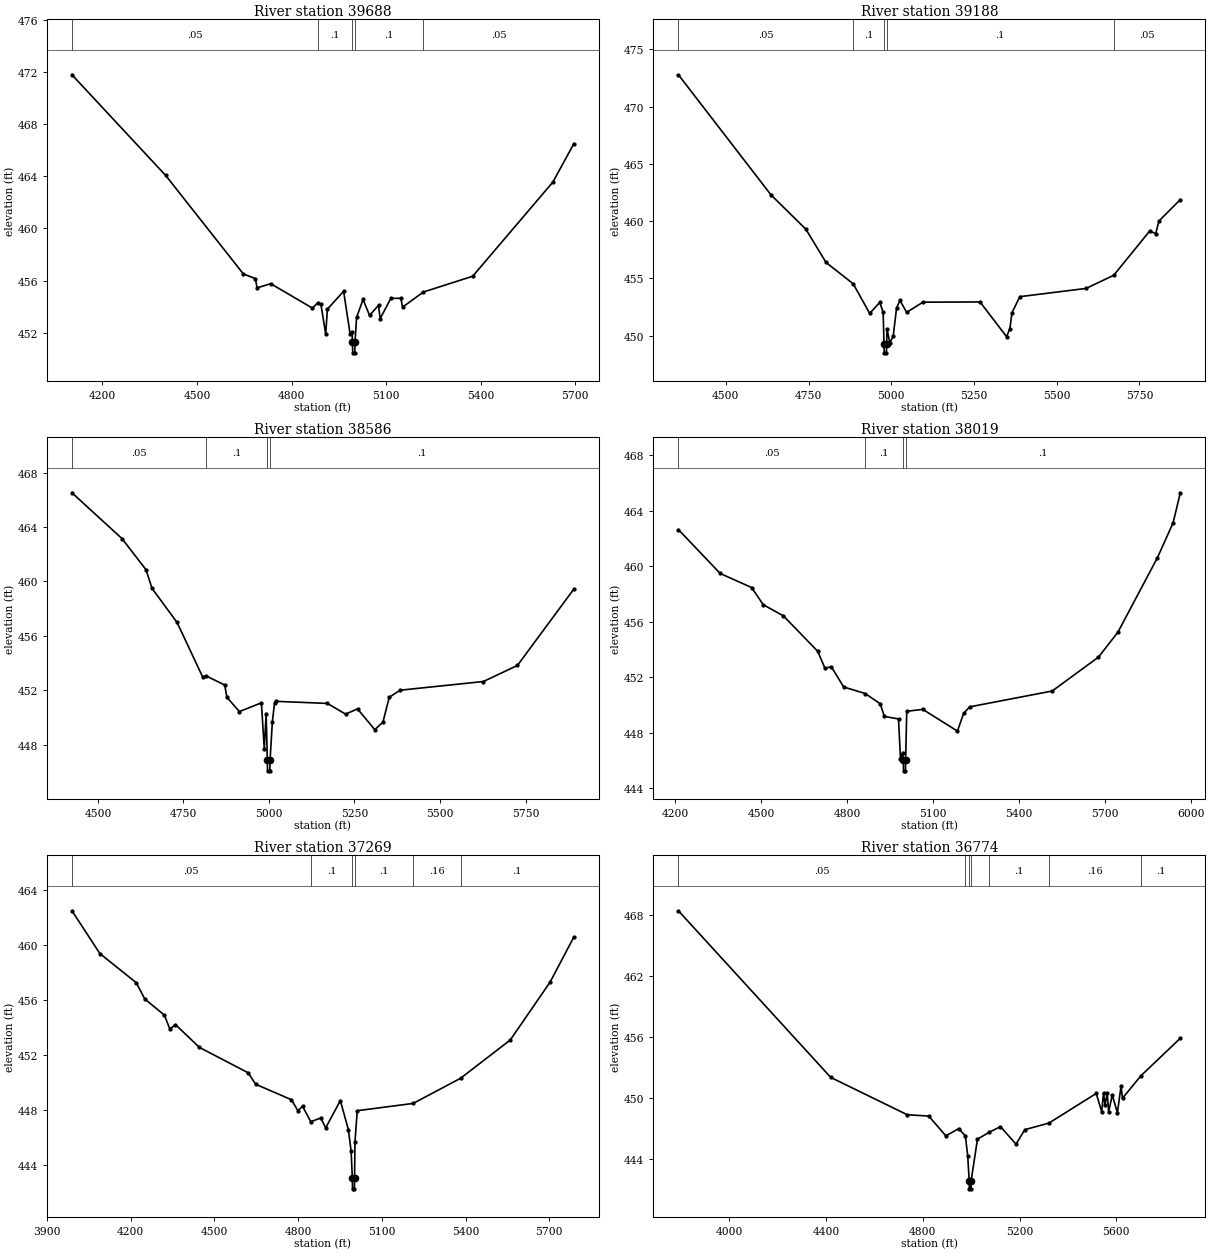
Type RM Length L Ch R = 1 ,39688   ,500,500,500
BEGIN DESCRIPTION:
Mapping XS 75f5db1f
END DESCRIPTION:
XS GIS Cut Line= 4
      2034915.08     13466287.79      2034248.46     13466138.49
      2033946.37     13466065.57      2033378.46     13465878.58
#Sta/Elev= 30
  4103.6   471.8  4400.9  464.07  4647.2  456.51  4685.5  456.15  4690.6  455.44
    4734  455.76  4866.5  453.88  4882.7  454.29  4893.2  454.18  4908.4  451.88
  4913.7   453.8  4965.2  455.18  4985.7  451.91  4992.1  452.07  4993.3  451.25
    4994  450.45  5000.6  450.45  5001.3  451.25  5006.3  453.17  5026.9  454.55
  5047.5  453.32  5075.9   454.1  5081.1  453.08    5115  454.63  5146.8  454.64
  5152.1  453.96  5218.1  455.12  5374.5  456.33  5628.8  463.56  5695.4  466.51
#Mann= 5 ,-1 , 0
  4103.6     .05       0  4882.7      .1       0  4993.3     .07       0
  5001.3      .1       0  5218.1     .05       0
Bank Sta=4993.3,5001.3
XS Rating Curve= 0 ,0
Exp/Cntr=0.3,0.1

Type RM Length L Ch R = 1 ,39188   ,602,602,602
BEGIN DESCRIPTION:
Mapping XS 74bf0982
END DESCRIPTION:
XS GIS Cut Line= 3
      2034974.14     13465978.77      2034185.96     13465839.88
      2033470.63      13465874.6
#Sta/Elev= 30
  4356.9  472.77  4636.6  462.29  4741.9   459.3  4802.8   456.4  4885.1  454.53
  4934.8  451.95  4965.3  452.91  4975.4  452.07  4978.1  449.31  4978.7  448.51
  4985.4  448.51  4986.1  449.31  4987.2   450.6  4995.7  449.38  5005.9  449.97
    5016  452.41  5026.2  453.09  5046.5  452.04  5095.6  452.93  5268.3  452.95
  5348.4  449.92  5358.4  450.61  5364.7  452.01  5388.5  453.41  5588.7  454.13
  5672.3  455.28  5781.2  459.15  5798.9   458.9    5809  460.02  5873.4  461.88
#Mann= 5 ,-1 , 0
  4356.9     .05       0  4885.1      .1       0  4978.1     .07       0
  4986.1      .1       0  5672.3     .05       0
Bank Sta=4978.1,4986.1
XS Rating Curve= 0 ,0
Exp/Cntr=0.3,0.1

Type RM Length L Ch R = 1 ,38586   ,567,567,567
BEGIN DESCRIPTION:
Liveoak Creek 51.0
END DESCRIPTION:
XS GIS Cut Line= 4
       2034901.2     13465381.55      2034609.57     13465391.96
      2034102.62     13465586.41       2033505.4     13465794.74
#Sta/Elev= 30
    4424  466.52  4570.3  463.15  4640.3  460.87  4658.1  459.49  4731.4  456.98
  4806.4  452.96  4816.4  453.05  4870.7  452.38  4876.9  451.48  4913.5  450.43
  4977.8  451.07  4986.3  447.68  4991.7  450.28  4995.2  446.87  4995.8  446.07
  5002.5  446.07  5003.2  446.87  5009.9  449.68  5016.4  451.09  5021.7  451.18
  5170.5  451.03  5224.1  450.24  5258.8  450.63  5309.2   449.1  5333.1  449.65
  5351.6  451.48  5383.4     452  5626.9  452.64  5726.3  453.82  5891.3  459.44
#Mann= 4 ,-1 , 0
    4424     .05       0  4816.4      .1       0  4995.2     .07       0
  5003.2      .1       0
Bank Sta=4995.2,5003.2
XS Rating Curve= 0 ,0
Exp/Cntr=0.3,0.1

Type RM Length L Ch R = 1 ,38019   ,750,750,750
BEGIN DESCRIPTION:
Liveoak Creek 50.0
END DESCRIPTION:
XS GIS Cut Line= 4
      2034880.38     13465005.68      2034363.91      13465040.4
      2033817.03     13465491.79      2033352.66     13465739.17
#Sta/Elev= 30
  4210.3  462.63    4356  459.47  4466.3  458.45  4506.4  457.22  4577.2  456.41
  4696.8  453.86  4721.9  452.65  4744.5  452.74  4787.5  451.29  4862.6  450.82
  4915.2  450.08  4929.5  449.17    4979  448.99  4985.9   446.1  4993.4  446.57
  4995.8  446.05  4996.5  445.25  5003.2  445.25  5003.9  446.05  5007.7  449.54
  5063.7  449.68  5184.9  448.11  5206.3  449.39  5227.9  449.86  5515.7     451
  5677.3  453.44  5745.3  455.24  5883.4  460.61  5937.9  463.11  5963.2  465.28
#Mann= 4 ,-1 , 0
  4210.3     .05       0  4862.6      .1       0  4995.8     .07       0
  5003.9      .1       0
Bank Sta=4995.8,5003.9
XS Rating Curve= 0 ,0
Exp/Cntr=0.3,0.1

Type RM Length L Ch R = 1 ,37269   ,495,495,495
BEGIN DESCRIPTION:
Liveoak Creek 49.0
END DESCRIPTION:
XS GIS Cut Line= 4
      2034875.03       13464925.      2034229.36     13464875.47
      2033686.82     13465109.84      2033340.77     13465551.06
#Sta/Elev= 30
  3989.1  462.49  4089.4  459.37  4219.8  457.25  4249.9  456.07  4320.5  454.89
  4340.2  453.87  4360.2   454.2  4446.1  452.54    4621  450.69  4647.5  449.86
  4775.9  448.73  4799.4  447.92  4815.7  448.26  4845.1  447.13  4881.1   447.4
  4898.8  446.68  4951.3  448.67  4980.2  446.54    4990  444.97  4994.2  443.04
  4994.9  442.24  5001.6  442.24  5002.3  443.04  5003.7  445.66  5011.8  447.93
  5212.3  448.46  5382.1  450.29  5560.5  453.08  5703.4   457.3  5788.4  460.58
#Mann= 6 ,-1 , 0
  3989.1     .05       0  4845.1      .1       0  4994.2     .07       0
  5002.3      .1       0  5212.3     .16       0  5382.1      .1       0
Bank Sta=4994.2,5002.3
XS Rating Curve= 0 ,0
Exp/Cntr=0.3,0.1

Type RM Length L Ch R = 1 ,36774   ,152,152,152
BEGIN DESCRIPTION:
Liveoak Creek 48.0
END DESCRIPTION:
XS GIS Cut Line= 4
      2035074.97     13464824.99      2034138.21     13464658.46
      2033769.29     13464697.52      2033356.97     13465326.84
#Sta/Elev= 30
  3789.7  468.44  4419.4  452.02  4735.8  448.34  4824.8  448.21  4895.2  446.26
  4948.1  446.97  4975.9  446.27  4985.7  444.27  4991.7  441.84  4992.4  441.04
  4999.1  441.04  4999.8  441.84  5025.9  445.94    5075  446.62  5121.1  447.17
  5185.3  445.44  5221.5  446.87  5321.4  447.52  5516.9  450.44  5539.5  448.63
  5547.1  450.51  5553.1  449.31  5562.2  450.44  5568.2  448.65  5583.3  450.28
  5604.4  448.53  5619.5  451.16  5625.5  449.97  5700.8  452.16  5864.5  455.88
#Mann= 7 ,-1 , 0
  3789.7     .05       0  4975.9     .12       0  4991.7     .07       0
  4999.8     .12       0    5075      .1       0  5321.4     .16       0
  5700.8      .1       0
Bank Sta=4991.7,4999.8
XS Rating Curve= 0 ,0
Exp/Cntr=0.3,0.1