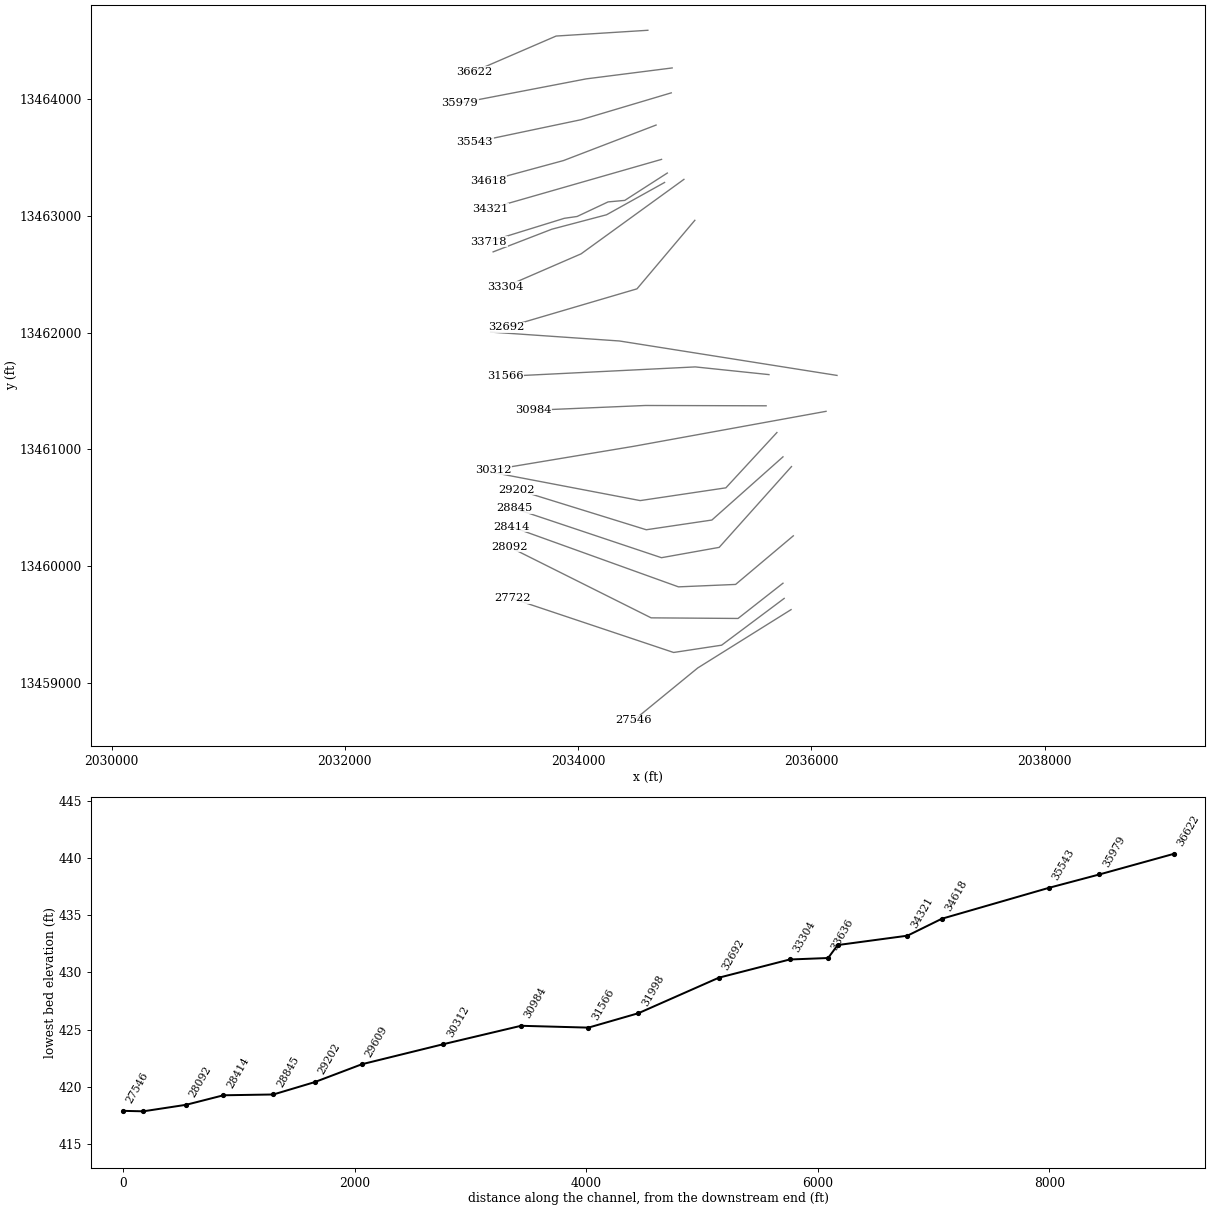
HEC-RAS study Liveoak Creek.prj: Liveoak Creek Base Level Engineering

--- Liveoak Creek.g01 (geometry) --- (continued)

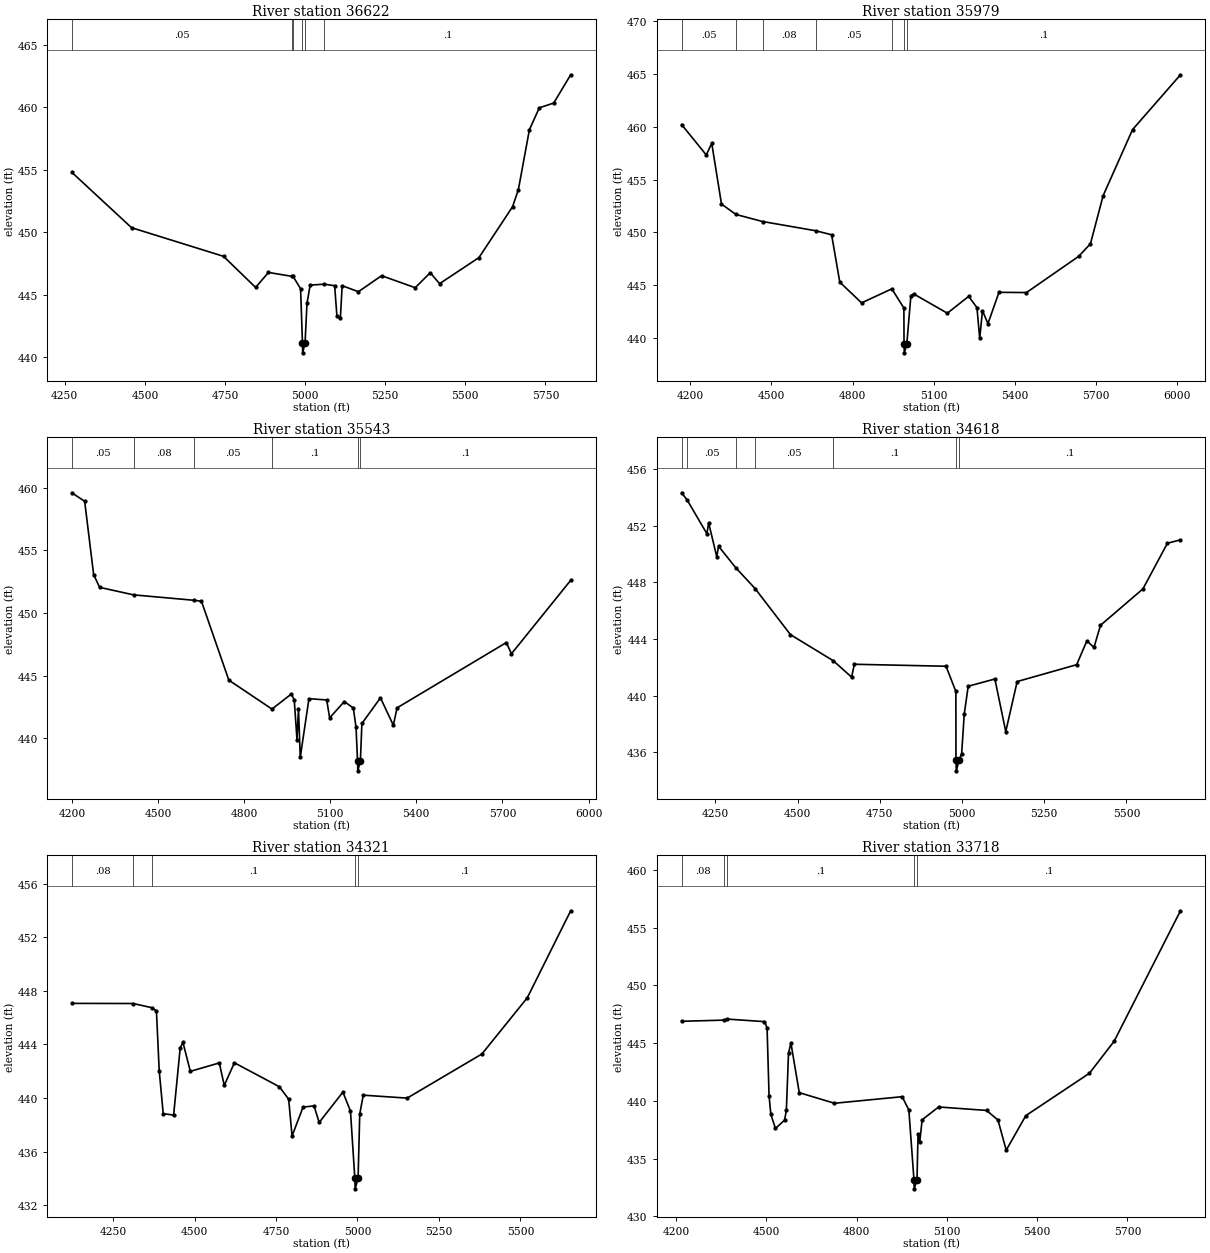
Type RM Length L Ch R = 1 ,36622   ,643,643,643
BEGIN DESCRIPTION:
Liveoak Creek 47.0
END DESCRIPTION:
XS GIS Cut Line= 3
      2034597.46     13464591.62      2033810.96     13464542.14
      2033105.18     13464237.43
#Sta/Elev= 30
  4271.9   454.8  4458.3  450.37  4745.3  448.08  4845.5  445.59  4885.6  446.79
  4958.6  446.48  4961.7   446.5  4985.8  445.49  4991.7  441.16  4992.4  440.36
  4999.8  441.16  5005.8  444.32  5015.8  445.78    5060  445.85  5092.1  445.73
  5099.1  443.34    5110  443.14  5115.6  445.73  5166.3  445.25  5238.6  446.53
  5343.5  445.57  5390.5  446.77  5419.5  445.89  5542.5  447.98  5647.4  452.05
  5665.5  453.42  5699.9  458.21  5730.9  459.96  5775.8  460.34  5828.7   462.6
#Mann= 6 ,-1 , 0
  4271.9     .05       0  4958.6      .1       0  4961.7     .12       0
  4991.7     .07       0  4999.8     .12       0    5060      .1       0
Bank Sta=4991.7,4999.8
XS Rating Curve= 0 ,0
Exp/Cntr=0.3,0.1

Type RM Length L Ch R = 1 ,35979   ,436,436,436
BEGIN DESCRIPTION:
Liveoak Creek 46.0
END DESCRIPTION:
XS GIS Cut Line= 3
      2034805.75      13464268.7      2034068.77     13464174.95
      2032985.44     13463966.62
#Sta/Elev= 30
  4167.5  460.22    4259  457.33  4279.1  458.44  4315.1  452.68  4368.3  451.69
    4467  451.02  4664.4  450.14  4722.7  449.76  4752.9  445.27  4833.6   443.3
  4945.4  444.63  4990.1  442.81  4990.7  439.36  4991.7  438.56  5000.7  439.36
  5016.1  443.99  5026.3  444.15    5151  442.32  5229.9  443.92  5260.5  442.85
  5270.7  439.93  5280.9  442.56  5301.2  441.33    5342   444.3  5443.8  444.28
  5637.3  447.72  5680.5  448.91  5727.4  453.47  5836.3  459.74  6013.6  464.94
#Mann= 7 ,-1 , 0
  4167.5     .05       0  4368.3      .1       0    4467     .08       0
  4664.4     .05       0  4945.4      .1       0  4990.7     .07       0
  5000.7      .1       0
Bank Sta=4990.7,5000.7
XS Rating Curve= 0 ,0
Exp/Cntr=0.3,0.1

Type RM Length L Ch R = 1 ,35543   ,925,925,925
BEGIN DESCRIPTION:
Liveoak Creek 45.0
END DESCRIPTION:
XS GIS Cut Line= 3
      2034797.91     13464055.15        2034025.       13463825.
      2033113.08     13463633.29
#Sta/Elev= 30
  4199.6  459.59  4244.4  458.91  4275.7  453.06  4296.5  452.04  4414.7  451.44
  4623.9  451.01  4651.3  450.93  4746.8  444.63  4897.1  442.32  4964.3  443.52
  4974.7  443.06  4984.2  439.89  4989.5  442.35  4995.6  438.46  5025.9  443.15
  5087.8  443.05    5098  441.62  5149.1  442.92  5180.5  442.41    5190  440.87
  5195.2  438.19  5196.2  437.39  5205.2  438.19  5210.4  441.17  5275.1  443.22
  5319.9  441.03    5333  442.42  5713.6  447.63  5731.6  446.74  5937.9   452.6
#Mann= 6 ,-1 , 0
  4199.6     .05       0  4414.7     .08       0  4623.9     .05       0
  4897.1      .1       0  5195.2     .07       0  5205.2      .1       0
Bank Sta=5195.2,5205.2
XS Rating Curve= 0 ,0
Exp/Cntr=0.3,0.1

Type RM Length L Ch R = 1 ,34618   ,297,297,297
BEGIN DESCRIPTION:
Liveoak Creek 44.0
END DESCRIPTION:
XS GIS Cut Line= 3
      2034667.76     13463779.13        2033875.       13463475.
      2033230.34     13463299.98
#Sta/Elev= 30
  4147.1  454.31  4163.8  453.81  4224.1  451.42  4229.4  452.19  4254.1  449.79
  4259.4  450.54  4311.9  449.02  4370.7  447.55  4478.2   444.3  4608.4  442.46
  4664.2   441.3  4672.3  442.21  4951.2  442.07  4981.2  440.29  4981.5  435.49
  4982.5  434.69  4991.5  435.49  4998.8   435.9  5006.6  438.68  5018.7  440.66
  5099.8  441.17  5132.9  437.46  5167.6  440.99  5348.5  442.18  5379.6  443.86
  5401.2   443.4    5421  444.96  5550.1  447.53  5624.5  450.75  5664.2  450.99
#Mann= 7 ,-1 , 0
  4147.1     .08       0  4163.8     .05       0  4311.9     .08       0
  4370.7     .05       0  4608.4      .1       0  4981.5     .07       0
  4991.5      .1       0
Bank Sta=4981.5,4991.5
XS Rating Curve= 0 ,0
Exp/Cntr=0.3,0.1

Type RM Length L Ch R = 1 ,34321   ,603,603,603
BEGIN DESCRIPTION:
Mapping XS f59c600b
END DESCRIPTION:
XS GIS Cut Line= 2
      2034714.62     13463484.85      2033243.21     13463062.96
#Sta/Elev= 30
  4123.5  447.07    4312  447.06  4370.2  446.74  4383.2   446.5  4391.7  442.04
    4404  438.83  4435.9  438.72    4456  443.72  4464.4  444.17  4487.2  441.99
  4576.1  442.62  4591.2  440.94  4622.4  442.63  4760.4  440.84  4788.9  439.91
  4799.3  437.16  4833.1  439.32  4866.8  439.41  4882.5  438.17  4955.3  440.44
  4978.5  439.02  4991.9  434.01  4992.9  433.21  5001.9  434.01    5007  438.81
  5017.8  440.21  5152.4  439.99  5381.9  443.29  5521.1  447.49  5654.2  453.99
#Mann= 5 ,-1 , 0
  4123.5     .08       0    4312     .05       0  4370.2      .1       0
  4991.9     .07       0  5001.9      .1       0
Bank Sta=4991.9,5001.9
XS Rating Curve= 0 ,0
Exp/Cntr=0.3,0.1

Type RM Length L Ch R = 1 ,33718   ,82,82,82
BEGIN DESCRIPTION:
Mapping XS d12f46d9
END DESCRIPTION:
XS GIS Cut Line= 6
      2034764.06     13463367.65       2034399.5     13463133.28
      2034256.27     13463120.26      2033990.64     13462995.26
      2033881.27     13462979.64      2033234.27     13462779.56
#Sta/Elev= 30
  4217.8   446.9  4358.2     447  4369.6  447.09  4493.4  446.87    4502  446.34
  4508.6  440.44  4514.6  438.83  4529.8  437.62  4560.2  438.34  4566.1  439.19
  4573.3  444.14  4581.3  445.02    4609  440.72    4726   439.8  4951.1  440.37
  4973.3  439.22  4990.3  433.19  4991.3  432.39  5000.4  433.19  5003.9  437.13
  5009.5  436.43  5017.5  438.37  5072.3  439.48  5231.7  439.18  5269.6  438.35
    5297  435.74  5362.2  438.73  5573.7   442.4  5655.7  445.17  5876.3  456.47
#Mann= 5 ,-1 , 0
  4217.8     .08       0  4358.2     .05       0  4369.6      .1       0
  4990.3     .07       0  5000.4      .1       0
Bank Sta=4990.3,5000.4
XS Rating Curve= 0 ,0
Exp/Cntr=0.3,0.1

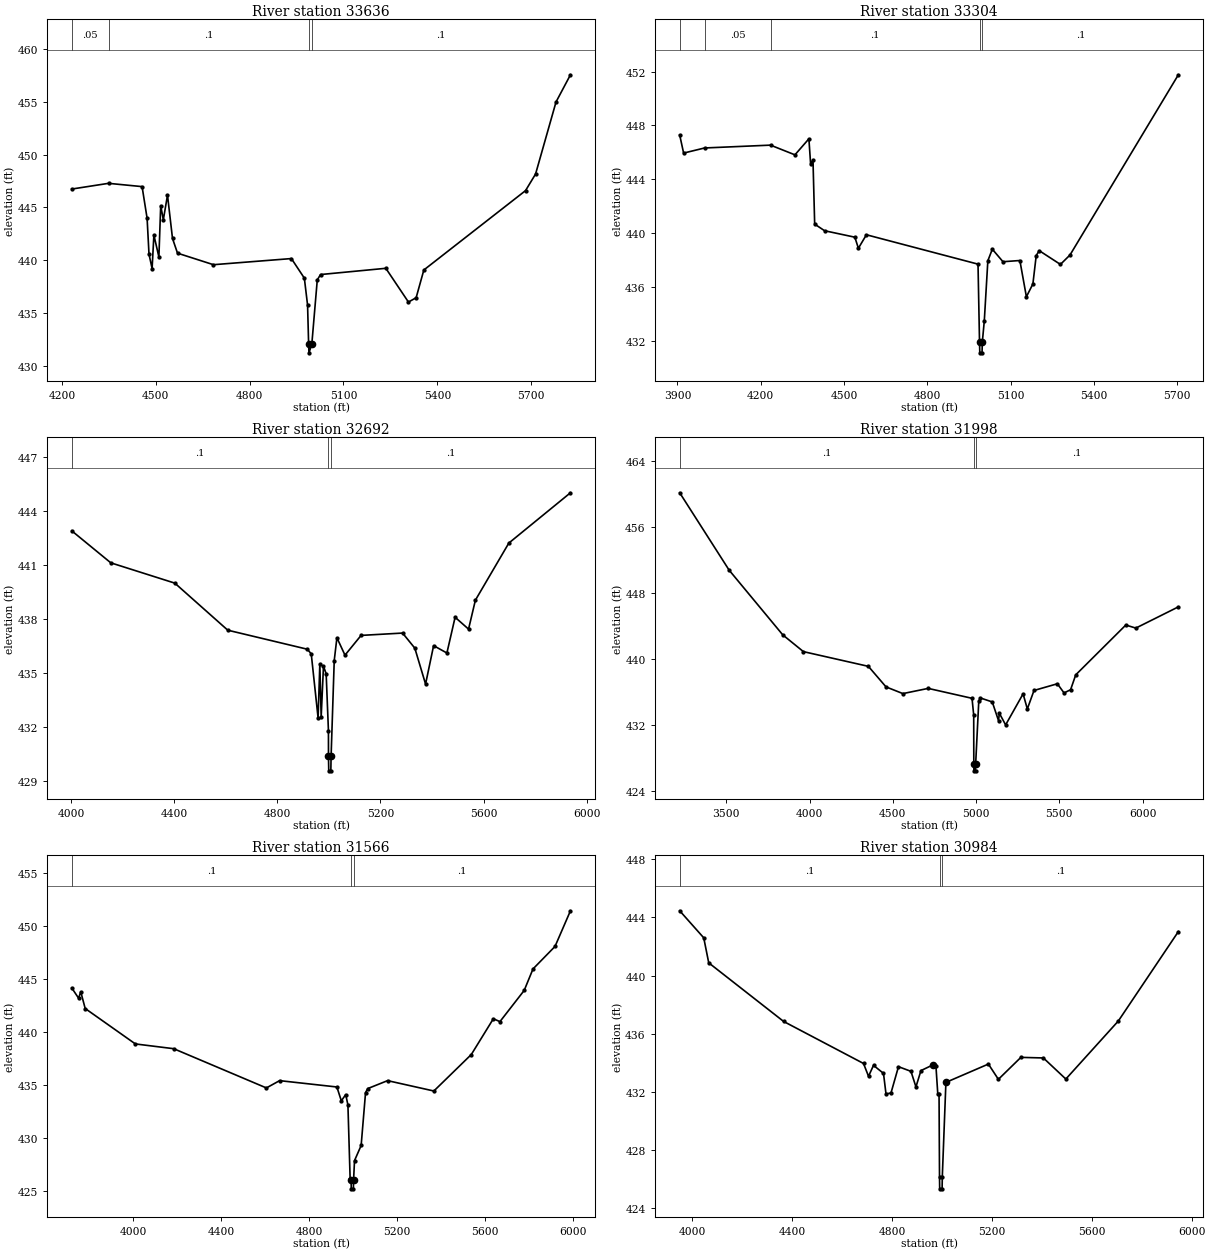
Type RM Length L Ch R = 1 ,33636   ,332,332,332
BEGIN DESCRIPTION:
Liveoak Creek 43.0
END DESCRIPTION:
XS GIS Cut Line= 4
      2034740.63     13463286.92      2034243.25     13463010.02
       2033774.5     13462886.32        2033271.     13462691.87
#Sta/Elev= 30
  4231.7  446.74  4349.1  447.28  4456.4  446.97  4472.4  443.98  4478.5  440.58
  4488.4  439.23  4494.1  442.39  4510.1  440.32  4515.9  445.17  4524.3  443.84
  4537.6  446.16  4553.6  442.07  4569.6  440.68  4684.5  439.59  4933.6  440.17
    4975  438.32  4985.3  435.77  4988.7  432.06  4989.7  431.26  4998.8  432.06
  5016.3  438.15  5026.7  438.66  5235.4  439.25  5307.7  436.06  5332.3  436.47
  5356.9  439.09  5681.9  446.59    5714  448.16  5779.4  454.97  5825.5  457.54
#Mann= 4 ,-1 , 0
  4231.7     .05       0  4349.1      .1       0  4988.7     .07       0
  4998.8      .1       0
Bank Sta=4988.7,4998.8
XS Rating Curve= 0 ,0
Exp/Cntr=0.3,0.1

Type RM Length L Ch R = 1 ,33304   ,612,612,612
BEGIN DESCRIPTION:
Liveoak Creek 42.0
END DESCRIPTION:
XS GIS Cut Line= 3
      2034906.45     13463313.41        2034025.       13462675.
       2033375.2     13462393.27
#Sta/Elev= 30
  3908.1  447.29  3922.2  445.95  3997.9  446.33  4235.3  446.54  4323.3  445.82
  4373.6  447.01  4379.7  445.16  4388.3  445.43  4394.4  440.68    4430  440.19
  4539.1  439.71  4551.9  438.89  4580.8  439.89  4982.9  437.71  4988.3  431.93
  4989.3  431.13  4997.4  431.13  4998.4  431.93  5005.5  433.49  5018.3  437.96
  5034.4  438.82  5072.8  437.89  5133.7  437.98  5157.2  435.29  5180.6  436.24
  5192.6  438.35  5203.5  438.71  5279.8  437.69  5314.3  438.39  5704.7  451.76
#Mann= 5 ,-1 , 0
  3908.1      .1       0  3997.9     .05       0  4235.3      .1       0
  4988.3     .07       0  4998.4      .1       0
Bank Sta=4988.3,4998.4
XS Rating Curve= 0 ,0
Exp/Cntr=0.3,0.1

Type RM Length L Ch R = 1 ,32692   ,694,694,694
BEGIN DESCRIPTION:
Liveoak Creek 41.0
END DESCRIPTION:
XS GIS Cut Line= 3
      2035000.21     13462962.73      2034504.17       13462375.
      2033385.62     13462046.05
#Sta/Elev= 30
  4002.3   442.9  4153.7  441.12  4402.1  439.99  4607.6  437.37  4916.4  436.31
  4931.5  436.05  4958.1  432.48  4964.8  435.49    4970  432.54    4979  435.37
  4989.4  434.94  4998.2  431.77  4998.4  430.34  4999.4  429.54  5007.5  429.54
  5008.5  430.34  5020.7  435.68  5031.1  436.95  5062.4  435.98  5124.9  437.08
  5285.9  437.21  5333.4  436.37  5375.1  434.37  5406.3  436.51  5457.9   436.1
  5489.7  438.09  5541.9  437.43  5568.4  439.04  5698.2  442.22  5937.3  445.02
#Mann= 3 ,-1 , 0
  4002.3      .1       0  4998.4     .07       0  5008.5      .1       0
Bank Sta=4998.4,5008.5
XS Rating Curve= 0 ,0
Exp/Cntr=0.3,0.1

Type RM Length L Ch R = 1 ,31998   ,432,432,432
BEGIN DESCRIPTION:
Liveoak Creek 40.0
END DESCRIPTION:
XS GIS Cut Line= 3
      2036218.91     13461632.85      2034354.36     13461927.99
      2033250.16     13462004.38
#Sta/Elev= 30
    3220   460.1    3517  450.73  3838.9   442.9    3963  440.87    4353  439.09
  4459.1   436.6  4560.4  435.79  4712.3  436.42  4975.5  435.22  4985.6  433.18
  4986.2  427.24  4986.9  426.44  4996.4  426.44  4997.2  427.24    5016  434.85
  5026.1  435.26    5097  434.78  5134.6  432.52  5139.6  433.41  5177.3     432
  5282.2  435.76  5307.6  433.93  5347.7  436.17    5488  436.98  5528.1  435.87
  5567.4  436.26  5598.3  438.06    5899  444.09  5959.2  443.72  6214.6  446.29
#Mann= 3 ,-1 , 0
    3220      .1       0  4986.2     .07       0  4997.2      .1       0
Bank Sta=4986.2,4997.2
XS Rating Curve= 0 ,0
Exp/Cntr=0.3,0.1

Type RM Length L Ch R = 1 ,31566   ,582,582,582
BEGIN DESCRIPTION:
Liveoak Creek 39.0
END DESCRIPTION:
XS GIS Cut Line= 3
       2035635.6     13461639.79      2035003.66     13461705.76
      2033375.03       13461625.
#Sta/Elev= 30
  3721.6  444.17  3752.4  443.21  3762.4  443.81  3782.5  442.23  4010.6  438.88
  4184.7  438.43  4605.9  434.72    4666  435.41  4926.3  434.81  4946.4   433.5
  4966.4  434.09  4976.4  433.11  4986.4  426.14  4990.9  425.98  4991.6  425.18
  5001.3  425.18    5002  425.98  5006.4  427.85  5036.5  429.28  5056.5  434.28
  5066.5  434.66  5156.6  435.41  5366.9  434.43  5537.1  437.88  5637.2  441.26
  5667.2  440.99  5777.4  443.94  5817.4  445.97  5917.5   448.1  5987.6  451.47
#Mann= 3 ,-1 , 0
  3721.6      .1       0  4990.9     .07       0    5002      .1       0
Bank Sta=4990.9,5002
XS Rating Curve= 0 ,0
Exp/Cntr=0.3,0.1

Type RM Length L Ch R = 1 ,30984   ,672,672,672
BEGIN DESCRIPTION:
Liveoak Creek 38.0
END DESCRIPTION:
XS GIS Cut Line= 3
      2035611.28     13461372.43        2034575.       13461375.
      2033614.75     13461334.24
#Sta/Elev= 30
  3949.5  444.46  4045.8   442.6  4065.8  440.88  4365.8  436.85  4685.8  433.96
  4705.8  433.08  4725.8  433.83  4765.8  433.28  4775.8  431.87  4795.8  431.93
  4825.8  433.74  4875.8  433.42  4895.8  432.35  4915.8  433.47  4965.8  433.88
  4975.8   433.8  4983.3  431.86  4988.3  431.86  4990.2  426.14  4990.9  425.34
  5000.6  425.34  5001.3  426.14  5015.8  432.66    5186  433.92    5226  432.87
  5316.1  434.38  5406.2  434.34  5496.2  432.89  5706.4  436.88  5946.9  443.03
#Mann= 3 ,-1 , 0
  3949.5      .1       0  4990.2     .07       0  5001.3      .1       0
Bank Sta=4965.8,5015.8
XS Rating Curve= 0 ,0
Exp/Cntr=0.3,0.1

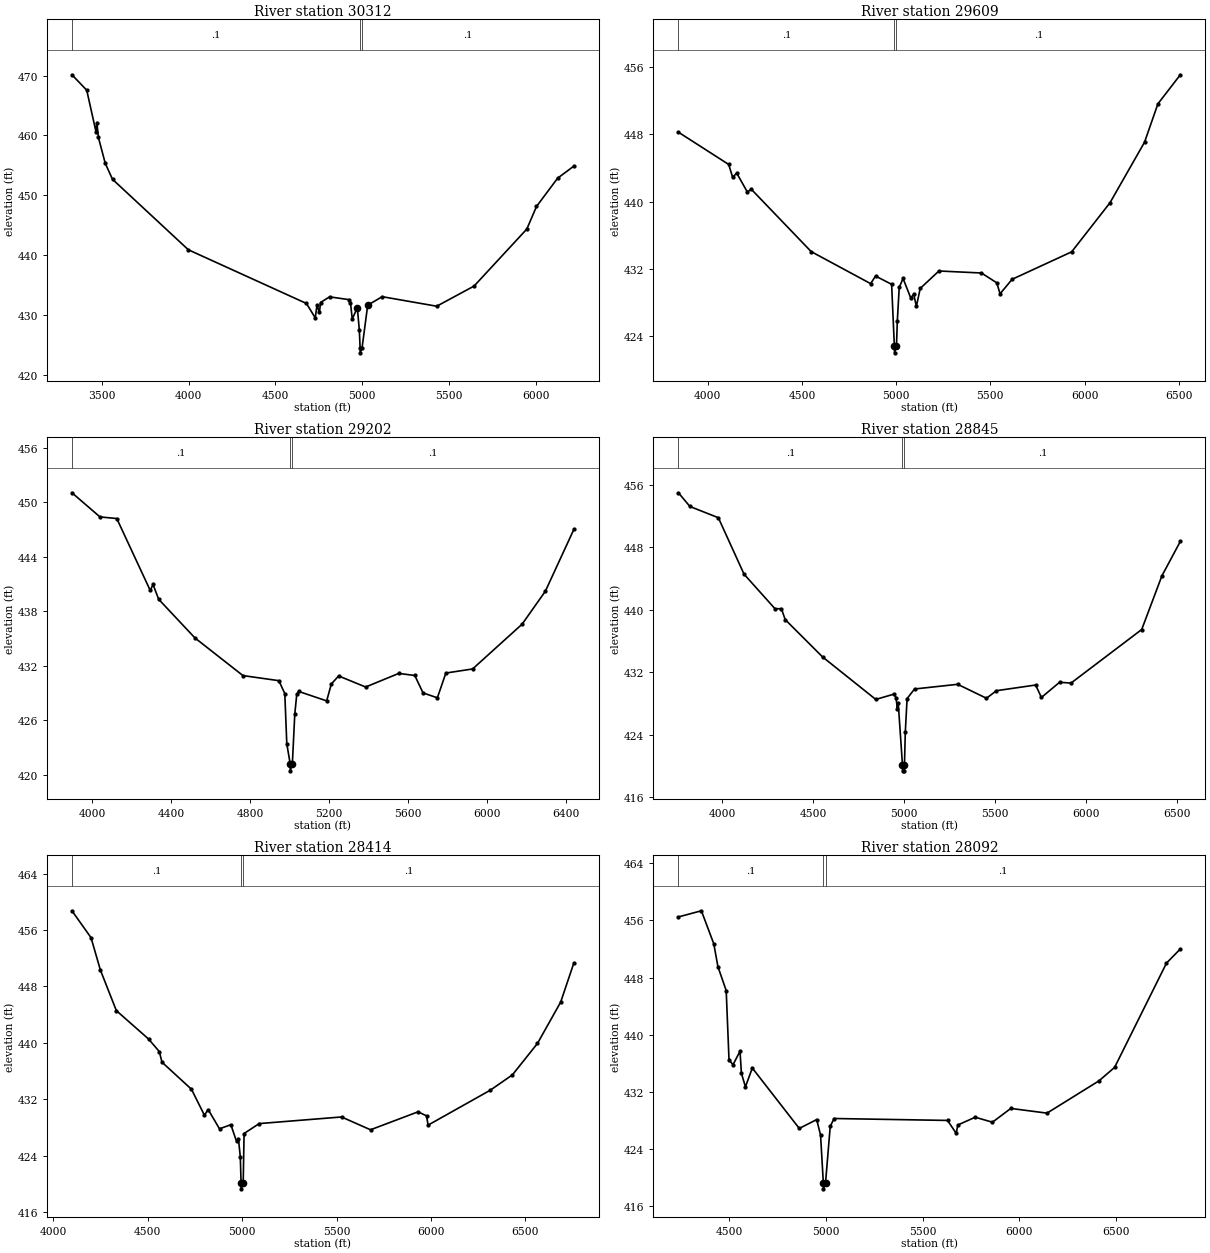
Type RM Length L Ch R = 1 ,30312   ,703,703,703
BEGIN DESCRIPTION:
Liveoak Creek 37.0
END DESCRIPTION:
XS GIS Cut Line= 3
      2036125.04     13461325.01        2034475.       13461025.
      2033275.04     13460825.01
#Sta/Elev= 30
  3327.5  470.13  3412.7  467.56    3466  460.63  3471.1  462.16    3480  459.68
  3519.4  455.36  3561.3  452.69  3998.4  440.93  4679.3  431.97  4730.2  429.57
  4740.3  431.65  4754.3  430.47  4760.7  432.13  4812.7  433.07  4924.5  432.61
  4933.4  432.06  4943.6  429.38  4972.8  431.26  4984.3  427.52  4988.9  424.53
  4989.6  423.73    5000  424.53  5032.5  431.68  5116.1   433.1  5430.4  431.51
  5645.8  434.87    5950  444.39  6005.7  448.15  6127.4  452.87  6221.1  454.89
#Mann= 3 ,-1 , 0
  3327.5      .1       0  4988.9     .07       0    5000      .1       0
Bank Sta=4972.8,5032.5
XS Rating Curve= 0 ,0
Exp/Cntr=0.3,0.1

Type RM Length L Ch R = 1 ,29609   ,407,407,407
BEGIN DESCRIPTION:
Mapping XS 8e0bc118
END DESCRIPTION:
XS GIS Cut Line= 4
      2035703.67     13461143.14      2035266.14     13460669.15
      2034531.77     13460559.77      2033278.23     13460799.03
#Sta/Elev= 30
  3844.6  448.26  4111.4  444.42  4132.4  442.89  4153.9  443.39  4210.1  441.15
  4231.6  441.46  4549.1  434.04  4864.9  430.22  4890.7  431.13  4976.1  430.14
  4990.7  422.78  4991.5  421.98  5001.9  422.78  5006.4   425.8  5016.5  429.77
  5036.8  430.84  5077.2  428.54  5093.6  428.95  5107.5   427.5  5127.8  429.65
  5227.2  431.73  5452.8  431.49  5534.3  430.32  5551.5  429.01  5615.7  430.74
  5931.6  434.01  6134.9  439.85  6318.2  447.06  6389.4  451.64  6508.3   455.1
#Mann= 3 ,-1 , 0
  3844.6      .1       0  4990.7     .07       0  5001.9      .1       0
Bank Sta=4990.7,5001.9
XS Rating Curve= 0 ,0
Exp/Cntr=0.3,0.1

Type RM Length L Ch R = 1 ,29202   ,357,357,357
BEGIN DESCRIPTION:
Mapping XS d5af297b
END DESCRIPTION:
XS GIS Cut Line= 4
      2035755.74     13460934.78      2035146.35      13460393.1
      2034583.85     13460309.77      2033474.46     13460653.53
#Sta/Elev= 30
    3896  451.07  4038.1  448.41  4123.4  448.23  4293.1   440.3  4307.3  440.96
  4335.8  439.33  4519.7  435.07  4763.2  430.92  4945.2  430.36  4975.5  428.94
  4985.6   423.4  5002.6  421.22  5003.3  420.42  5013.8  421.22  5026.1  426.67
  5036.2  428.87  5046.3  429.17  5187.8  428.13  5211.6     430  5248.5  430.88
  5385.4  429.66  5553.6  431.16  5634.7  430.93  5676.6  429.01  5749.2  428.47
  5792.3   431.2  5927.9  431.65  6179.1  436.59  6296.9  440.22  6441.4  447.03
#Mann= 3 ,-1 , 0
    3896      .1       0  5002.6     .07       0  5013.8      .1       0
Bank Sta=5002.6,5013.8
XS Rating Curve= 0 ,0
Exp/Cntr=0.3,0.1

Type RM Length L Ch R = 1 ,28845   ,431,431,431
BEGIN DESCRIPTION:
Mapping XS 5aea75d1
END DESCRIPTION:
XS GIS Cut Line= 4
      2035828.61      13460851.4      2035208.85     13460158.73
      2034714.06     13460070.19       2033453.6     13460492.08
#Sta/Elev= 30
  3758.4  455.01  3821.8  453.25  3978.1  451.81  4119.4  444.57  4289.9  440.13
    4325  440.14  4345.9  438.74  4551.6  433.95  4844.2   428.5  4945.7  429.19
  4955.9  428.69  4962.7  427.32  4967.8  428.04  4990.9  420.14  4991.6  419.34
  5001.4  419.34  5002.1  420.14  5006.7  424.33  5016.5  428.61  5057.5  429.84
    5295  430.44  5453.1  428.65  5508.1  429.62  5723.8  430.35  5755.4  428.75
  5855.3   430.7  5918.5   430.6  6307.3  437.47  6418.3  444.35  6519.7  448.77
#Mann= 3 ,-1 , 0
  3758.4      .1       0  4990.9     .07       0  5002.1      .1       0
Bank Sta=4990.9,5002.1
XS Rating Curve= 0 ,0
Exp/Cntr=0.3,0.1

Type RM Length L Ch R = 1 ,28414   ,322,322,322
BEGIN DESCRIPTION:
Mapping XS d4638741
END DESCRIPTION:
XS GIS Cut Line= 4
      2035844.24     13460257.67      2035349.47     13459841.02
      2034859.89     13459820.19      2033428.76     13460335.39
#Sta/Elev= 30
  4098.6  458.73  4199.7  454.91  4249.1  450.33  4333.7  444.56    4504  440.54
  4561.2  438.75  4575.5  437.24  4731.6   433.4    4800  429.72    4820  430.52
    4880  427.79  4940.1  428.37  4970.1  426.01  4980.1   426.4  4990.1  423.84
  4994.3  420.07    4995  419.27  5005.5  420.07  5010.1  427.12  5090.2  428.53
  5526.2  429.47  5679.7  427.65  5931.5   430.2  5976.2  429.63  5984.6  428.31
  6314.1  433.27    6431  435.44  6563.7   439.9  6686.5  445.76  6756.5  451.32
#Mann= 3 ,-1 , 0
  4098.6      .1       0  4994.3     .07       0  5005.5      .1       0
Bank Sta=4994.3,5005.5
XS Rating Curve= 0 ,0
Exp/Cntr=0.3,0.1

Type RM Length L Ch R = 1 ,28092   ,370,370,370
BEGIN DESCRIPTION:
Mapping XS 714f9a96
END DESCRIPTION:
XS GIS Cut Line= 4
      2035755.74     13459851.45      2035370.31     13459549.35
      2034625.52     13459554.56       2033408.4     13460163.12
#Sta/Elev= 30
  4237.5  456.48  4356.2  457.34  4420.4  452.72  4441.7  449.53  4484.6  446.17
  4499.1  436.49  4519.9   435.8  4556.1   437.7  4563.2  434.61  4584.1  432.71
  4619.6  435.34  4862.5  426.89  4952.5  428.13  4972.5  425.96  4986.9  419.24
  4987.6  418.44  4998.1  419.24  5022.5  427.18  5042.5  428.28  5629.1  428.01
  5673.8  426.21  5682.4  427.37  5771.9  428.46  5861.3  427.76  5956.3  429.69
  6143.4  429.03  6411.7  433.54    6493  435.43  6761.3  450.02  6832.8     452
#Mann= 3 ,-1 , 0
  4237.5      .1       0  4986.9     .07       0  4998.1      .1       0
Bank Sta=4986.9,4998.1
XS Rating Curve= 0 ,0
Exp/Cntr=0.3,0.1

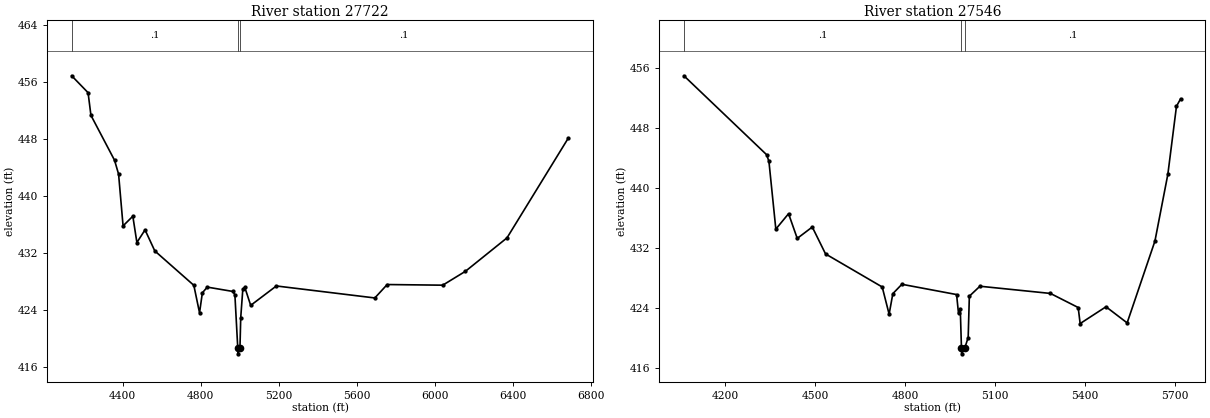
Type RM Length L Ch R = 1 ,27722   ,176,176,176
BEGIN DESCRIPTION:
Mapping XS b82493c0
END DESCRIPTION:
XS GIS Cut Line= 4
      2035766.11      13459721.2      2035229.68     13459320.19
      2034818.22     13459257.69      2033434.64     13459720.62
#Sta/Elev= 30
  4139.2  456.83  4223.2  454.46  4237.8  451.29  4358.7     445  4379.5  443.05
  4402.5   435.8  4452.5  437.15  4473.3  433.47  4515.1  435.24  4565.1  432.29
  4765.1  427.47  4794.3  423.62  4808.8  426.42  4833.9  427.22  4965.4  426.61
  4975.5  426.13  4990.2  418.67  4990.9  417.87  5001.4  418.67  5005.4  422.95
    5016   426.9  5026.1   427.2  5056.4  424.66  5187.9  427.38  5692.5   425.7
  5755.8  427.58  6040.5  427.49  6156.5  429.43  6369.8  434.12  6684.1  448.11
#Mann= 3 ,-1 , 0
  4139.2      .1       0  4990.2     .07       0  5001.4      .1       0
Bank Sta=4990.2,5001.4
XS Rating Curve= 0 ,0
Exp/Cntr=0.3,0.1

Type RM Length L Ch R = 1 ,27546   ,868,868,868
BEGIN DESCRIPTION:
Liveoak Creek 32.0
END DESCRIPTION:
XS GIS Cut Line= 3
      2035825.03     13459625.02        2035025.       13459125.
      2034474.98     13458674.98
#Sta/Elev= 30
  4063.4  455.01  4338.8  444.48  4346.5  443.59  4369.5  434.55  4411.9  436.61
  4440.8  433.31  4490.9  434.83  4535.1  431.24  4723.8  426.83  4746.8   423.2
  4759.2  425.94  4789.3  427.19  4971.5  425.82  4977.9   423.3  4983.8  423.87
  4987.7  418.71  4988.4  417.91  4998.9  418.71  5010.1  420.09    5014   425.6
  5049.2  426.93  5283.9  425.97  5376.5  424.09    5383  421.95  5469.1  424.19
  5539.5  422.04  5632.1  432.96  5675.1  441.87  5703.8  450.94  5717.5  451.93
#Mann= 3 ,-1 , 0
  4063.4      .1       0  4987.7     .07       0  4998.9      .1       0
Bank Sta=4987.7,4998.9
XS Rating Curve= 0 ,0
Exp/Cntr=0.3,0.1