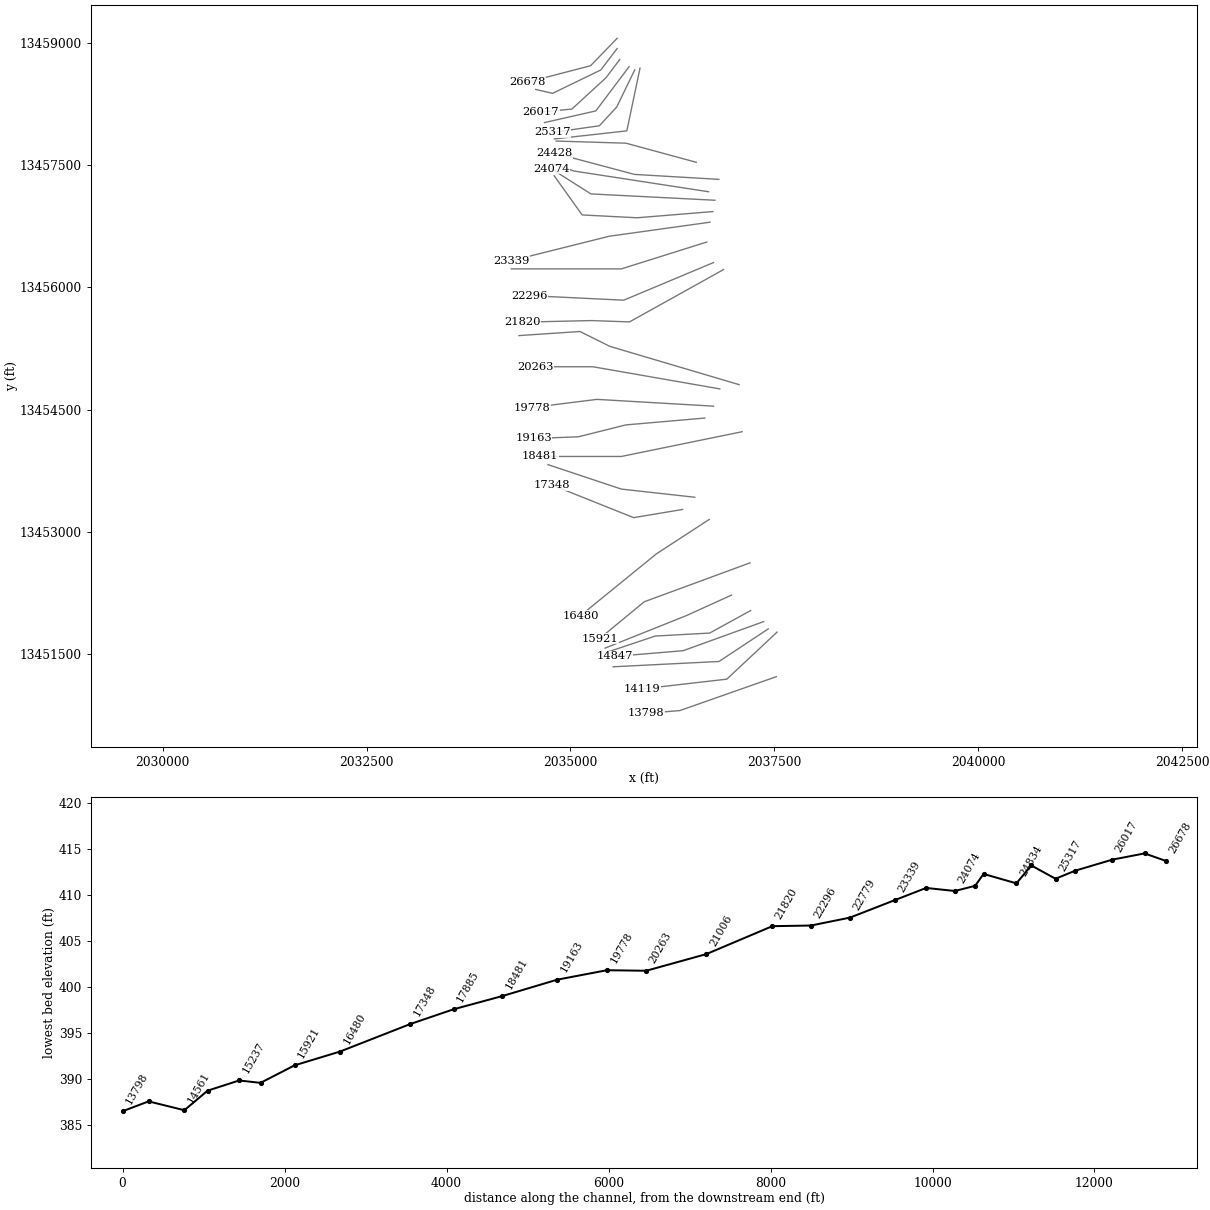
HEC-RAS study Liveoak Creek.prj: Liveoak Creek Base Level Engineering

--- Liveoak Creek.g01 (geometry) --- (continued)

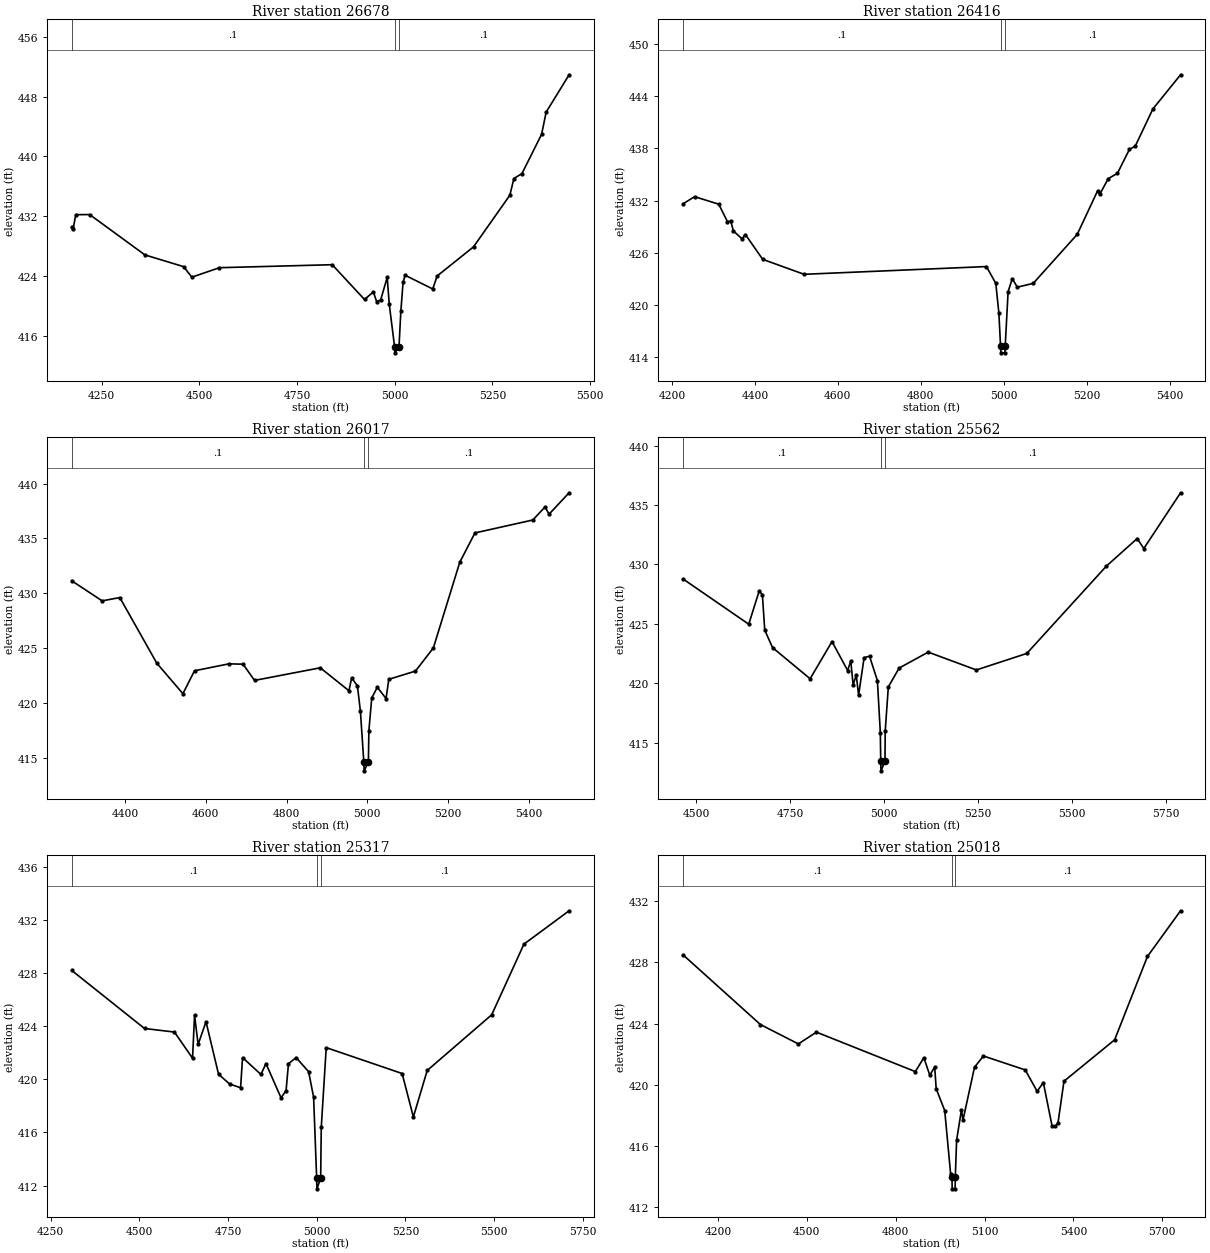
Type RM Length L Ch R = 1 ,26678   ,262,262,262
BEGIN DESCRIPTION:
Mapping XS c50b5f58
END DESCRIPTION:
XS GIS Cut Line= 3
      2035573.09     13459051.75      2035247.59     13458715.83
      2034468.15     13458513.18
#Sta/Elev= 30
    4173  430.57  4176.4  430.25  4183.4   432.2  4218.9  432.22  4360.4  426.81
  4459.4  425.24  4480.5  423.83  4551.2   425.1  4839.7   425.5  4922.4  420.84
  4945.2  421.86  4953.4  420.55  4963.7  420.77  4980.5   423.8  4985.7  420.23
  4999.4  414.49  5000.1  413.69  5010.7  414.49  5015.4  419.25  5021.1  423.12
  5026.2  424.09    5097  422.25  5108.4  423.99  5201.4  427.89  5294.4  434.81
  5304.8  437.05  5325.4  437.71  5375.6  442.96  5387.4  445.95  5446.1  450.95
#Mann= 3 ,-1 , 0
    4173      .1       0  4999.4     .07       0  5010.7      .1       0
Bank Sta=4999.4,5010.7
XS Rating Curve= 0 ,0
Exp/Cntr=0.3,0.1

Type RM Length L Ch R = 1 ,26416   ,399,399,399
BEGIN DESCRIPTION:
Liveoak Creek 31.0
END DESCRIPTION:
XS GIS Cut Line= 4
       2035573.1     13458926.76      2035372.59     13458663.75
      2034781.44     13458377.29      2034575.01       13458425.
#Sta/Elev= 30
  4226.9  431.64  4254.5  432.46  4312.7  431.59  4333.5   429.6  4341.7  429.64
    4348  428.52  4368.8  427.61  4377.1   428.1  4418.7  425.25  4518.5  423.53
  4958.3  424.42  4980.9  422.48  4988.3  419.05  4992.3   415.3    4993   414.5
  5002.9   414.5  5003.6   415.3  5010.5  421.52  5020.5  423.03  5032.8  422.05
  5071.2  422.49  5177.2  428.12  5226.4  433.13  5231.5  432.72  5251.9  434.52
  5274.3  435.15  5303.2   437.9    5317  438.25  5359.7  442.54  5426.4  446.47
#Mann= 3 ,-1 , 0
  4226.9      .1       0  4992.3     .07       0  5003.6      .1       0
Bank Sta=4992.3,5003.6
XS Rating Curve= 0 ,0
Exp/Cntr=0.3,0.1

Type RM Length L Ch R = 1 ,26017   ,455,455,455
BEGIN DESCRIPTION:
Mapping XS cccab8cb
END DESCRIPTION:
XS GIS Cut Line= 4
      2035604.36     13458791.36      2035437.69       13458570.
      2035018.42     13458184.58      2034635.64     13458148.13
#Sta/Elev= 30
  4268.3  431.14  4343.6  429.31  4387.3  429.61  4478.9  423.63  4543.5  420.85
  4572.2  422.94  4657.3  423.57  4692.4  423.54  4720.8  422.06  4883.5  423.21
  4954.4  421.12  4961.2  422.29  4975.4  421.57  4982.8  419.27  4991.3  414.62
    4992  413.82  5002.6  414.62  5003.8  417.48  5010.9  420.46  5024.7  421.44
  5046.3  420.41  5053.1  422.16  5119.1  422.91  5163.4  425.02  5228.8  432.83
  5266.3   435.5  5409.6  436.68  5439.8  437.87  5449.8  437.21  5499.4  439.16
#Mann= 3 ,-1 , 0
  4268.3      .1       0  4991.3     .07       0  5002.6      .1       0
Bank Sta=4991.3,5002.6
XS Rating Curve= 0 ,0
Exp/Cntr=0.3,0.1

Type RM Length L Ch R = 1 ,25562   ,245,245,245
BEGIN DESCRIPTION:
Mapping XS 2d10b573
END DESCRIPTION:
XS GIS Cut Line= 3
       2035719.8     13458704.53      2035311.82     13458162.01
      2034682.52     13458018.79
#Sta/Elev= 30
  4465.1  428.77  4639.7  424.97  4667.7  427.78    4676  427.45  4682.3  424.47
  4703.1     423  4803.1  420.38  4861.4  423.51    4903  421.07  4911.3  421.88
  4917.6  419.86  4925.9  420.69  4932.2     419  4946.8  422.15  4961.3  422.28
  4982.2  420.22    4990  415.85  4991.1  413.43  4991.8  412.63  5002.4  413.43
    5003  415.96  5011.3  419.69  5040.1  421.28  5117.5  422.62  5245.7  421.12
    5380  422.51  5591.9  429.86  5673.9  432.18  5691.5  431.34  5789.3  436.03
#Mann= 3 ,-1 , 0
  4465.1      .1       0  4991.1     .07       0  5002.4      .1       0
Bank Sta=4991.1,5002.4
XS Rating Curve= 0 ,0
Exp/Cntr=0.3,0.1

Type RM Length L Ch R = 1 ,25317   ,299,299,299
BEGIN DESCRIPTION:
Mapping XS 2e8b3d26
END DESCRIPTION:
XS GIS Cut Line= 4
      2035789.25     13458665.49       2035567.9     13458209.76
      2035355.23     13457979.72        2034779.     13457897.41
#Sta/Elev= 30
  4309.2  428.19  4514.4  423.82  4598.8  423.55  4649.8  421.58  4655.4  424.82
  4665.5  422.62  4687.7  424.33  4723.1  420.37  4754.4  419.64  4785.2  419.36
  4790.7  421.63  4842.5  420.36  4856.7  421.18  4899.2   418.6  4913.4  419.15
  4920.2  421.17  4941.7  421.63  4976.9  420.57    4991  418.65  4999.6  412.55
  5000.3  411.75  5010.9  412.55  5012.6  416.38  5026.6  422.38  5240.5  420.43
  5272.2  417.16  5311.2  420.66    5493  424.85  5583.9  430.17  5711.2  432.68
#Mann= 3 ,-1 , 0
  4309.2      .1       0  4999.6     .07       0  5010.9      .1       0
Bank Sta=4999.6,5010.9
XS Rating Curve= 0 ,0
Exp/Cntr=0.3,0.1

Type RM Length L Ch R = 1 ,25018   ,184,184,184
BEGIN DESCRIPTION:
Liveoak Creek 30.0
END DESCRIPTION:
XS GIS Cut Line= 3
       2035853.5     13458685.49      2035692.03     13457917.22
      2034803.98     13457818.26
#Sta/Elev= 30
  4082.9  428.49  4343.5  423.94  4471.7  422.67  4532.7  423.44  4866.5  420.86
  4895.2  421.77  4915.3  420.62  4931.8  421.16  4936.8  419.74  4965.6  418.31
  4985.7  414.14  4990.1  413.99  4990.8  413.19  5000.7  413.19  5001.4  413.99
  5005.8  416.38  5022.2  418.36  5027.2  417.68  5066.2  421.15  5096.4  421.88
  5237.3  420.97  5277.5  419.57  5298.5  420.14  5327.8  417.31  5337.9  417.27
  5347.9   417.5  5368.1  420.23  5539.1  422.94  5649.8  428.39  5761.5  431.38
#Mann= 3 ,-1 , 0
  4082.9      .1       0  4990.1     .07       0  5001.4      .1       0
Bank Sta=4990.1,5001.4
XS Rating Curve= 0 ,0
Exp/Cntr=0.3,0.1

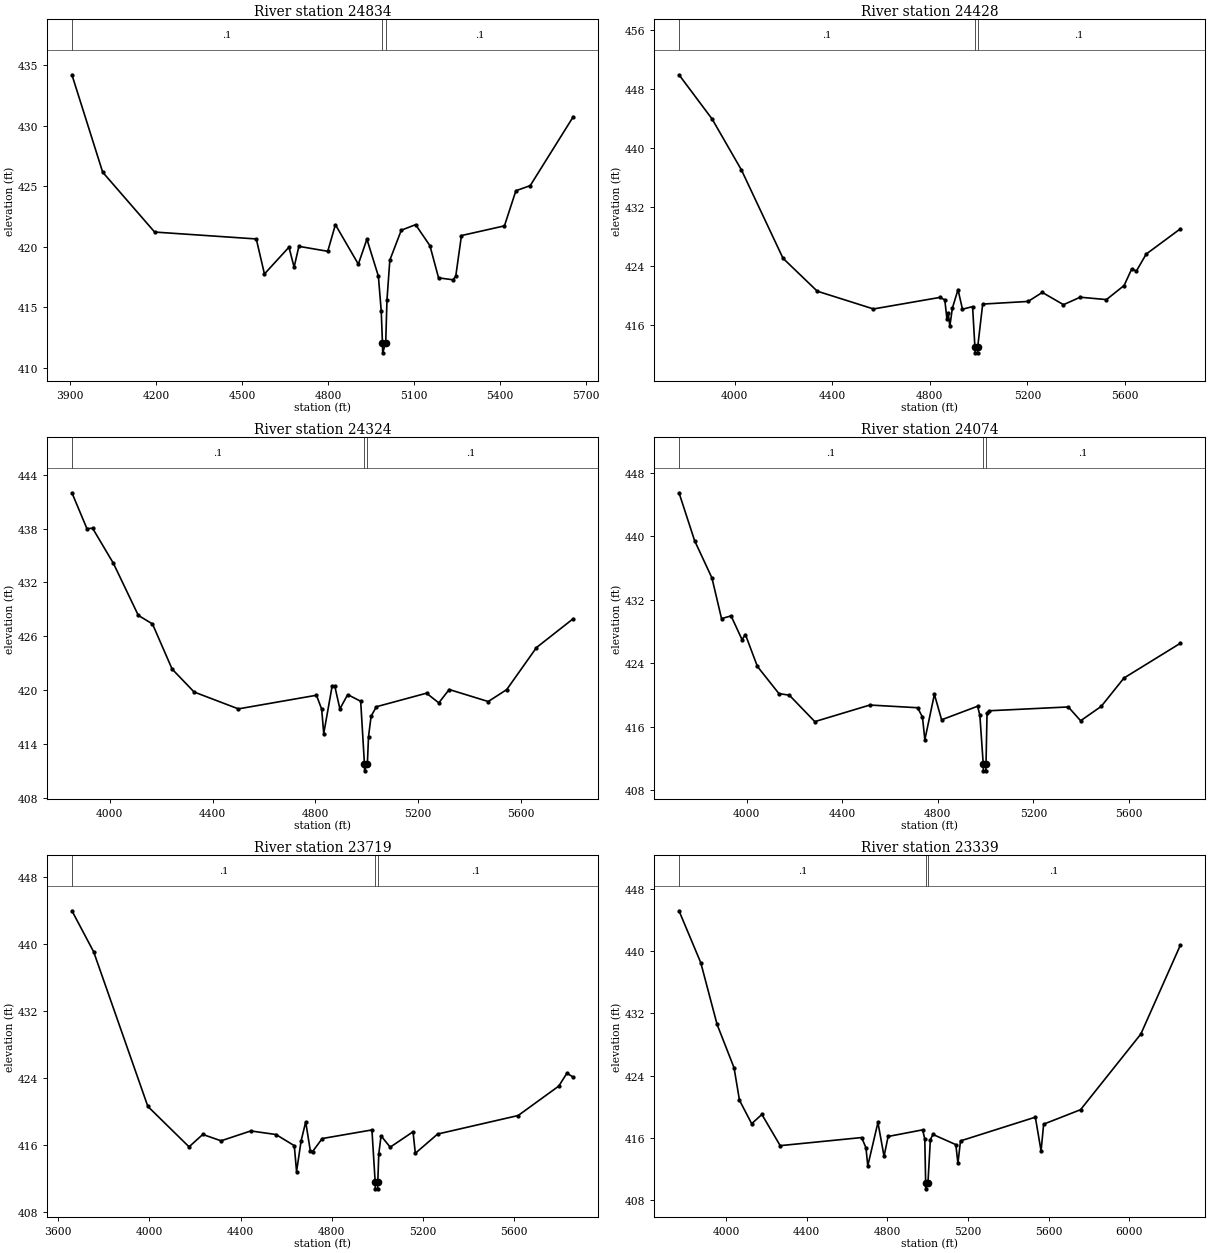
Type RM Length L Ch R = 1 ,24834   ,406,406,406
BEGIN DESCRIPTION:
Liveoak Creek 29.0
END DESCRIPTION:
XS GIS Cut Line= 3
      2036543.61      13457531.8      2035681.61     13457766.18
       2034824.8     13457792.22
#Sta/Elev= 30
  3905.8   434.2  4013.2  426.16  4194.5  421.22  4549.5  420.65    4578  417.76
  4663.6  419.97  4681.6  418.32  4698.2  420.04  4799.1  419.63  4825.7  421.83
  4905.8  418.57  4935.8  420.63  4975.8  417.58  4985.8   414.7  4990.1  412.05
  4990.8  411.25  5001.4  412.05  5005.8   415.6  5015.8   418.9  5055.8  421.37
  5105.8  421.83  5155.9  420.09  5185.9  417.44  5235.9  417.28  5245.9  417.56
  5265.9  420.93    5416  421.73    5456  424.63    5506  425.05  5656.3  430.74
#Mann= 3 ,-1 , 0
  3905.8      .1       0  4990.1     .07       0  5001.4      .1       0
Bank Sta=4990.1,5001.4
XS Rating Curve= 0 ,0
Exp/Cntr=0.3,0.1

Type RM Length L Ch R = 1 ,24428   ,104,104,104
BEGIN DESCRIPTION:
Mapping XS 54e21cab
END DESCRIPTION:
XS GIS Cut Line= 3
      2036820.47     13457322.61       2035785.2     13457383.37
       2034802.4     13457645.46
#Sta/Elev= 30
  3772.1  449.97  3907.8  443.97    4028  437.06  4198.3  425.09  4338.5  420.63
  4568.9  418.22  4840.4  419.78  4861.1  419.47    4870  416.83  4875.2  417.63
  4881.8  415.87  4892.2  418.33  4915.3  420.84  4933.6  418.18    4975  418.54
  4984.5  413.07  4985.2  412.27  4995.4  412.27    4996  413.07  5016.4  418.88
  5202.6  419.24  5260.7  420.46  5347.5   418.8  5415.9  419.81  5523.5  419.49
  5595.9   421.4    5627  423.64  5646.2  423.36  5686.3  425.66  5826.3  429.08
#Mann= 3 ,-1 , 0
  3772.1      .1       0  4984.5     .07       0    4996      .1       0
Bank Sta=4984.5,4996
XS Rating Curve= 0 ,0
Exp/Cntr=0.3,0.1

Type RM Length L Ch R = 1 ,24324   ,250,250,250
BEGIN DESCRIPTION:
Mapping XS a8039826
END DESCRIPTION:
XS GIS Cut Line= 3
      2036694.59      13457170.7      2035047.64      13457424.1
      2034779.26     13457512.84
#Sta/Elev= 30
  3853.4  441.99  3911.6     438  3933.9  438.03  4014.9  434.11  4111.4  428.32
  4166.6  427.36  4242.9  422.33  4328.5  419.77  4500.5  417.89    4804  419.41
  4824.3  417.86  4832.3  415.14  4864.8   420.4  4874.9  420.47  4895.1  417.89
  4925.5  419.48    4976  418.74  4990.5  411.78  4991.2  410.98    5002  411.78
  5006.4  414.79  5016.5  417.08  5037.1  418.13  5231.9  419.64  5279.6  418.56
    5320  420.05  5471.8  418.71  5543.7  420.04  5659.4  424.73  5802.4  427.95
#Mann= 3 ,-1 , 0
  3853.4      .1       0  4990.5     .07       0    5002      .1       0
Bank Sta=4990.5,5002
XS Rating Curve= 0 ,0
Exp/Cntr=0.3,0.1

Type RM Length L Ch R = 1 ,24074   ,355,355,355
BEGIN DESCRIPTION:
Mapping XS 28211dc8
END DESCRIPTION:
XS GIS Cut Line= 3
      2036772.73     13457066.53      2035251.64     13457144.15
      2034765.55     13457452.29
#Sta/Elev= 30
  3716.4  445.45  3781.8  439.41  3854.3  434.72  3894.4   429.6  3934.4  429.94
  3980.1  426.96  3994.5  427.58  4044.6  423.57  4134.7  420.15  4178.3  419.95
  4284.9  416.62  4515.2  418.71  4715.4  418.37  4735.5  417.19  4745.5  414.34
  4785.5  420.06  4815.6  416.85  4966.3  418.56  4975.8  417.41    4990  411.22
  4990.7  410.42  5000.9  410.42  5001.5  411.22  5005.8  417.68  5015.8  417.99
  5345.9  418.47  5397.6  416.73  5484.1  418.55  5578.9  422.11    5815  426.49
#Mann= 3 ,-1 , 0
  3716.4      .1       0    4990     .07       0  5001.5      .1       0
Bank Sta=4990,5001.5
XS Rating Curve= 0 ,0
Exp/Cntr=0.3,0.1

Type RM Length L Ch R = 1 ,23719   ,380,380,380
BEGIN DESCRIPTION:
Liveoak Creek 28.0
END DESCRIPTION:
XS GIS Cut Line= 4
      2036746.75     13456927.64      2035818.04     13456851.61
      2035144.43     13456886.34      2034800.22     13457367.71
#Sta/Elev= 30
  3660.4  443.98  3755.8  439.07  3993.3   420.6  4173.9  415.77  4234.1  417.25
  4314.3  416.49  4444.8  417.67  4555.1  417.24  4635.3  415.91  4645.3  412.82
  4665.4   416.5  4685.4  418.75  4705.4  415.33  4715.4   415.2  4757.8  416.76
  4975.8  417.79    4990  411.55  4990.7  410.75  5000.9  410.75  5001.5  411.55
  5005.8  414.93  5015.8  417.08  5055.9  415.73    5156  417.57    5166     415
  5263.9   417.3  5616.8  419.51    5795  423.03  5830.6  424.57  5858.5   424.1
#Mann= 3 ,-1 , 0
  3660.4      .1       0    4990     .07       0  5001.5      .1       0
Bank Sta=4990,5001.5
XS Rating Curve= 0 ,0
Exp/Cntr=0.3,0.1

Type RM Length L Ch R = 1 ,23339   ,560,560,560
BEGIN DESCRIPTION:
Liveoak Creek 27.0
END DESCRIPTION:
XS GIS Cut Line= 3
      2036711.99     13456797.43        2035475.       13456625.
      2034274.98       13456325.
#Sta/Elev= 30
    3767  445.18    3875   438.5  3955.8  430.58  4039.9  425.01  4066.9  420.83
  4127.4  417.82  4177.9  419.01  4268.8     415  4672.7  416.04    4694  414.72
    4703   412.4  4753.4  417.98  4783.7  413.63  4803.9  416.18  4975.1  417.03
  4985.7  415.83    4990  410.25  4990.6  409.45  5001.5  410.25  5013.4  415.78
  5026.3  416.44  5139.6  415.13    5150  412.72  5162.8  415.61  5533.9  418.66
  5562.3  414.32  5575.1  417.76  5758.1  419.62    6057  429.34  6252.9  440.76
#Mann= 3 ,-1 , 0
    3767      .1       0    4990     .07       0  5001.5      .1       0
Bank Sta=4990,5001.5
XS Rating Curve= 0 ,0
Exp/Cntr=0.3,0.1

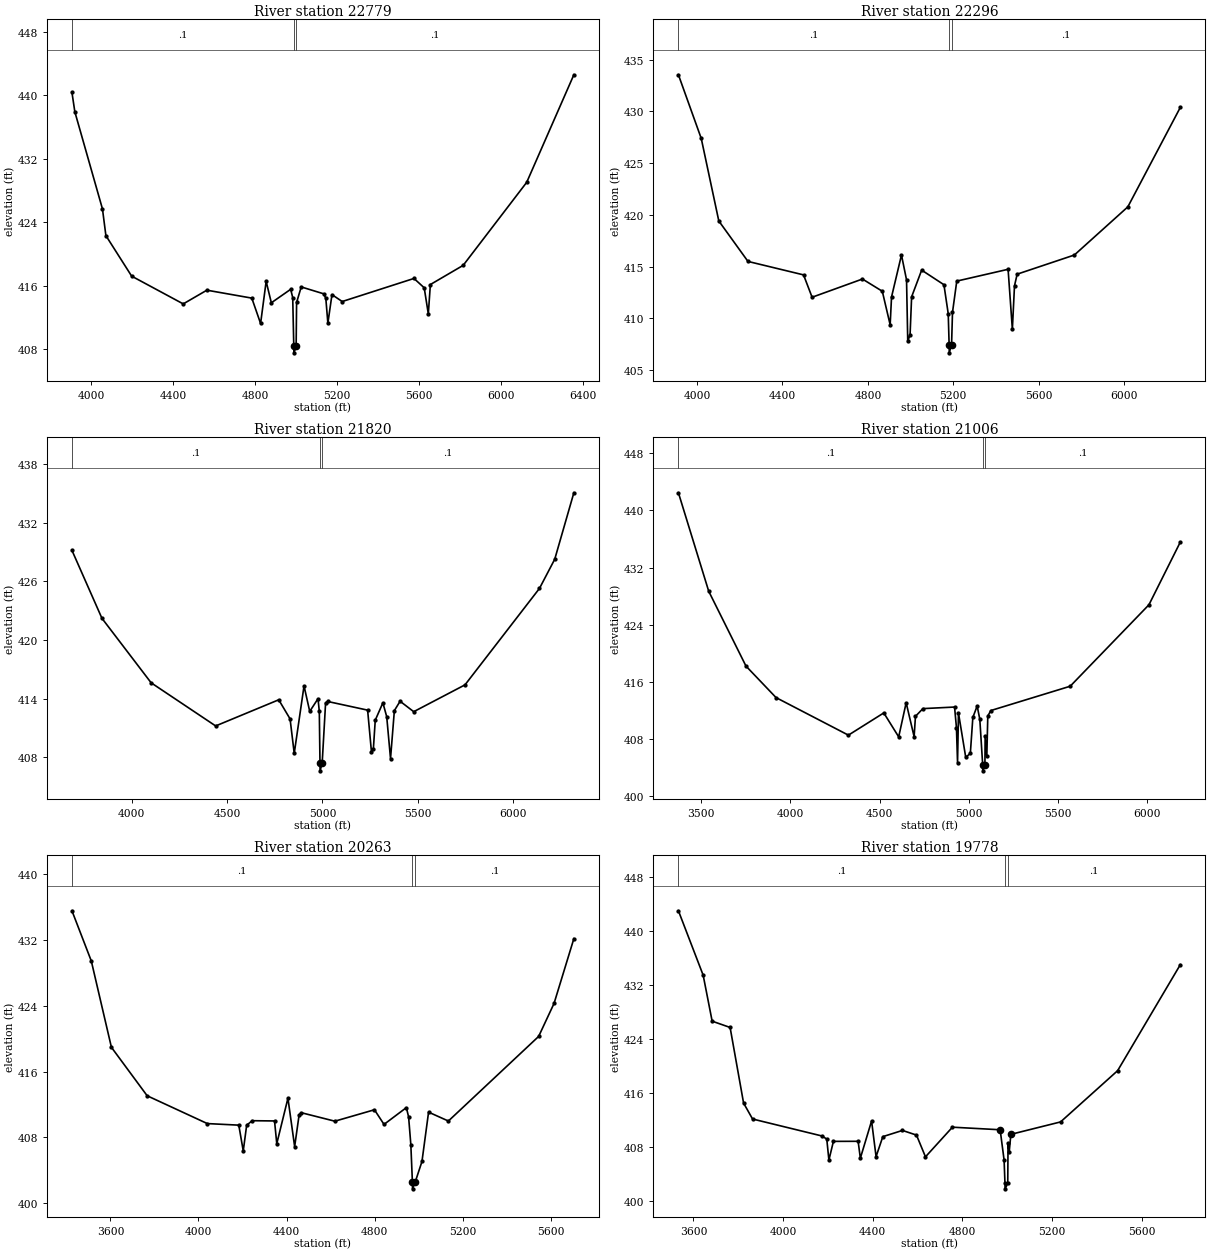
Type RM Length L Ch R = 1 ,22779   ,483,483,483
BEGIN DESCRIPTION:
Liveoak Creek 26.0
END DESCRIPTION:
XS GIS Cut Line= 3
      2036672.93     13456554.38        2035625.       13456225.
      2034274.98       13456225.
#Sta/Elev= 30
  3907.6  440.37  3921.7  437.92  4056.5  425.67  4073.2  422.31  4198.9   417.2
  4450.5   413.7  4565.8  415.43    4785  414.43  4827.9  411.23    4855  416.54
  4880.3  413.84  4974.6  415.54  4984.6   414.5  4989.8  408.33  4990.4  407.53
  5001.3  408.33  5003.5  413.88  5026.1  415.84  5136.1  414.97  5146.1   414.4
  5156.1  411.27  5176.1  414.87  5226.1     414  5576.1  416.91  5626.1  415.73
  5646.1  412.44  5656.1  416.14  5816.1  418.56  6126.1  429.03  6356.1  442.59
#Mann= 3 ,-1 , 0
  3907.6      .1       0  4989.8     .07       0  5001.3      .1       0
Bank Sta=4989.8,5001.3
XS Rating Curve= 0 ,0
Exp/Cntr=0.3,0.1

Type RM Length L Ch R = 1 ,22296   ,476,476,476
BEGIN DESCRIPTION:
Liveoak Creek 25.0
END DESCRIPTION:
XS GIS Cut Line= 3
      2036755.42     13456302.65      2035653.98      13455841.2
      2034499.52     13455897.03
#Sta/Elev= 30
  3912.9  433.53  4019.8  427.38    4102  419.41  4238.6   415.5  4498.8   414.2
  4538.8  412.04  4774.5   413.8  4867.5  412.62  4904.3  409.38  4910.8  412.07
  4957.3  416.12    4981  413.72  4986.7  407.77  4997.6  408.44  5004.8  412.08
  5051.8  414.66  5156.1  413.25  5176.2  410.45  5180.4  407.47    5181  406.67
  5191.9  407.47  5196.2  410.58  5216.2   413.6  5456.5  414.74  5476.5  408.95
  5486.5  413.15    5499  414.27  5766.8  416.12  6017.1  420.77  6262.9  430.38
#Mann= 3 ,-1 , 0
  3912.9      .1       0  5180.4     .07       0  5191.9      .1       0
Bank Sta=5180.4,5191.9
XS Rating Curve= 0 ,0
Exp/Cntr=0.3,0.1

Type RM Length L Ch R = 1 ,21820   ,814,814,814
BEGIN DESCRIPTION:
Liveoak Creek 24.0
END DESCRIPTION:
XS GIS Cut Line= 4
      2036877.55     13456216.27        2035725.       13455575.
      2035257.28      13455591.2      2034414.83      13455572.1
#Sta/Elev= 30
  3687.7  429.19  3844.8  422.23  4102.6  415.62  4440.6   411.2  4771.1  413.88
  4830.5  411.92  4852.3  408.39  4903.6   415.3  4933.5  412.69  4976.9  413.99
  4983.7  412.69  4987.2   407.4  4987.8   406.6  4998.7   407.4  5016.6  413.56
  5026.6  413.71  5236.8  412.82  5256.8  408.56  5266.8  408.81  5276.8  411.79
  5316.8  413.57  5336.8  412.15  5356.8  407.85  5376.9  412.77  5406.9  413.73
  5478.3  412.66    5747  415.41  6137.1  425.29  6217.1  428.28  6317.3  435.09
#Mann= 3 ,-1 , 0
  3687.7      .1       0  4987.2     .07       0  4998.7      .1       0
Bank Sta=4987.2,4998.7
XS Rating Curve= 0 ,0
Exp/Cntr=0.3,0.1

Type RM Length L Ch R = 1 ,21006   ,743,743,743
BEGIN DESCRIPTION:
Liveoak Creek 23.0
END DESCRIPTION:
XS GIS Cut Line= 4
      2037067.74     13454805.75      2035483.71     13455274.96
      2035117.96     13455457.08      2034369.67      13455407.2
#Sta/Elev= 30
  3373.6  442.45  3543.3  428.68  3751.9  418.22  3920.4  413.81  4325.5  408.56
  4523.7  411.67  4607.1  408.32  4648.9  413.09  4693.5  408.35    4701  411.19
  4742.7  412.27    4920  412.49  4930.5  409.62  4936.7  404.71  4941.9  411.66
  4982.6  405.45  5008.4  406.03  5022.4  411.04  5046.6  412.64  5061.4  410.77
  5077.5  404.37    5078  403.57  5089.9  404.37  5091.3  408.43  5100.6  405.61
  5106.1  411.23  5122.9     412  5567.5   415.4  6008.5  426.79  6184.2  435.56
#Mann= 3 ,-1 , 0
  3373.6      .1       0  5077.5     .07       0  5089.9      .1       0
Bank Sta=5077.5,5089.9
XS Rating Curve= 0 ,0
Exp/Cntr=0.3,0.1

Type RM Length L Ch R = 1 ,20263   ,485,485,485
BEGIN DESCRIPTION:
Liveoak Creek 22.0
END DESCRIPTION:
XS GIS Cut Line= 3
      2036831.64     13454753.66        2035275.       13455025.
      2034575.01       13455025.
#Sta/Elev= 30
  3425.3  435.55  3513.2  429.45  3604.6  418.96    3767  413.07  4040.3  409.69
  4183.2   409.5  4203.5  406.37    4219  409.49  4244.1  410.04  4345.6  410.01
  4355.8  407.25  4406.5  412.77    4437  406.89  4457.3  410.75  4467.4  411.01
  4619.7  409.98  4799.5  411.37    4843  409.59  4944.5  411.63  4954.7   410.5
  4964.8  407.14    4972  402.56  4972.5  401.76  4984.4  402.56  5015.4  405.09
  5045.4  411.08  5135.4     410  5545.4  420.28  5615.4  424.29  5705.4  432.16
#Mann= 3 ,-1 , 0
  3425.3      .1       0    4972     .07       0  4984.4      .1       0
Bank Sta=4972,4984.4
XS Rating Curve= 0 ,0
Exp/Cntr=0.3,0.1

Type RM Length L Ch R = 1 ,19778   ,615,615,615
BEGIN DESCRIPTION:
Liveoak Creek 21.0
END DESCRIPTION:
XS GIS Cut Line= 3
      2036755.22     13454541.86        2035325.       13454625.
      2034524.96     13454524.99
#Sta/Elev= 30
  3532.9     443  3643.3  433.46  3683.4  426.65  3763.5  425.72  3823.6  414.52
  3863.7  412.16  4174.2  409.64  4194.7  409.18  4204.2  406.08  4224.3  408.85
  4334.5  408.86  4344.5  406.36  4394.6  411.87  4414.6  406.59  4444.7  409.55
  4532.3  410.47  4594.9  409.78    4635  406.56  4755.2  410.95  4968.1  410.57
  4985.7  406.08  4989.6  402.62  4990.1  401.82    5002  402.62  5003.3  408.56
  5008.4  407.24  5015.9  409.89  5237.6  411.73  5492.1  419.32  5771.8  435.02
#Mann= 3 ,-1 , 0
  3532.9      .1       0  4989.6     .07       0    5002      .1       0
Bank Sta=4968.1,5015.9
XS Rating Curve= 0 ,0
Exp/Cntr=0.3,0.1

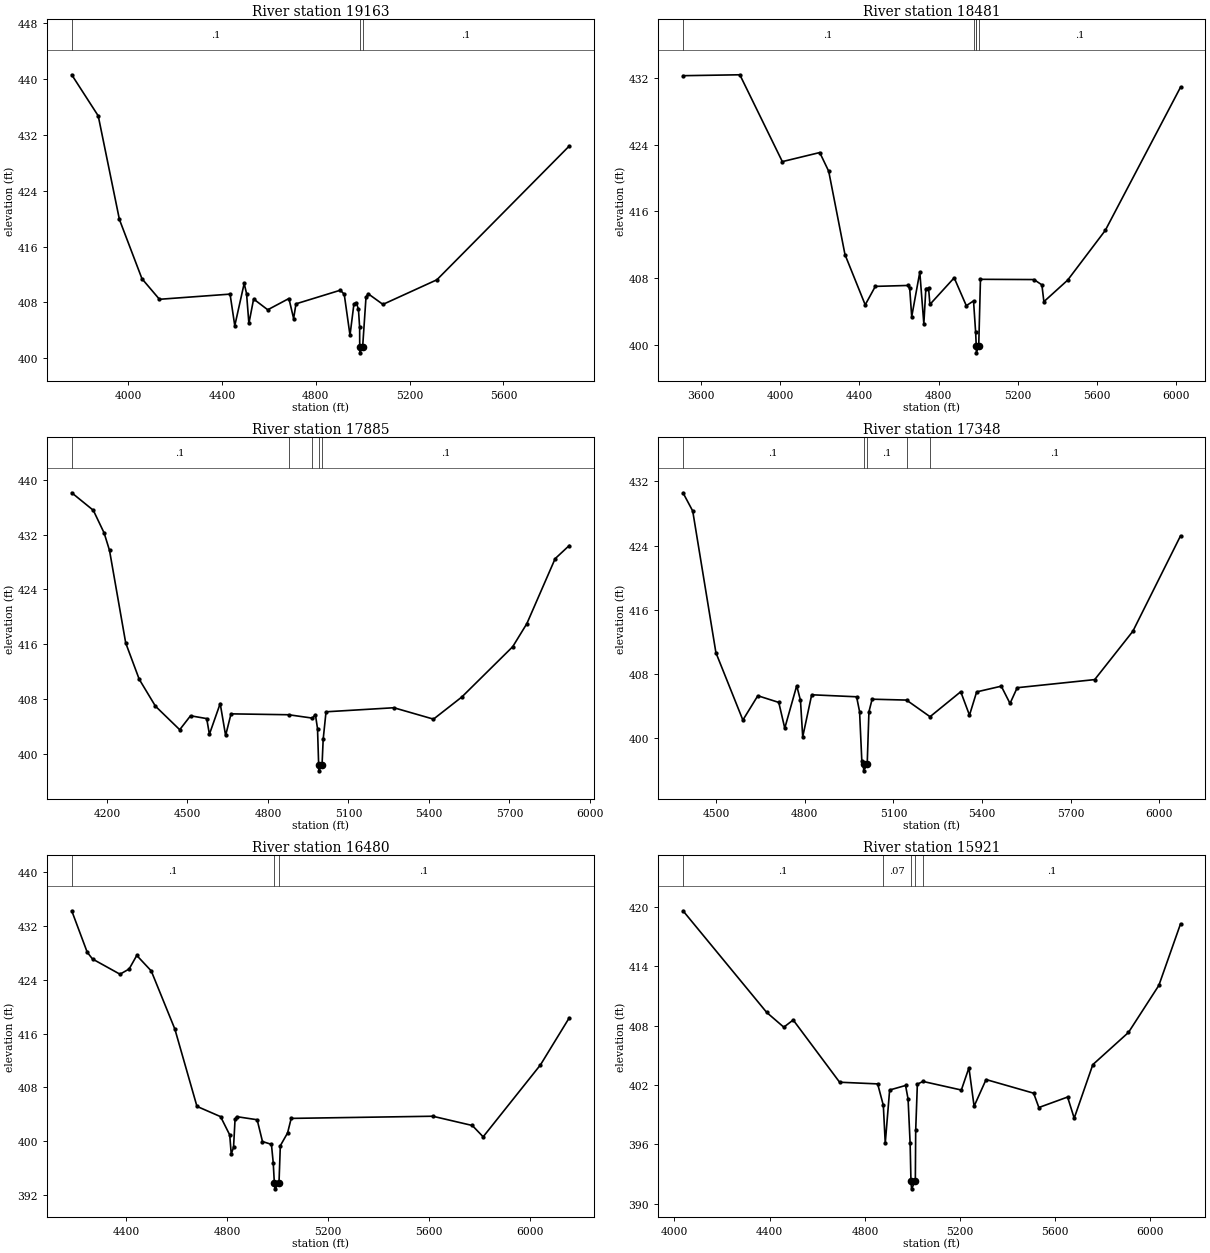
Type RM Length L Ch R = 1 ,19163   ,682,682,682
BEGIN DESCRIPTION:
Liveoak Creek 20.0
END DESCRIPTION:
XS GIS Cut Line= 4
      2036647.56     13454396.02       2035678.5     13454311.75
      2035098.43     13454166.14      2034548.21     13454145.38
#Sta/Elev= 30
  3759.5  440.57  3872.5  434.69  3962.8  419.87    4059  411.39  4133.5  408.45
  4434.6  409.19  4454.7  404.67  4494.8  410.72  4504.9  409.27  4514.9  404.99
    4535  408.49  4595.2  406.95  4685.5  408.56  4705.6   405.7  4715.7   407.8
  4904.8  409.75  4921.4  409.17    4946  403.31  4962.7  407.78    4973  407.97
    4982  407.01  4987.1  404.44  4987.4  401.59  4987.9  400.79  4999.8  401.59
  5014.2  408.74  5023.1  409.25  5086.4  407.72  5316.4  411.24  5880.9  430.38
#Mann= 3 ,-1 , 0
  3759.5      .1       0  4987.4     .07       0  4999.8      .1       0
Bank Sta=4987.4,4999.8
XS Rating Curve= 0 ,0
Exp/Cntr=0.3,0.1

Type RM Length L Ch R = 1 ,18481   ,596,596,596
BEGIN DESCRIPTION:
Liveoak Creek 19.0
END DESCRIPTION:
XS GIS Cut Line= 3
      2037106.26     13454228.64        2035625.       13453925.
      2034624.96       13453925.
#Sta/Elev= 30
  3509.4  432.32  3796.4  432.43  4010.9  421.99  4199.8  423.08  4245.1  420.83
  4327.3  410.81  4429.4  404.77  4480.4  406.99  4643.3   407.1    4654  406.75
  4664.2  403.35    4705   408.7  4725.4  402.49  4735.6  406.73  4749.3  406.78
  4756.1  404.82  4878.6  408.02  4939.8  404.67  4976.3  405.24  4986.9  401.48
  4990.1   399.8  4990.6     399  5002.5   399.8  5011.3  407.84  5281.5  407.81
  5321.5  407.17  5331.5  405.15  5451.5  407.74  5641.5  413.72  6021.5  430.94
#Mann= 5 ,-1 , 0
  3509.4      .1       0  4976.3     .07       0  4986.9      .1       0
  4990.1     .07       0  5002.5      .1       0
Bank Sta=4990.1,5002.5
XS Rating Curve= 0 ,0
Exp/Cntr=0.3,0.1

Type RM Length L Ch R = 1 ,17885   ,537,537,537
BEGIN DESCRIPTION:
Liveoak Creek 18.0
END DESCRIPTION:
XS GIS Cut Line= 3
      2036524.95     13453425.01        2035625.       13453525.
      2034724.97     13453825.01
#Sta/Elev= 30
    4069  438.08  4149.4  435.53  4189.7  432.23  4209.8  429.69  4270.2   416.2
  4320.5  410.92  4380.9     407  4471.4  403.57  4511.7   405.6    4572  405.19
  4582.1  402.91  4622.3  407.38  4642.5  402.73  4662.6  405.88  4877.5  405.75
  4965.7  405.26  4977.1  405.76    4985  403.73  4989.3  398.38  4989.8  397.58
  5001.8  398.38  5006.1  402.18  5016.7  406.18  5269.6  406.77  5417.2  405.11
  5522.6  408.33  5712.4  415.66  5765.1  419.02  5870.5  428.48  5923.2   430.4
#Mann= 5 ,-1 , 0
    4069      .1       0  4877.5     .07       0  4965.7      .1       0
  4989.3     .07       0  5001.8      .1       0
Bank Sta=4989.3,5001.8
XS Rating Curve= 0 ,0
Exp/Cntr=0.3,0.1

Type RM Length L Ch R = 1 ,17348   ,868,868,868
BEGIN DESCRIPTION:
Liveoak Creek 17.0
END DESCRIPTION:
XS GIS Cut Line= 3
        2036375.       13453275.        2035775.       13453175.
      2034775.01       13453575.
#Sta/Elev= 30
  4387.2  430.59  4420.1  428.32  4498.7  410.68    4590  402.29  4640.6  405.32
  4711.6  404.49  4731.9  401.28  4772.4  406.57  4785.1  404.74  4792.7   400.2
  4823.1  405.44  4975.2  405.19  4985.3  403.35  4992.9  397.22  4998.6  396.77
  4999.1  395.97  5011.1  396.77    5017  403.32  5027.8  404.89  5144.3  404.78
    5224  402.71    5328  405.82  5357.6   402.9  5381.9   405.8  5465.3  406.51
  5494.9  404.36  5519.2  406.32  5781.7  407.33    5911  413.35  6072.5  425.23
#Mann= 5 ,-1 , 0
  4387.2      .1       0  4998.6     .07       0  5011.1      .1       0
  5144.3     .12       0    5224      .1       0
Bank Sta=4998.6,5011.1
XS Rating Curve= 0 ,0
Exp/Cntr=0.3,0.1

Type RM Length L Ch R = 1 ,16480   ,559,559,559
BEGIN DESCRIPTION:
Liveoak Creek 16.0
END DESCRIPTION:
XS GIS Cut Line= 3
      2036702.62     13453152.74      2036056.76     13452732.59
      2035124.98     13451974.99
#Sta/Elev= 30
    4184  434.19  4245.4  428.04  4266.5  427.04  4375.2  424.79  4411.4  425.56
  4441.7  427.57    4499  425.28  4592.6  416.66  4680.2   405.2  4773.8  403.68
    4810  400.97    4816  398.15  4825.1  399.11  4831.1  403.26  4837.3  403.68
  4918.7  403.22  4939.8  399.99  4975.3  399.57  4982.5   396.8  4986.9  393.78
  4989.4  392.98  5005.2  393.78  5010.5  399.37  5039.2  401.26  5053.6  403.42
  5614.5  403.74  5771.1  402.37  5814.2  400.69  6041.2  411.35  6155.4  418.33
#Mann= 3 ,-1 , 0
    4184      .1       0  4986.9     .07       0  5005.2      .1       0
Bank Sta=4986.9,5005.2
XS Rating Curve= 0 ,0
Exp/Cntr=0.3,0.1

Type RM Length L Ch R = 1 ,15921   ,420,420,420
BEGIN DESCRIPTION:
Liveoak Creek 15.0
END DESCRIPTION:
XS GIS Cut Line= 3
      2037202.55     13452620.59      2035904.85     13452143.18
      2035359.01     13451692.64
#Sta/Elev= 30
  4035.8  419.63  4387.6  409.34  4459.4  407.85  4498.8  408.58  4693.8  402.28
  4853.7  402.11  4877.5  399.94  4885.6  396.11    4904  401.49  4970.9  401.95
  4981.5  400.58  4990.1   396.1  4993.6  392.29  4996.1  391.49    5012  392.29
  5013.5  397.41  5020.5  402.08    5044  402.36  5205.3  401.49  5237.2  403.74
  5258.9  399.85  5309.2  402.55  5509.1  401.17    5531  399.72  5651.7  400.78
  5679.5  398.64  5757.7  404.06  5907.6  407.32  6035.2  412.08  6126.3  418.31
#Mann= 5 ,-1 , 0
  4035.8      .1       0  4877.5     .07       0  4993.6     .07       0
    5012     .07       0    5044      .1       0
Bank Sta=4993.6,5012
XS Rating Curve= 0 ,0
Exp/Cntr=0.3,0.1

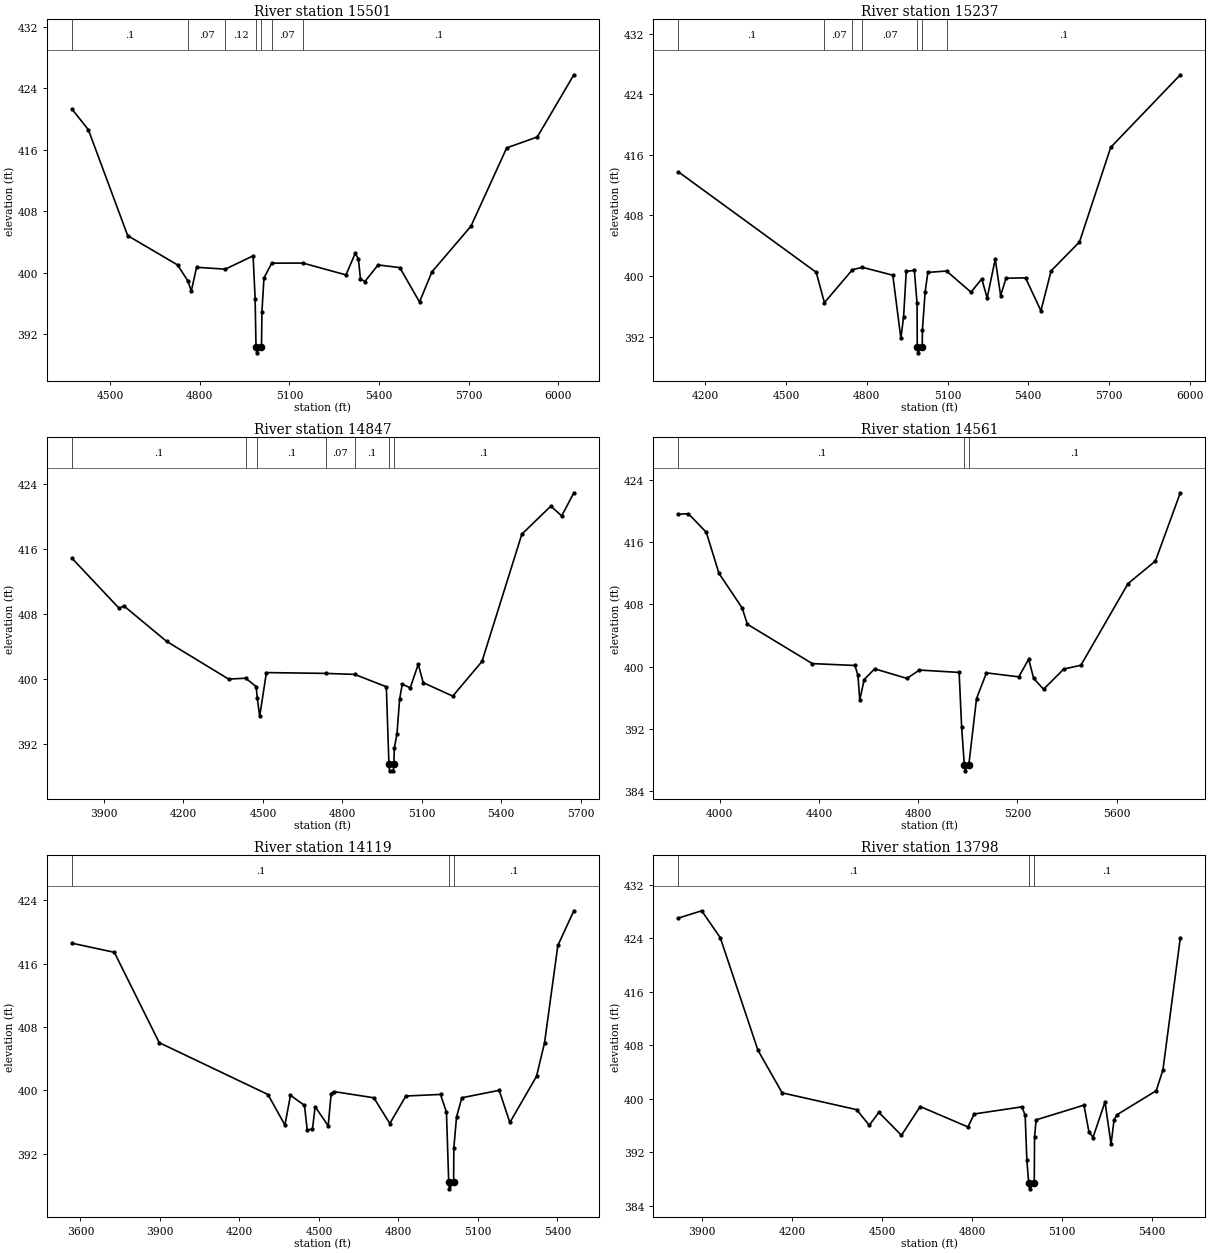
Type RM Length L Ch R = 1 ,15501   ,264,264,264
BEGIN DESCRIPTION:
Liveoak Creek 14.0
END DESCRIPTION:
XS GIS Cut Line= 3
      2036974.99     13452224.99        2036425.       13451975.
      2035424.97     13451574.99
#Sta/Elev= 30
  4371.7  421.28  4426.6   418.6  4558.4  404.83  4725.4  401.02  4760.4  398.92
  4771.5  397.61  4789.1  400.71  4885.5  400.47  4978.5   402.2  4985.3  396.63
  4988.2  390.39  4990.7  389.59  5006.6  390.39  5008.1  394.93  5014.9  399.33
  5040.9  401.25  5145.5  401.26  5289.5  399.72  5320.5  402.52  5331.3  401.82
    5338  399.22  5352.8  398.86  5397.2  401.02  5469.9  400.67  5535.9   396.2
  5577.6  400.12  5708.2  406.05    5828  416.24  5930.4  417.65  6052.9  425.74
#Mann= 7 ,-1 , 0
  4371.7      .1       0  4760.4     .07       0  4885.5     .12       0
  4988.2     .07       0  5006.6     .12       0  5040.9     .07       0
  5145.5      .1       0
Bank Sta=4988.2,5006.6
XS Rating Curve= 0 ,0
Exp/Cntr=0.3,0.1

Type RM Length L Ch R = 1 ,15237   ,390,390,390
BEGIN DESCRIPTION:
Mapping XS 6e892966
END DESCRIPTION:
XS GIS Cut Line= 4
      2037210.12     13452035.67      2036707.55     13451759.65
      2036040.89     13451723.19      2035449.87     13451525.32
#Sta/Elev= 30
  4100.5  413.74  4612.4  400.48  4642.7  396.48  4747.1  400.83  4783.8  401.14
  4896.8   400.1  4926.8  391.77  4936.8  394.54  4946.8  400.61  4976.9  400.73
  4986.9  396.37  4987.7  390.65  4990.2  389.85  5006.1  390.65  5006.9  392.92
  5016.9  397.87    5027  400.47  5096.5  400.65  5187.2  397.86  5227.3  399.61
  5247.3  397.09  5277.3  402.22  5297.4   397.4  5317.4   399.7  5389.9  399.75
    5447   395.4  5484.8  400.67  5590.3  404.49  5706.3  416.98  5964.8  426.56
#Mann= 7 ,-1 , 0
  4100.5      .1       0  4642.7     .07       0  4747.1      .1       0
  4783.8     .07       0  4987.7     .07       0  5006.1     .07       0
  5096.5      .1       0
Bank Sta=4987.7,5006.1
XS Rating Curve= 0 ,0
Exp/Cntr=0.3,0.1

Type RM Length L Ch R = 1 ,14847   ,286,286,286
BEGIN DESCRIPTION:
Mapping XS 3aab8891
END DESCRIPTION:
XS GIS Cut Line= 3
      2037369.26     13451900.12      2036382.28     13451543.35
      2035539.29      13451473.1
#Sta/Elev= 30
  3778.9  414.84  3957.3  408.68  3974.8  408.99    4136  404.64  4370.6     400
  4434.9  400.11  4474.6  399.08  4478.8  397.66  4487.9  395.43  4513.2   400.8
  4736.5   400.7  4846.2  400.58  4966.1  399.06    4976  389.54  4978.5  388.74
  4991.9  388.74  4994.4  389.54  4996.2   391.5  5006.3  393.28  5016.3  397.53
  5026.3  399.38  5056.5  398.93  5086.6  401.82  5105.6  399.56    5217  397.91
  5327.4  402.17  5477.9  417.79  5587.3  421.23  5628.4  420.03  5674.3  422.87
#Mann= 7 ,-1 , 0
  3778.9      .1       0  4434.9     .07       0  4478.8      .1       0
  4736.5     .07       0  4846.2      .1       0    4976     .07       0
  4994.4      .1       0
Bank Sta=4976,4994.4
XS Rating Curve= 0 ,0
Exp/Cntr=0.3,0.1

Type RM Length L Ch R = 1 ,14561   ,442,442,442
BEGIN DESCRIPTION:
Mapping XS b93e9c82
END DESCRIPTION:
XS GIS Cut Line= 3
      2037425.71     13451810.73      2036822.38     13451411.41
      2035524.63      13451346.3
#Sta/Elev= 30
  3833.6  419.55  3873.8  419.61    3946  417.23  3997.2  411.95  4090.4  407.53
  4111.5  405.43  4373.3  400.38  4544.8  400.14  4557.1   398.9  4564.5  395.72
  4582.4  398.34  4624.6  399.71  4754.7  398.48  4804.8  399.55    4965  399.25
    4975  392.28  4985.8  387.42  4988.3  386.62  5004.2  387.42  5035.1  395.89
  5075.1  399.19  5205.3  398.68  5245.4  400.95  5265.4  398.48  5305.4  397.09
    5387  399.69  5455.6  400.16  5645.9  410.65    5756  413.54  5856.5   422.3
#Mann= 3 ,-1 , 0
  3833.6      .1       0  4985.8     .07       0  5004.2      .1       0
Bank Sta=4985.8,5004.2
XS Rating Curve= 0 ,0
Exp/Cntr=0.3,0.1

Type RM Length L Ch R = 1 ,14119   ,321,321,321
BEGIN DESCRIPTION:
Liveoak Creek 13.0
END DESCRIPTION:
XS GIS Cut Line= 3
       2037534.2     13451771.66      2036917.87     13451194.39
      2035875.04       13451075.
#Sta/Elev= 30
  3567.8  418.57  3727.7  417.42  3897.2  406.02  4307.5  399.48  4371.5  395.63
  4392.5  399.38  4445.3  398.11  4455.7     395  4475.5  395.13  4485.6  397.95
  4534.8  395.52    4546   399.6  4556.1  399.85    4707  399.07  4767.4  395.82
  4827.8  399.29  4958.7  399.49  4981.1  397.25  4989.7  388.38  4992.2  387.58
  5008.1  388.38    5009  392.73  5019.1  396.64  5039.2  399.07  5180.1  400.01
  5220.4  395.95    5321  401.77  5351.2  405.99  5401.5  418.28  5461.9  422.66
#Mann= 3 ,-1 , 0
  3567.8      .1       0  4989.7     .07       0  5008.1      .1       0
Bank Sta=4989.7,5008.1
XS Rating Curve= 0 ,0
Exp/Cntr=0.3,0.1

Type RM Length L Ch R = 1 ,13798   ,160,160,160
BEGIN DESCRIPTION:
Liveoak Creek 12.0
END DESCRIPTION:
XS GIS Cut Line= 3
        2037525.       13451225.      2036342.78     13450809.56
        2035925.       13450775.
#Sta/Elev= 30
  3821.9  427.02  3899.4  428.11  3961.3  424.09  4086.9  407.24  4167.6  400.87
  4415.5  398.36  4457.9  396.02  4489.7  397.95    4565  394.52  4627.5  398.82
  4786.5  395.77  4807.7  397.71  4966.6  398.78  4977.2   397.5  4982.9  390.79
  4989.2  387.31  4991.7  386.51  5007.6  387.31  5008.5  394.26  5013.8  396.83
  5173.1  399.03  5189.5  395.08  5203.2  394.19  5243.3  399.51  5263.4  393.18
  5273.5  396.86  5283.5   397.6  5413.9  401.19  5436.3  404.32  5494.2  424.07
#Mann= 3 ,-1 , 0
  3821.9      .1       0  4989.2     .07       0  5007.6      .1       0
Bank Sta=4989.2,5007.6
XS Rating Curve= 0 ,0
Exp/Cntr=0.3,0.1