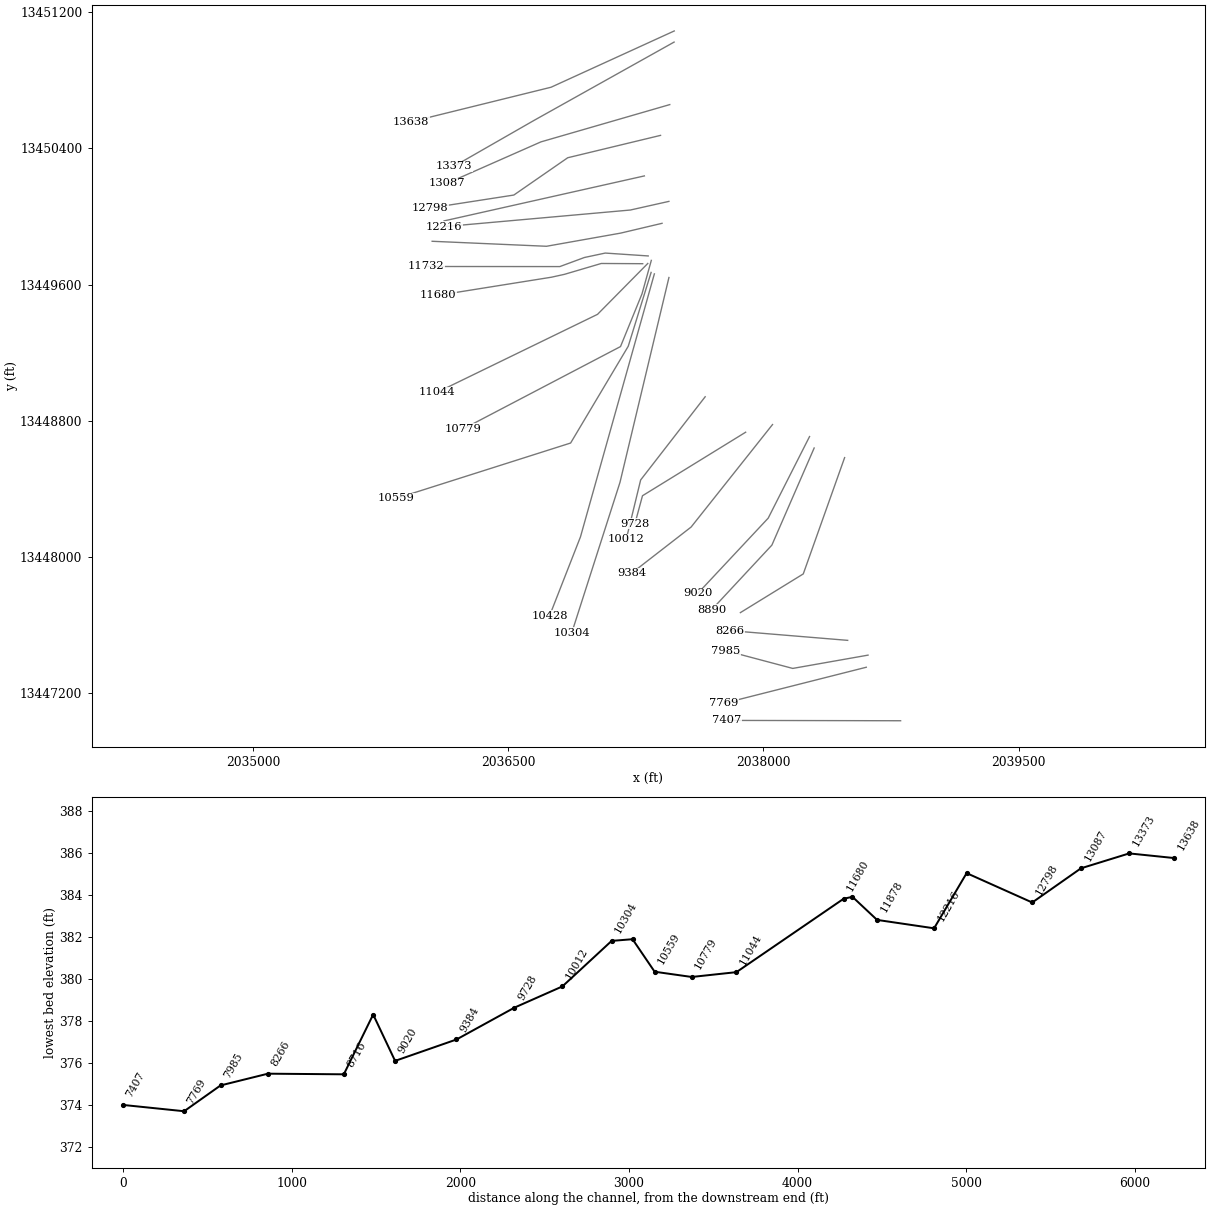
HEC-RAS study Liveoak Creek.prj: Liveoak Creek Base Level Engineering

--- Liveoak Creek.g01 (geometry) --- (continued)

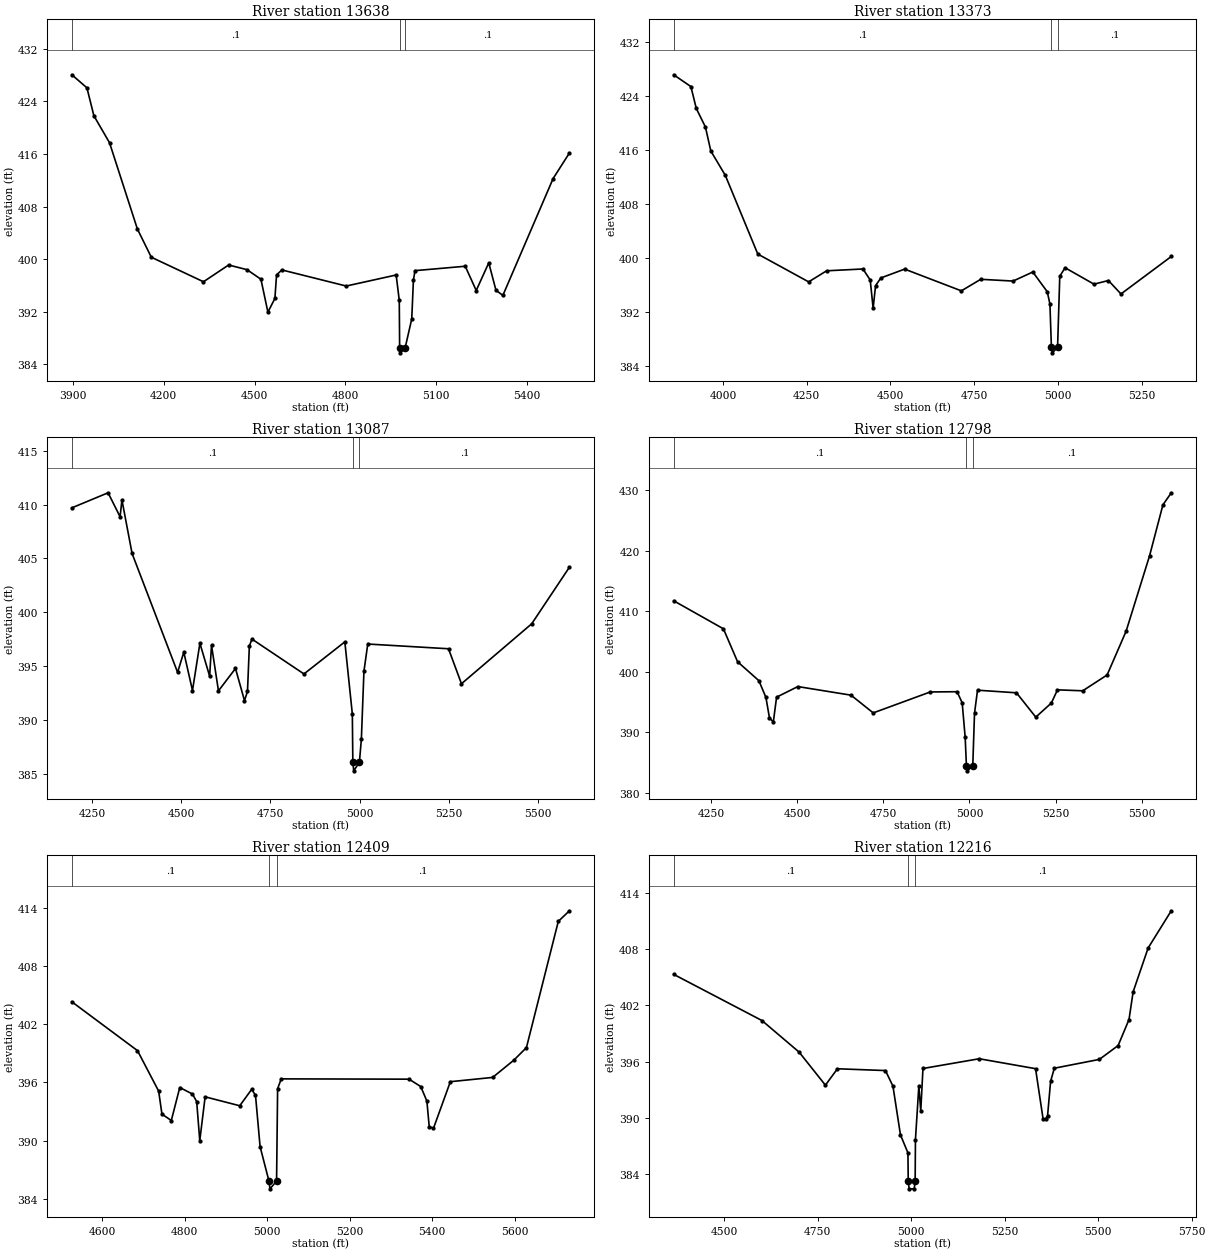
Type RM Length L Ch R = 1 ,13638   ,265,265,265
BEGIN DESCRIPTION:
Mapping XS f8492de3
END DESCRIPTION:
XS GIS Cut Line= 3
      2037475.78     13451090.38      2036751.82     13450759.65
      2035929.43     13450556.65
#Sta/Elev= 30
  3896.9  428.05  3946.6  426.07  3969.6  421.82  4021.2  417.72  4113.3  404.59
  4159.3   400.3  4331.5  396.57  4414.5  399.12  4475.2  398.41  4521.2  396.95
  4544.2  391.95  4567.3  394.03  4572.8  397.61  4590.3  398.37  4802.9  395.92
  4967.7   397.6    4978  393.74  4979.2  386.56  4981.7  385.76  4997.6  386.56
  5019.2  390.92  5024.7  396.81  5029.9  398.26  5195.8  398.93  5232.1  395.24
  5273.5  399.45  5297.3  395.27  5320.1   394.5    5486  412.27  5539.9  416.16
#Mann= 3 ,-1 , 0
  3896.9      .1       0  4979.2     .07       0  4997.6      .1       0
Bank Sta=4979.2,4997.6
XS Rating Curve= 0 ,0
Exp/Cntr=0.3,0.1

Type RM Length L Ch R = 1 ,13373   ,286,286,286
BEGIN DESCRIPTION:
Liveoak Creek 11.0
END DESCRIPTION:
XS GIS Cut Line= 3
      2037474.99     13451024.99      2036651.81     13450564.76
      2036180.49     13450294.71
#Sta/Elev= 30
  3852.5  427.16  3903.9  425.41  3919.9  422.18  3947.3  419.42  3963.3  415.88
  4006.7  412.26  4103.7  400.61  4255.6  396.49  4309.3  398.13  4417.8   398.4
  4439.5  396.77  4448.2  392.59  4455.5  395.93  4471.2  397.07  4542.3  398.38
  4711.7  395.16  4769.6  396.87  4866.2  396.61  4925.2  397.95  4968.3  395.03
  4976.3  393.21  4980.7  386.78  4983.2  385.98  4999.1  386.78  5005.7  397.33
  5021.6  398.58  5107.9  396.15    5151  396.69  5188.5   394.7  5338.8  400.25
#Mann= 3 ,-1 , 0
  3852.5      .1       0  4980.7     .07       0  4999.1      .1       0
Bank Sta=4980.7,4999.1
XS Rating Curve= 0 ,0
Exp/Cntr=0.3,0.1

Type RM Length L Ch R = 1 ,13087   ,289,289,289
BEGIN DESCRIPTION:
Mapping XS daf48772
END DESCRIPTION:
XS GIS Cut Line= 3
      2037449.55     13450657.64      2036692.18     13450438.46
      2036138.29     13450193.97
#Sta/Elev= 30
    4194   409.7  4295.5   411.1  4329.1  408.87  4334.3  410.43  4362.7  405.46
  4490.2  394.42  4507.6  396.29  4531.9  392.73  4552.7  397.12    4580  394.06
  4585.2  396.93  4604.7   392.7  4652.4  394.78  4677.6  391.79    4686  392.65
  4691.2  396.85  4698.4  397.51  4844.2  394.27  4958.7  397.25  4979.7  390.55
  4981.1  386.07  4983.6  385.27  4999.5  386.07    5005  388.21  5012.2  394.51
  5022.9  397.05  5249.1  396.61  5285.4  393.36  5482.2  398.93  5587.9  404.19
#Mann= 3 ,-1 , 0
    4194      .1       0  4981.1     .07       0  4999.5      .1       0
Bank Sta=4981.1,4999.5
XS Rating Curve= 0 ,0
Exp/Cntr=0.3,0.1

Type RM Length L Ch R = 1 ,12798   ,389,389,389
BEGIN DESCRIPTION:
Mapping XS ea24f162
END DESCRIPTION:
XS GIS Cut Line= 4
      2037395.27     13450476.76      2036849.73     13450345.25
      2036533.14     13450126.08      2036041.04     13450049.84
#Sta/Elev= 30
  4141.5  411.73  4285.8   407.1  4326.9  401.66  4388.8  398.53  4409.2  395.76
  4419.5  392.36  4430.7  391.72  4440.1  395.81  4501.8  397.56  4656.1  396.14
  4720.6  393.21  4886.2  396.67  4963.9  396.71  4978.8  394.88  4987.5  389.15
  4991.1  384.44  4993.6  383.64  5009.5  384.44  5014.6  393.16  5023.3  396.96
  5136.4  396.53  5192.4  392.51  5237.6  394.84  5255.4  397.02  5328.7  396.86
  5399.5  399.48  5454.6  406.71  5522.7  419.17  5561.4  427.57  5585.7  429.57
#Mann= 3 ,-1 , 0
  4141.5      .1       0  4991.1     .07       0  5009.5      .1       0
Bank Sta=4991.1,5009.5
XS Rating Curve= 0 ,0
Exp/Cntr=0.3,0.1

Type RM Length L Ch R = 1 ,12409   ,193,193,193
BEGIN DESCRIPTION:
Mapping XS bf06e460
END DESCRIPTION:
XS GIS Cut Line= 2
      2037300.26     13450238.49      2036123.28     13449974.15
#Sta/Elev= 30
  4526.9  404.31    4686  399.28  4737.3  395.11  4745.3  392.74    4768  392.08
  4788.5  395.48  4819.3  394.81  4829.5  394.03    4837  390.01    4850  394.52
  4933.9   393.6  4962.8  395.29  4972.1  394.68  4983.2   389.4  5004.7  385.84
  5007.2  385.04  5023.2  385.84  5025.7  395.36  5034.5  396.37  5344.3  396.34
  5372.7  395.58  5387.6  394.08  5393.2  391.46  5403.5  391.27  5444.5  396.08
    5547  396.52  5598.2  398.29  5628.9  399.59  5706.2   412.6  5733.2  413.69
#Mann= 3 ,-1 , 0
  4526.9      .1       0  5004.7     .07       0  5023.2      .1       0
Bank Sta=5004.7,5023.2
XS Rating Curve= 0 ,0
Exp/Cntr=0.3,0.1

Type RM Length L Ch R = 1 ,12216   ,338,338,338
BEGIN DESCRIPTION:
Mapping XS 1a039a08
END DESCRIPTION:
XS GIS Cut Line= 3
      2037444.46     13450088.83      2037217.91     13450038.05
      2036123.34      13449940.3
#Sta/Elev= 30
  4364.4  405.31  4600.5  400.38  4699.9  397.01  4770.2  393.48  4802.4  395.23
  4930.8  395.04  4950.9  393.38    4971  388.17    4991  386.25  4991.8  383.21
  4994.3  382.41  5007.8  382.41  5010.3  383.21  5011.1  387.67  5020.2  393.41
  5025.3  390.72  5031.2  395.26  5181.8   396.3  5332.4  395.24  5352.5  389.88
  5359.6   389.9  5364.6  390.23  5372.6  393.88  5382.6  395.29  5503.1  396.23
  5553.3  397.71  5582.4  400.49  5593.4  403.44  5633.6  408.13  5695.5   412.1
#Mann= 3 ,-1 , 0
  4364.4      .1       0  4991.8     .07       0  5010.3      .1       0
Bank Sta=4991.8,5010.3
XS Rating Curve= 0 ,0
Exp/Cntr=0.3,0.1

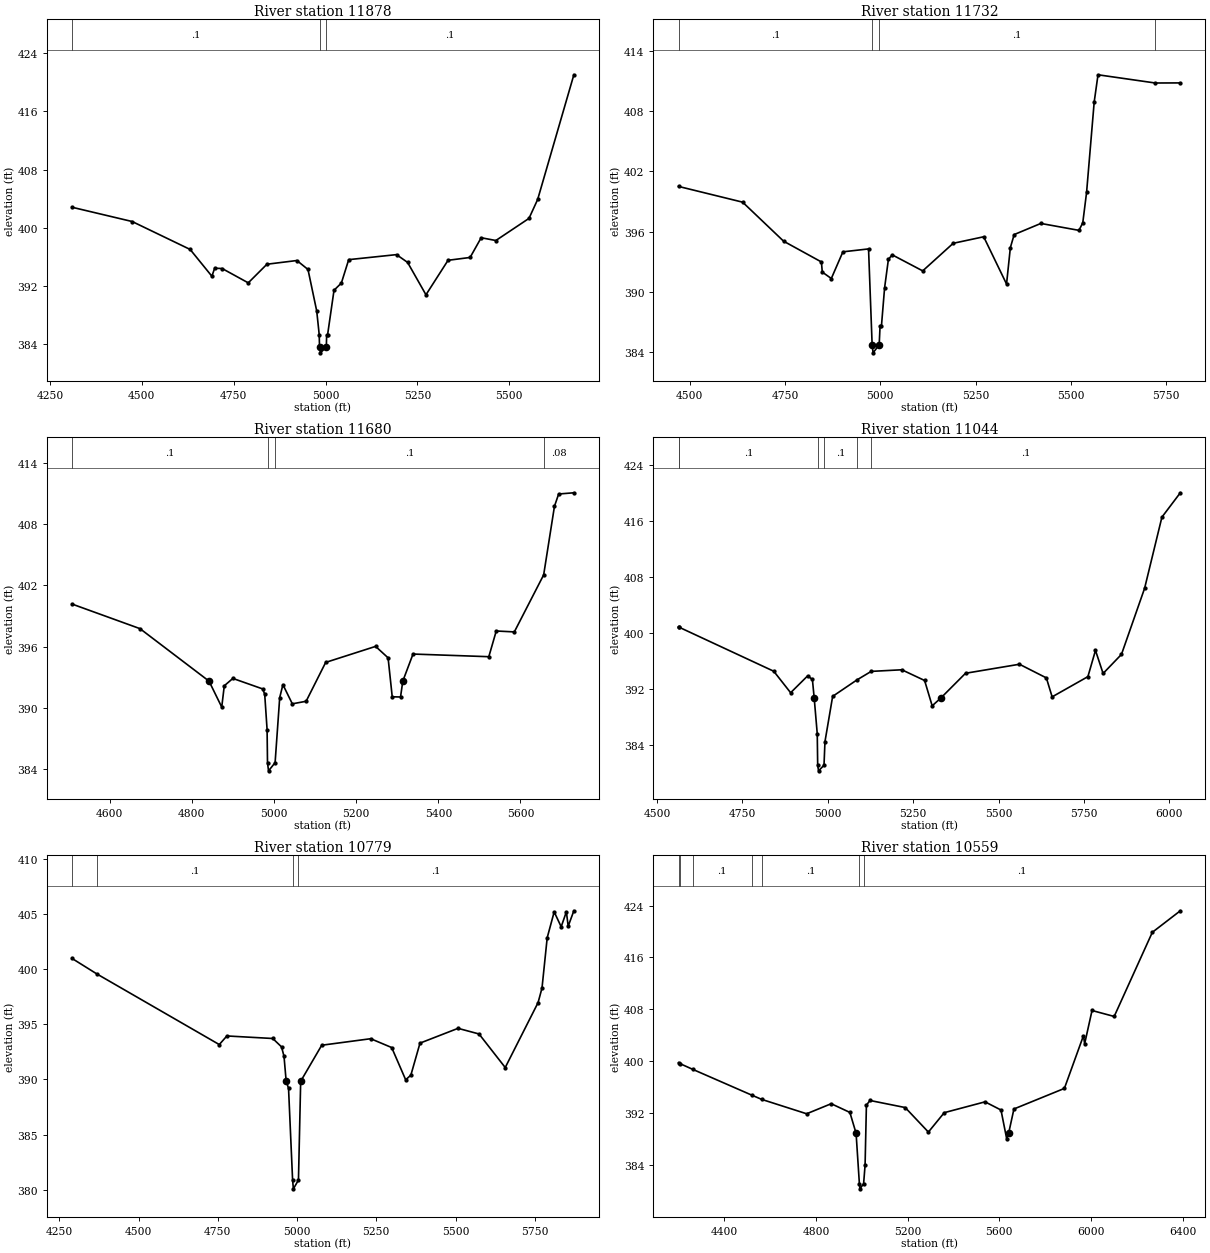
Type RM Length L Ch R = 1 ,11878   ,146,146,146
BEGIN DESCRIPTION:
Liveoak Creek 10.0
END DESCRIPTION:
XS GIS Cut Line= 4
      2037404.13     13449959.93      2037160.53     13449902.29
        2036725.       13449825.      2036053.01     13449854.36
#Sta/Elev= 30
  4310.4  402.82  4473.9  400.86  4631.7  397.02  4690.8  393.34  4698.4  394.44
  4718.7   394.4  4789.8  392.43  4840.6  394.99  4922.1   395.5  4952.3  394.27
  4976.1  388.55  4982.8  385.33  4983.7  383.61  4986.2  382.81  5002.2  383.61
  5003.1  385.28  5005.6  385.28  5023.1  391.41  5043.1   392.4  5063.1  395.62
  5193.2  396.31  5223.3  395.24  5273.3  390.79  5333.4  395.53  5393.4  395.92
  5423.5  398.63  5463.5  398.25  5553.6  401.29  5577.2  403.89  5675.7  421.03
#Mann= 3 ,-1 , 0
  4310.4      .1       0  4983.7     .07       0  5002.2      .1       0
Bank Sta=4983.7,5002.2
XS Rating Curve= 0 ,0
Exp/Cntr=0.3,0.1

Type RM Length L Ch R = 1 ,11732   ,52,52,52
BEGIN DESCRIPTION:
Mapping XS 83074a44
END DESCRIPTION:
XS GIS Cut Line= 5
      2037322.83     13449768.17      2037070.25      13449785.1
      2036947.85     13449759.06      2036803.32     13449705.67
      2036018.98      13449706.2
#Sta/Elev= 30
  4470.7   400.5  4638.9  398.93  4746.4  395.04  4845.6  392.97  4847.9  391.96
  4871.6  391.32    4902  393.98  4969.3  394.27  4978.7  384.71  4981.2  383.91
  4997.2  384.71  4999.5  386.57  5003.1  386.57  5011.4  390.39  5021.4  393.23
  5031.4  393.68  5111.4  392.08  5191.4  394.83  5271.4  395.48  5331.4  390.77
  5341.4   394.4  5351.4   395.7  5421.4  396.81  5521.4  396.12  5531.4  396.87
  5541.4   399.9  5561.4  408.92  5571.4  411.63  5721.7  410.81  5787.4  410.82
#Mann= 4 ,-1 , 0
  4470.7      .1       0  4978.7     .07       0  4997.2      .1       0
  5721.7     .08       0
Bank Sta=4978.7,4997.2
XS Rating Curve= 0 ,0
Exp/Cntr=0.3,0.1

Type RM Length L Ch R = 1 ,11680   ,636,636,636
BEGIN DESCRIPTION:
Mapping XS 7d5020a8
END DESCRIPTION:
XS GIS Cut Line= 5
      2037290.33      13449722.6      2037046.81      13449723.9
      2036830.67      13449660.1      2036753.84     13449643.17
      2036088.43     13449536.91
#Sta/Elev= 30
  4508.5  400.17  4673.8  397.76 4841.88392.6136  4872.8  390.07    4879  392.16
  4899.9  392.88  4972.5  391.85  4977.4  391.33  4983.2  387.86  4984.2  384.62
  4986.7  383.82  5002.7  384.62  5013.9     391  5021.7  392.27  5044.6  390.39
  5078.2  390.64  5125.8  394.45  5247.3  396.02  5277.7   394.9  5287.8  391.08
    5308  391.06 5313.52392.6132  5338.4  395.27  5522.9  395.01    5541  397.53
    5585  397.44  5656.4  403.03  5682.7  409.76  5692.9  410.96  5729.9  411.08
#Mann= 4 ,-1 , 0
  4508.5      .1       0  4984.2     .07       0  5002.7      .1       0
  5656.4     .08       0
Bank Sta=4841.88,5313.52
XS Rating Curve= 0 ,0
Exp/Cntr=0.3,0.1

Type RM Length L Ch R = 1 ,11044   ,265,265,265
BEGIN DESCRIPTION:
Liveoak Creek 9.0
END DESCRIPTION:
XS GIS Cut Line= 3
      2037320.26     13449723.91        2037025.       13449425.
      2036081.64     13448966.34
#Sta/Elev= 30
  4562.9  400.88  4565.5  400.82  4841.7  394.55  4891.1  391.48  4940.7  393.88
  4954.8  393.39 4960.07390.7324    4969  385.62  4970.3  381.12  4972.8  380.32
  4988.8  381.12  4991.6  384.49  5014.1  390.96  5085.8  393.33    5127  394.53
  5216.6  394.76  5283.3  393.23  5305.5  389.61 5331.02 390.733  5403.1  394.26
    5561  395.55  5639.8   393.6  5656.7  390.89  5761.4  393.78  5783.6  397.53
  5805.9  394.23  5859.7  396.96  5927.4   406.4  5978.1  416.57    6032  420.05
#Mann= 6 ,-1 , 0
  4562.9     .05       0  4565.5      .1       0  4970.3     .07       0
  4988.8      .1       0  5085.8     .16       0    5127      .1       0
Bank Sta=4960.07,5331.02
XS Rating Curve= 0 ,0
Exp/Cntr=0.3,0.1

Type RM Length L Ch R = 1 ,10779   ,220,220,220
BEGIN DESCRIPTION:
Mapping XS c9d9fcec
END DESCRIPTION:
XS GIS Cut Line= 4
      2037341.09     13449742.14      2037286.39     13449545.51
      2037160.09     13449235.62      2036234.96     13448751.25
#Sta/Elev= 30
  4290.3  400.96  4368.4  399.56  4754.7  393.16  4778.7  393.94  4923.4  393.71
  4951.1  392.95  4958.9   392.1 4965.73389.8366  4973.2   389.2    4986  380.89
  4988.5  380.09  5004.5  380.89  5011.5389.8342  5077.9   393.1  5232.4  393.69
  5298.6  392.89  5342.7  389.97  5359.1  390.39  5387.9  393.29  5507.9  394.63
  5574.1  394.12  5656.8  391.08  5760.4  396.96  5772.8  398.28  5789.2  402.84
  5811.2  405.18  5833.3  403.83  5849.7  405.19  5855.4  403.88  5873.3  405.28
#Mann= 4 ,-1 , 0
  4290.3     .05       0  4368.4      .1       0    4986     .07       0
  5004.5      .1       0
Bank Sta=4965.73,5011.5
XS Rating Curve= 0 ,0
Exp/Cntr=0.3,0.1

Type RM Length L Ch R = 1 ,10559   ,131,131,131
BEGIN DESCRIPTION:
Mapping XS 69f29ddb
END DESCRIPTION:
XS GIS Cut Line= 4
      2037339.93     13449671.39      2037205.38     13449237.34
      2036866.84     13448668.76      2035842.58     13448343.26
#Sta/Elev= 30
  4199.5  399.78  4205.3  399.65  4260.7  398.77  4518.2   394.8  4562.4  394.13
  4758.9  391.91  4866.1  393.46  4947.6  392.12 4974.73388.9021  4989.1  381.14
  4991.6  380.34  5007.6  381.14    5014  383.99  5019.8  393.24  5035.4  393.96
  5189.2  392.87  5290.4  389.09  5359.6  392.08  5537.7  393.75  5607.4  392.49
  5632.4  388.03 5640.72388.9018  5663.9  392.65  5884.2  395.82  5967.4  403.94
  5972.7  402.71  6004.9  407.83  6101.6  406.91  6268.1  419.88  6390.4   423.2
#Mann= 7 ,-1 , 0
  4199.5     .05       0  4205.3     .08       0  4260.7      .1       0
  4518.2     .08       0  4562.4      .1       0  4989.1     .07       0
  5007.6      .1       0
Bank Sta=4974.73,5640.72
XS Rating Curve= 0 ,0
Exp/Cntr=0.3,0.1

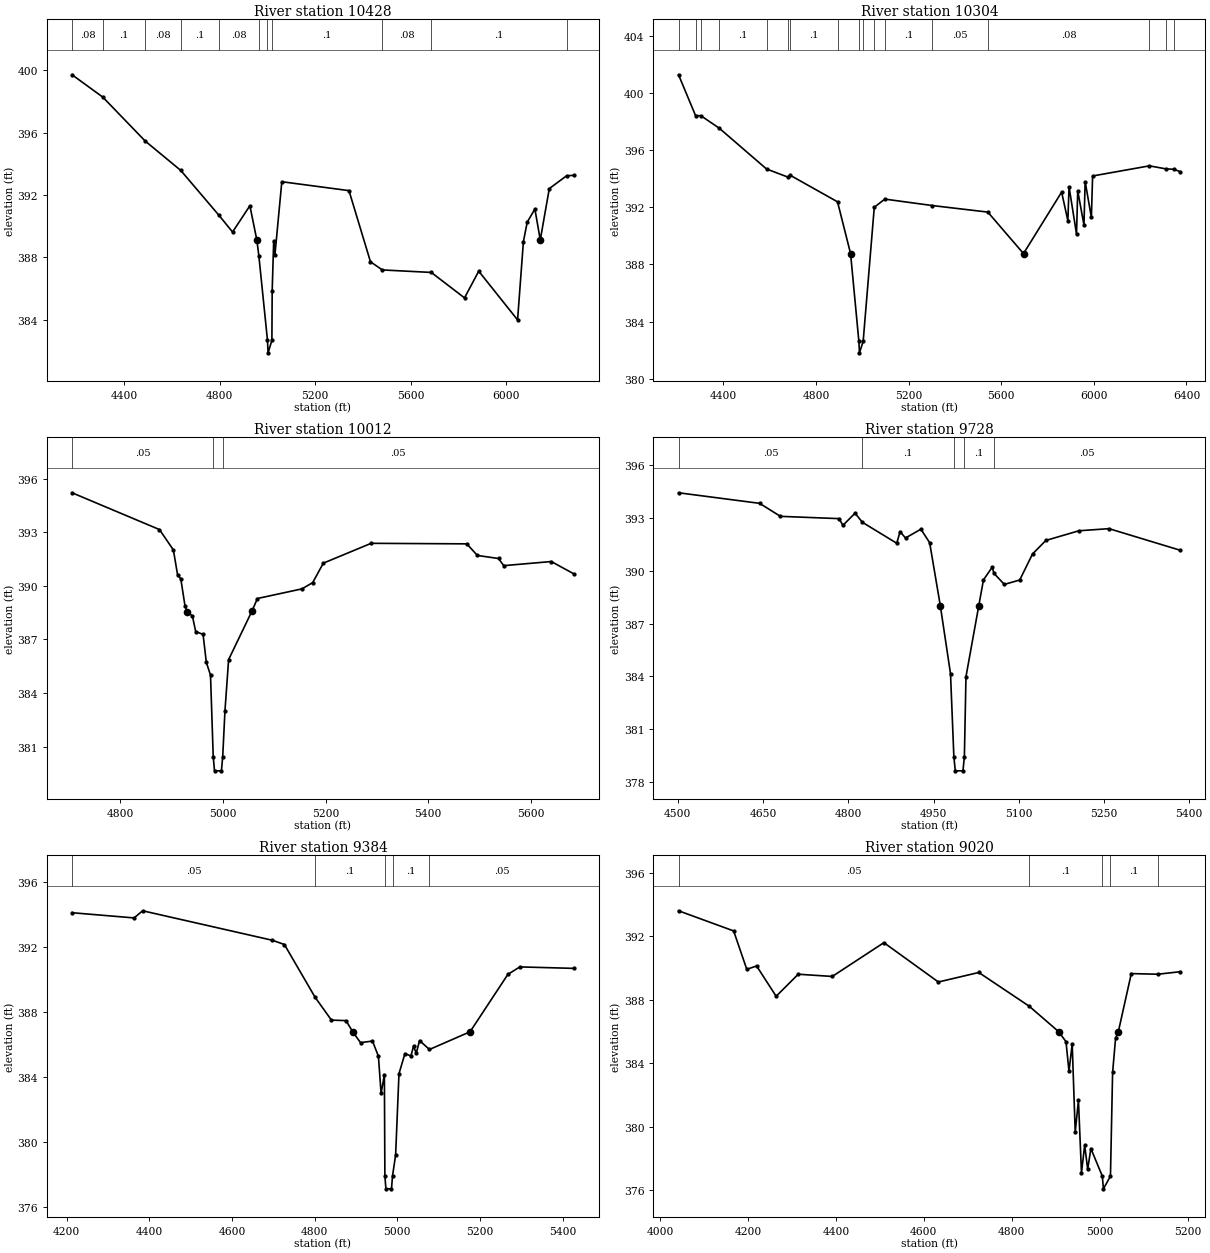
Type RM Length L Ch R = 1 ,10428   ,124,124,124
BEGIN DESCRIPTION:
Liveoak Creek 8.0
END DESCRIPTION:
XS GIS Cut Line= 3
      2037358.98      13449662.8      2036924.75     13448117.33
      2036742.95     13447652.85
#Sta/Elev= 30
  4180.5   399.7  4309.3  398.27  4486.8  395.46  4636.5  393.57  4796.9  390.69
  4853.4  389.63  4926.1  391.31 4955.24389.1221  4963.7  388.11  4999.9  382.69
  5002.4  381.89  5018.4  382.69  5019.6  385.86  5025.9  389.05  5031.1  388.16
    5060  392.85  5341.6  392.28  5431.8  387.72  5481.6   387.2  5686.8  387.04
  5826.1  385.41  5885.7  387.12  6048.6     384    6073  389.01    6089  390.26
  6121.2   391.1 6143.76389.1234  6181.6  392.41  6254.1  393.23  6284.6  393.26
#Mann= 11 ,-1 , 0
  4180.5     .08       0  4309.3      .1       0  4486.8     .08       0
  4636.5      .1       0  4796.9     .08       0  4963.7      .1       0
  4999.9     .07       0  5018.4      .1       0  5481.6     .08       0
  5686.8      .1       0  6254.1     .05       0
Bank Sta=4955.24,6143.76
XS Rating Curve= 0 ,0
Exp/Cntr=0.3,0.1

Type RM Length L Ch R = 1 ,10304   ,292,292,292
BEGIN DESCRIPTION:
Mapping XS 865d8ad4
END DESCRIPTION:
XS GIS Cut Line= 3
      2037444.62     13449641.45       2037157.1     13448438.15
      2036873.24     13447552.71
#Sta/Elev= 30
  4206.6  401.29  4280.1  398.43  4303.3  398.42  4382.3  397.55  4586.6  394.69
  4677.6  394.13  4688.8  394.25  4893.2  392.39 4949.52388.7639  4985.4  382.61
  4987.9  381.81  5003.9  382.61  5051.9  392.01  5097.5  392.58  5301.9  392.13
  5542.3  391.67 5696.34388.7635    5861  393.07  5887.9  391.07  5893.1  393.45
  5925.3  390.13  5930.5  393.17  5957.4  390.77  5962.6  393.81  5989.5   391.3
  5994.8   394.2  6240.2  394.91  6310.5   394.7  6344.8  394.67  6373.6   394.5
#Mann= 17 ,-1 , 0
  4206.6      .1       0  4280.1     .05       0  4303.3     .08       0
  4382.3      .1       0  4586.6     .05       0  4677.6     .08       0
  4688.8      .1       0  4893.2     .05       0  4985.4     .03       0
  5003.9     .05       0  5051.9     .08       0  5097.5      .1       0
  5301.9     .05       0  5542.3     .08       0  6240.2      .1       0
  6310.5     .05       0  6344.8     .08       0
Bank Sta=4949.52,5696.34
XS Rating Curve= 0 ,0
Exp/Cntr=0.3,0.1

Type RM Length L Ch R = 1 ,10012   ,284,284,284
BEGIN DESCRIPTION:
Mapping XS 27cbd7d7
END DESCRIPTION:
XS GIS Cut Line= 3
      2037657.56     13448940.55      2037278.39     13448451.65
      2037193.55      13448102.2
#Sta/Elev= 30
  4705.8  395.21  4876.2  393.15  4903.3  392.01  4911.5  390.62  4917.8  390.39
  4925.9  388.89  4930.1388.5619  4940.4  388.31  4946.8  387.44  4961.2  387.28
  4967.6  385.71  4975.7     385    4981  380.44  4983.5  379.64    4997  379.64
  4999.5  380.44  5003.9  383.01    5011  385.87 5056.15388.5624  5067.2  389.29
  5154.1  389.83  5174.9  390.18  5195.7  391.27  5288.9  392.38  5475.4  392.35
    5496   391.7  5537.2  391.53  5547.4  391.13  5640.1  391.36  5684.1  390.67
#Mann= 3 ,-1 , 0
  4705.8     .05       0    4981     .03       0  4999.5     .05       0
Bank Sta=4930.1,5056.15
XS Rating Curve= 0 ,0
Exp/Cntr=0.3,0.1

Type RM Length L Ch R = 1 ,9728    ,344,344,344
BEGIN DESCRIPTION:
Mapping XS 762b7d20
END DESCRIPTION:
XS GIS Cut Line= 3
      2037895.45     13448732.26      2037289.17     13448358.93
      2037244.54     13448193.86
#Sta/Elev= 30
  4501.3  394.44  4643.9  393.84  4680.6   393.1  4783.7  392.97  4790.6  392.59
  4811.9  393.28  4824.9  392.76  4885.3  391.57  4891.1  392.23  4900.7  391.87
  4927.8  392.37  4943.2   391.6 4961.95388.0215  4979.9  384.15  4985.8  379.43
  4988.3  378.63  5001.8  378.63  5004.3  379.43  5007.1  383.98 5029.64388.0213
  5037.9  389.49  5053.3  390.21  5056.3  389.86  5074.6  389.23  5101.7  389.48
  5124.2  390.96  5147.7  391.73  5205.9  392.28  5258.8   392.4  5384.3  391.17
#Mann= 5 ,-1 , 0
  4501.3     .05       0  4824.9      .1       0  4985.8     .07       0
  5004.3      .1       0  5056.3     .05       0
Bank Sta=4961.95,5029.64
XS Rating Curve= 0 ,0
Exp/Cntr=0.3,0.1

Type RM Length L Ch R = 1 ,9384    ,364,364,364
BEGIN DESCRIPTION:
Liveoak Creek 7.0
END DESCRIPTION:
XS GIS Cut Line= 3
       2038053.4     13448777.36        2037575.       13448175.
      2037223.56     13447902.39
#Sta/Elev= 30
  4213.2  394.13  4363.2  393.81    4384  394.25  4698.1  392.43  4726.9  392.17
  4801.1  388.92  4840.7  387.51  4875.9  387.48 4892.21386.7924  4911.1  386.12
    4940  386.22  4954.4  385.28  4960.8  382.99  4968.8  384.15    4970  377.91
  4972.5  377.11    4986  377.11  4988.5  377.91    4996   379.2  5004.1  384.21
  5018.6  385.45    5033   385.3  5039.4  385.91  5045.8  385.46  5053.9  386.25
  5077.8   385.7 5176.13386.7925  5267.6  390.33  5296.5  390.79  5427.2   390.7
#Mann= 5 ,-1 , 0
  4213.2     .05       0  4801.1      .1       0    4970     .07       0
  4988.5      .1       0  5077.8     .05       0
Bank Sta=4892.21,5176.13
XS Rating Curve= 0 ,0
Exp/Cntr=0.3,0.1

Type RM Length L Ch R = 1 ,9020    ,130,130,130
BEGIN DESCRIPTION:
Mapping XS 40cc6240
END DESCRIPTION:
XS GIS Cut Line= 3
      2038271.01      13448706.8      2038027.93     13448227.17
      2037615.61     13447786.63
#Sta/Elev= 30
  4042.1  393.62  4167.4  392.35  4197.3  389.93  4219.6  390.14  4264.1  388.23
  4314.3  389.62  4391.7  389.48  4509.1  391.61    4633  389.13  4724.9  389.73
  4839.7   387.6  4906.3386.0045  4923.2  385.37    4930   383.5  4937.3  385.23
  4944.2  379.66  4951.5  381.67  4958.4  377.11  4965.7  378.84  4972.5  377.33
  4979.8  378.63  5005.8  376.89  5008.3  376.09  5024.3  376.89  5029.2  383.43
    5036   385.6 5042.28386.0043  5071.7  389.66    5132  389.62  5183.2  389.78
#Mann= 5 ,-1 , 0
  4042.1     .05       0  4839.7      .1       0  5005.8     .07       0
  5024.3      .1       0    5132     .05       0
Bank Sta=4906.3,5042.28
XS Rating Curve= 0 ,0
Exp/Cntr=0.3,0.1

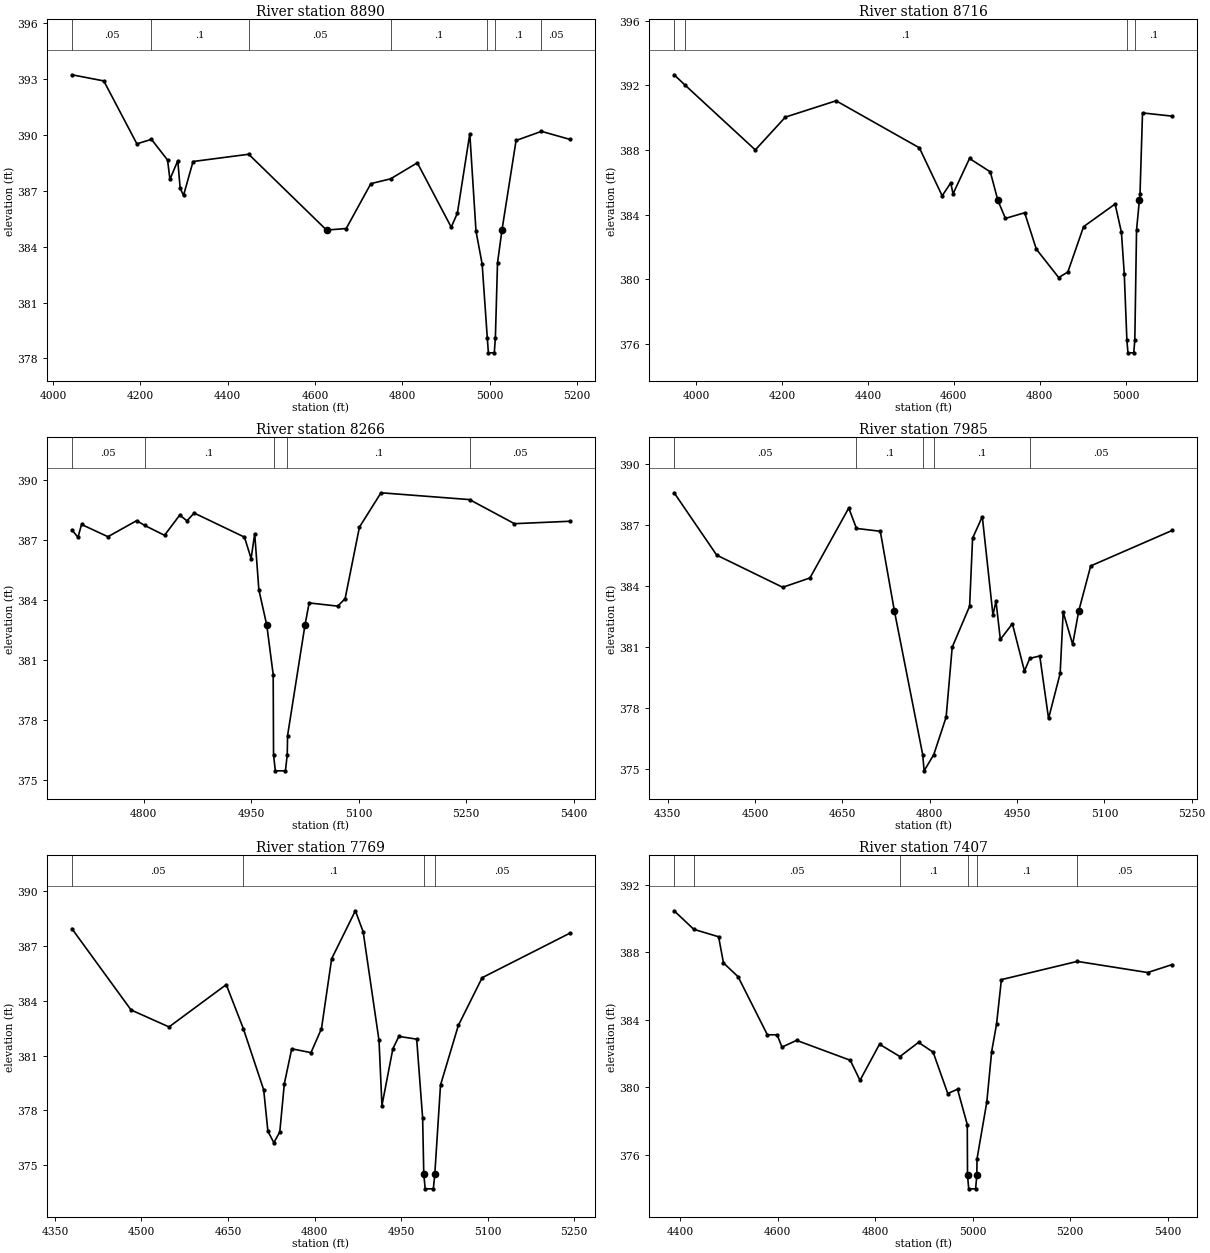
Type RM Length L Ch R = 1 ,8890    ,174,174,174
BEGIN DESCRIPTION:
Mapping XS caad6642
END DESCRIPTION:
XS GIS Cut Line= 3
      2038298.12      13448639.5      2038049.64     13448068.75
      2037696.37     13447689.48
#Sta/Elev= 30
  4042.8  393.24  4115.9  392.91  4191.7  389.53  4225.1  389.77    4262  388.66
  4267.4  387.62  4285.4  388.62  4290.9  387.14  4298.6  386.76  4320.4  388.58
  4447.9  388.97 4626.21384.8962  4671.3  384.98  4727.7  387.39    4773  387.65
  4834.2  388.51  4911.9  385.05    4926  385.81  4954.4  390.07  4968.6  384.84
  4982.7  383.07  4994.5   379.1    4997   378.3  5010.5   378.3    5013   379.1
  5017.9  383.13 5028.11384.8968  5060.4  389.71  5118.6   390.2  5183.6  389.77
#Mann= 7 ,-1 , 0
  4042.8     .05       0  4225.1      .1       0  4447.9     .05       0
    4773      .1       0  4994.5     .07       0    5013      .1       0
  5118.6     .05       0
Bank Sta=4626.21,5028.11
XS Rating Curve= 0 ,0
Exp/Cntr=0.3,0.1

Type RM Length L Ch R = 1 ,8716    ,450,450,450
BEGIN DESCRIPTION:
Mapping XS 26ac9c56
END DESCRIPTION:
XS GIS Cut Line= 3
      2038477.15     13448583.05       2038234.1     13447899.48
      2037864.49     13447671.98
#Sta/Elev= 30
  3948.7  392.66  3974.2  392.02  4137.7  388.01  4207.7  390.04  4325.8  391.05
  4519.7  388.14  4572.8  385.17  4592.8  385.97  4598.1  385.29  4636.5  387.48
  4684.9  386.65 4702.52384.8851  4720.1  383.77  4764.9  384.12    4792  381.87
  4844.1  380.11  4865.4  380.45  4902.1  383.26  4975.5  384.66  4990.2  382.91
  4996.8  380.34  5002.9  376.25  5005.4  375.45  5018.9  375.45  5021.4  376.25
  5025.4  383.05 5031.98384.8859  5033.5  385.31  5039.3   390.3  5108.2   390.1
#Mann= 4 ,-1 , 0
  3948.7     .05       0  3974.2      .1       0  5002.9     .07       0
  5021.4      .1       0
Bank Sta=4702.52,5031.98
XS Rating Curve= 0 ,0
Exp/Cntr=0.3,0.1

Type RM Length L Ch R = 1 ,8266    ,281,281,281
BEGIN DESCRIPTION:
Mapping XS 5877b06f
END DESCRIPTION:
XS GIS Cut Line= 2
      2038495.08     13447509.02      2037802.35     13447566.32
#Sta/Elev= 30
  4699.6  387.49  4708.1  387.12  4713.1  387.76  4749.9  387.15    4790  387.95
  4801.4  387.71  4828.9  387.22  4850.2  388.23  4860.2  387.94  4870.3  388.33
  4940.5  387.13  4949.8  386.06  4954.8   387.3  4960.6  384.51 4971.68 382.733
  4980.6  380.28  4981.1  376.28  4983.6  375.48  4997.7  375.48  5000.2  376.28
  5000.7  377.24 5024.93382.7348  5030.8  383.85  5070.7  383.69    5081  384.06
    5101  387.63  5131.1  389.34  5254.7     389  5317.4   387.8  5394.7  387.92
#Mann= 5 ,-1 , 0
  4699.6     .05       0  4801.4      .1       0  4981.1     .07       0
  5000.2      .1       0  5254.7     .05       0
Bank Sta=4971.68,5024.93
XS Rating Curve= 0 ,0
Exp/Cntr=0.3,0.1

Type RM Length L Ch R = 1 ,7985    ,216,216,216
BEGIN DESCRIPTION:
Mapping XS 14cffe87
END DESCRIPTION:
XS GIS Cut Line= 3
      2038614.79     13447422.22      2038172.12      13447344.1
      2037779.92     13447448.22
#Sta/Elev= 30
    4361  388.57  4434.1  385.51  4547.5  383.93  4594.3  384.39  4660.9  387.82
  4674.2  386.82  4715.1  386.68 4739.19382.7863  4787.9  375.72  4790.4  374.92
    4807  375.72  4828.2  377.56  4838.6  380.99  4868.5     383  4873.6  386.34
  4890.3   387.4  4908.6  382.57  4913.8  383.25  4921.3  381.37    4942  382.14
  4962.7  379.82  4971.9  380.44    4989  380.56  5004.1  377.49    5024   379.7
  5029.2  382.71  5045.5  381.13 5056.09382.7863  5076.5  384.98  5216.3  386.72
#Mann= 5 ,-1 , 0
    4361     .05       0  4674.2      .1       0  4787.9     .03       0
    4807      .1       0  4971.9     .05       0
Bank Sta=4739.19,5056.09
XS Rating Curve= 0 ,0
Exp/Cntr=0.3,0.1

Type RM Length L Ch R = 1 ,7769    ,362,362,362
BEGIN DESCRIPTION:
Mapping XS d850e63f
END DESCRIPTION:
XS GIS Cut Line= 2
      2038604.43     13447351.05      2037767.62     13447139.24
#Sta/Elev= 30
  4379.4  387.96    4482   383.5  4547.8  382.57    4647  384.89  4676.6  382.48
  4711.9  379.12  4719.2  376.85  4729.5  376.22  4739.8  376.81  4747.7  379.46
  4760.5  381.37  4793.9  381.16  4812.1  382.48  4829.7  386.31  4870.8  388.94
  4884.3  387.79  4911.8  381.83  4916.9  378.26  4935.8  381.37  4946.2  382.05
  4977.1   381.9  4987.4  377.59  4989.4  374.49  4991.9  373.69    5006  373.69
  5008.5  374.49  5018.4  379.38  5049.3  382.65  5090.6  385.27  5242.6  387.71
#Mann= 4 ,-1 , 0
  4379.4     .05       0  4676.6      .1       0  4989.4     .07       0
  5008.5     .05       0
Bank Sta=4989.4,5008.5
XS Rating Curve= 0 ,0
Exp/Cntr=0.3,0.1

Type RM Length L Ch R = 1 ,7407    ,250,250,250
BEGIN DESCRIPTION:
Mapping XS 12ab573b
END DESCRIPTION:
XS GIS Cut Line= 2
      2038806.22     13447036.58      2037784.92     13447038.54
#Sta/Elev= 30
  4387.8  390.47  4428.1  389.37    4479  388.93    4489  387.38    4519  386.56
    4579  383.12    4599  383.12    4609  382.39    4639  382.79    4749  381.61
    4769  380.42    4809  382.56  4850.9  381.83    4889  382.67    4919  382.09
    4949  379.64    4969  379.89    4989   377.8  4989.5  374.79    4992  373.99
  5006.1  373.99  5008.6  374.79    5009  375.77    5029  379.12    5039  382.12
    5049  383.74    5059  386.39  5214.6  387.47    5359  386.81  5409.1  387.28
#Mann= 6 ,-1 , 0
  4387.8      .1       0  4428.1     .05       0  4850.9      .1       0
  4989.5     .07       0  5008.6      .1       0  5214.6     .05       0
Bank Sta=4989.5,5008.6
XS Rating Curve= 0 ,0
Exp/Cntr=0.3,0.1