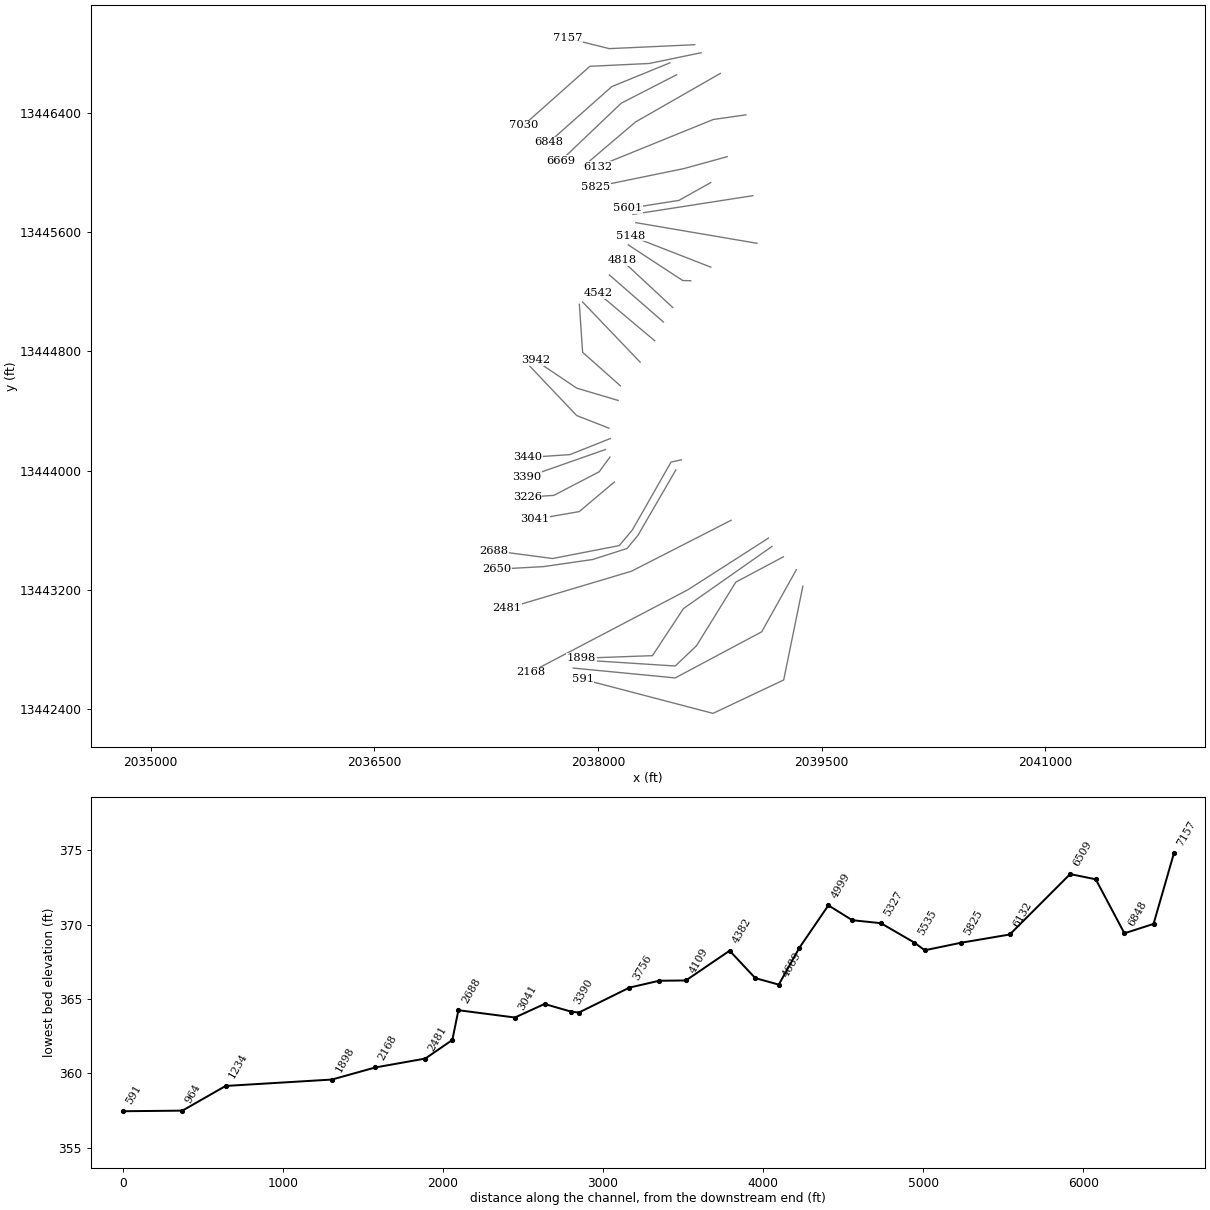
HEC-RAS study Liveoak Creek.prj: Liveoak Creek Base Level Engineering

--- Liveoak Creek.g01 (geometry) --- (continued)

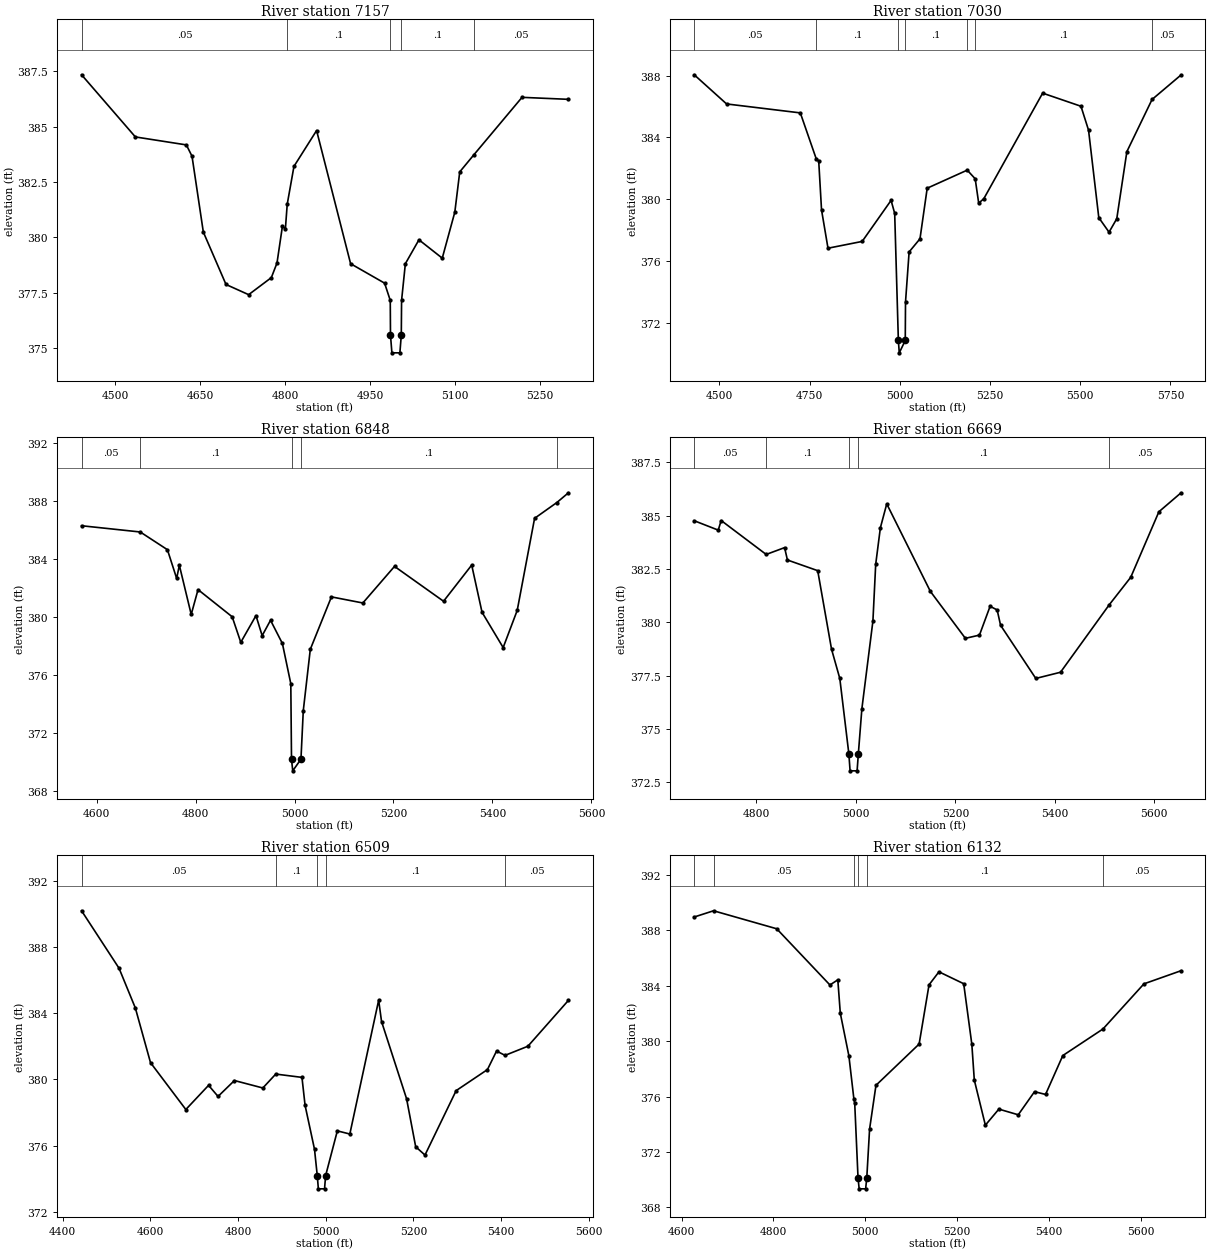
Type RM Length L Ch R = 1 ,7157    ,127,127,127
BEGIN DESCRIPTION:
Mapping XS 8f80ee66
END DESCRIPTION:
XS GIS Cut Line= 3
      2038650.01     13446856.46      2038076.63     13446830.21
      2037798.57     13446899.29
#Sta/Elev= 30
  4440.2  387.35  4535.3  384.54  4625.4  384.18  4635.4  383.67  4655.4  380.24
  4695.5  377.87  4735.5  377.41  4775.6  378.18  4785.6  378.84  4795.3  380.52
  4800.4  380.37  4803.7   381.5  4815.6  383.21  4855.6  384.83  4915.7  378.81
  4975.8  377.93  4985.8  377.15  4986.2  375.58  4988.7  374.78  5002.8  374.78
  5005.3  375.58  5005.8  377.15  5012.5  378.81  5036.5  379.89  5077.7  379.06
  5099.9  381.14  5108.6  382.96  5133.8  383.74  5218.7  386.33  5300.7  386.24
#Mann= 5 ,-1 , 0
  4440.2     .05       0  4803.7      .1       0  4986.2     .07       0
  5005.3      .1       0  5133.8     .05       0
Bank Sta=4986.2,5005.3
XS Rating Curve= 0 ,0
Exp/Cntr=0.3,0.1

Type RM Length L Ch R = 1 ,7030    ,182,182,182
BEGIN DESCRIPTION:
Mapping XS a841e416
END DESCRIPTION:
XS GIS Cut Line= 4
      2038692.88     13446802.79      2038344.83     13446730.75
      2037946.39     13446711.65      2037501.84     13446316.51
#Sta/Elev= 30
  4430.3  388.06    4520  386.17  4724.3  385.59  4768.6   382.6  4775.3  382.47
  4783.1   379.3    4801  376.82  4895.7  377.26  4975.8  379.92  4985.8  379.08
    4996  370.84  4998.5  370.04  5015.1  370.84  5015.8  373.33  5025.8  376.58
  5055.9  377.43  5075.9  380.71  5186.8  381.88  5208.9  381.32  5218.6  379.74
  5232.8  380.03  5395.8  386.87    5502  386.02    5523  384.47  5551.4   378.8
  5579.8  377.86  5601.2  378.73  5629.2  383.08    5699  386.46  5779.4  388.05
#Mann= 7 ,-1 , 0
  4430.3     .05       0  4768.6      .1       0    4996     .07       0
  5015.1      .1       0  5186.8     .05       0  5208.9      .1       0
    5699     .05       0
Bank Sta=4996,5015.1
XS Rating Curve= 0 ,0
Exp/Cntr=0.3,0.1

Type RM Length L Ch R = 1 ,6848    ,179,179,179
BEGIN DESCRIPTION:
Mapping XS 4c61c17c
END DESCRIPTION:
XS GIS Cut Line= 3
      2038482.91     13446734.73      2038093.67     13446575.66
      2037671.95      13446201.9
#Sta/Elev= 30
  4569.6  386.29  4688.2  385.86  4743.1  384.64  4761.8  382.66  4767.2  383.57
  4791.2  380.18    4805  381.89    4874  380.02  4891.4  378.26  4922.1   380.1
  4934.6  378.72  4951.5  379.78  4975.5  378.18  4992.5  375.41  4993.9  370.21
  4996.4  369.41    5013  370.21  5017.7  373.55  5031.9  377.78  5074.6  381.39
  5138.1  380.97  5202.1  383.49  5301.2  381.09  5358.1  383.58    5379  380.33
  5421.7   377.9  5450.1  380.46  5485.2   386.8  5530.3  387.89  5553.6  388.56
#Mann= 5 ,-1 , 0
  4569.6     .05       0  4688.2      .1       0  4993.9     .07       0
    5013      .1       0  5530.3     .05       0
Bank Sta=4993.9,5013
XS Rating Curve= 0 ,0
Exp/Cntr=0.3,0.1

Type RM Length L Ch R = 1 ,6669    ,160,160,160
BEGIN DESCRIPTION:
Mapping XS c345f4d7
END DESCRIPTION:
XS GIS Cut Line= 3
      2038528.01     13446654.86      2038157.02     13446464.48
      2037750.13     13446076.94
#Sta/Elev= 30
    4675  384.76  4723.3  384.32  4729.2  384.77  4819.7  383.18  4856.7   383.5
  4862.4  382.92  4923.3  382.42  4951.1  378.74  4967.7  377.37  4985.9  373.84
  4988.4  373.04  5002.5  373.04    5005  373.84  5012.1  375.95  5034.3  380.06
  5039.9  382.72  5049.3  384.43  5062.1  385.55  5149.8  381.45  5220.2  379.25
  5248.5   379.4  5269.9  380.75  5284.1  380.58    5291  379.86  5361.8  377.37
  5411.5  377.66  5509.4  380.82  5552.7  382.11  5609.3  385.18  5653.9  386.07
#Mann= 5 ,-1 , 0
    4675     .05       0  4819.7      .1       0  4985.9     .07       0
    5005      .1       0  5509.4     .05       0
Bank Sta=4985.9,5005
XS Rating Curve= 0 ,0
Exp/Cntr=0.3,0.1

Type RM Length L Ch R = 1 ,6509    ,377,377,377
BEGIN DESCRIPTION:
Mapping XS 70ea4324
END DESCRIPTION:
XS GIS Cut Line= 3
      2038821.47       13446664.      2038252.85     13446338.45
      2037905.64     13446043.33
#Sta/Elev= 30
    4443  390.18  4528.5  386.71  4565.7  384.31  4600.3  381.01  4680.9  378.18
  4732.8  379.64  4754.4  378.97  4791.8  379.93  4856.6  379.48  4886.1  380.32
  4945.9  380.12    4953  378.43  4974.5  375.78  4980.8  374.19  4983.3  373.39
  4997.4  373.39  4999.9  374.19  5026.6  376.89  5055.1   376.7  5120.9  384.78
  5127.5  383.49  5184.6  378.83  5205.4  375.93  5226.6  375.43  5297.7  379.32
  5369.1  380.59  5389.9  381.71  5409.3  381.45  5461.4     382  5553.9  384.77
#Mann= 5 ,-1 , 0
    4443     .05       0  4886.1      .1       0  4980.8     .07       0
  4999.9      .1       0  5409.3     .05       0
Bank Sta=4980.8,4999.9
XS Rating Curve= 0 ,0
Exp/Cntr=0.3,0.1

Type RM Length L Ch R = 1 ,6132    ,307,307,307
BEGIN DESCRIPTION:
Liveoak Creek 6.0
END DESCRIPTION:
XS GIS Cut Line= 3
      2038992.91      13446386.2      2038774.12     13446354.95
      2037996.36     13446038.99
#Sta/Elev= 30
  4627.6  388.97  4669.7  389.42  4807.3  388.12  4923.2  384.06  4940.4  384.43
  4945.8  382.02  4964.5  378.94  4975.3  375.85  4977.2  375.52  4984.4  370.13
  4986.9  369.33    5001  369.33  5003.5  370.13  5009.6  373.65  5023.5  376.81
  5117.5  379.79  5139.1  384.07  5160.7  385.01  5214.6  384.15  5232.3  379.78
  5237.7  377.19  5261.8  373.93  5291.2  375.09  5333.4  374.68  5368.9  376.35
  5392.9  376.15  5430.5  378.96    5518  380.88  5607.2  384.14  5688.1  385.09
#Mann= 6 ,-1 , 0
  4627.6      .1       0  4669.7     .05       0  4975.3      .1       0
  4984.4     .07       0  5003.5      .1       0    5518     .05       0
Bank Sta=4984.4,5003.5
XS Rating Curve= 0 ,0
Exp/Cntr=0.3,0.1

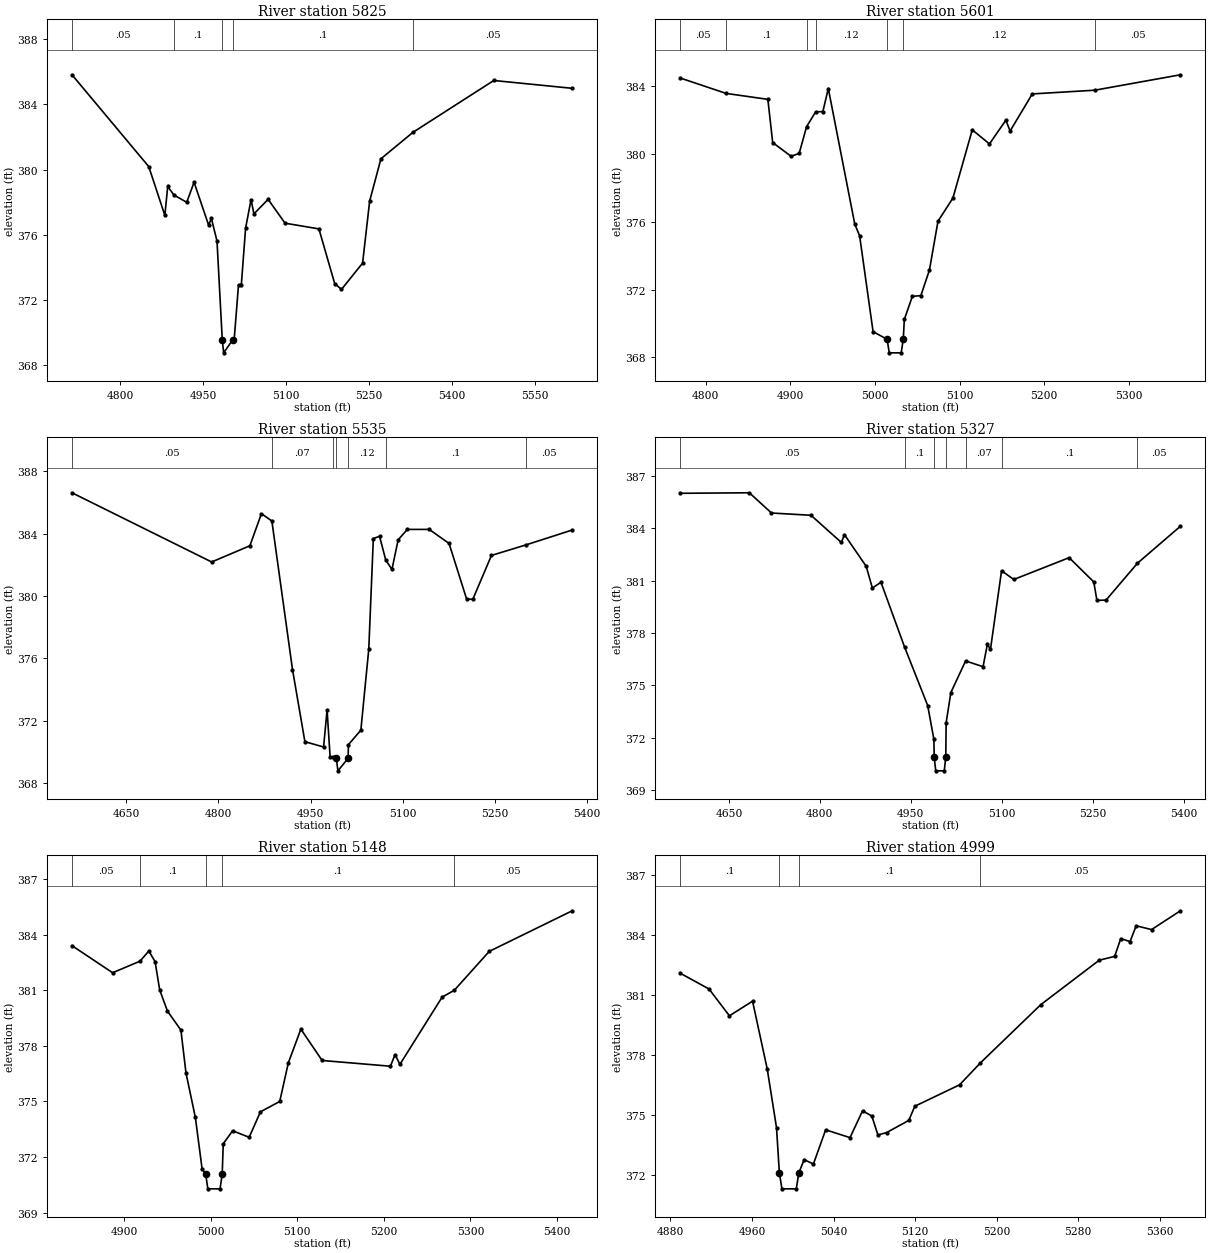
Type RM Length L Ch R = 1 ,5825    ,224,224,224
BEGIN DESCRIPTION:
Liveoak Creek 5.0
END DESCRIPTION:
XS GIS Cut Line= 3
       2038867.9     13446105.83        2038575.       13446025.
      2037985.96     13445904.44
#Sta/Elev= 30
  4712.5  385.82  4851.4  380.19  4880.5   377.2  4885.7  378.97  4896.9  378.45
  4920.1     378  4933.4  379.23  4959.6  376.61  4964.8  377.01  4974.9  375.62
  4984.4  369.57  4986.9  368.77  5003.5  369.57    5006   369.6  5013.8  372.94
  5018.9  372.94  5026.6  376.41  5036.5  378.17  5041.6  377.29  5067.4  378.18
    5098  376.72  5159.3  376.37  5187.8  373.02  5200.1  372.66  5238.3  374.27
  5251.1  378.08  5271.5  380.67  5329.4  382.29  5475.7  385.47  5617.6  384.99
#Mann= 5 ,-1 , 0
  4712.5     .05       0  4896.9      .1       0  4984.4     .07       0
  5003.5      .1       0  5329.4     .05       0
Bank Sta=4984.4,5003.5
XS Rating Curve= 0 ,0
Exp/Cntr=0.3,0.1

Type RM Length L Ch R = 1 ,5601    ,66,66,66
BEGIN DESCRIPTION:
Mapping XS 39326131
END DESCRIPTION:
XS GIS Cut Line= 3
       2038757.6     13445932.19      2038544.08     13445812.41
      2038202.11      13445758.6
#Sta/Elev= 30
  4769.9  384.49  4824.2  383.58  4873.5  383.23  4879.2  380.68  4900.9  379.87
  4910.5  380.04  4919.2  381.61  4929.9  382.49  4938.5  382.51  4944.9  383.87
  4976.2  375.86  4981.9  375.18  4997.8  369.52  5014.4  369.07  5016.9  368.27
    5031  368.27  5033.5  369.07  5034.7  370.24  5044.2   371.6  5054.3  371.65
  5064.4  373.16  5074.5  376.04  5092.1   377.4    5115  381.43  5135.3   380.6
  5154.7     382  5159.7  381.36  5185.9  383.55  5259.8  383.77  5360.9  384.68
#Mann= 7 ,-1 , 0
  4769.9     .05       0  4824.2      .1       0  4919.2     .07       0
  4929.9     .12       0  5014.4     .07       0  5033.5     .12       0
  5259.8     .05       0
Bank Sta=5014.4,5033.5
XS Rating Curve= 0 ,0
Exp/Cntr=0.3,0.1

Type RM Length L Ch R = 1 ,5535    ,208,208,208
BEGIN DESCRIPTION:
Mapping XS 4851de38
END DESCRIPTION:
XS GIS Cut Line= 2
      2039039.72     13445844.01      2038235.02     13445718.66
#Sta/Elev= 30
  4561.6  386.63    4789  382.19  4851.2  383.23    4870  385.29    4887  384.82
  4920.6  375.29  4940.8  370.66  4971.2  370.32  4976.9  372.69  4981.9  369.65
    4986  369.65    4992  369.59  4994.5  368.79  5011.1  369.59  5011.7  370.47
  5031.9   371.4  5044.8  376.61  5052.2  383.69  5062.3  383.84  5072.4  382.32
  5082.5  381.71  5092.6  383.61  5107.6  384.28  5143.2  384.28  5175.5  383.38
    5204  379.82  5214.1  379.79  5244.5  382.61  5300.2  383.28    5376  384.24
#Mann= 7 ,-1 , 0
  4561.6     .05       0    4887     .07       0    4986     .12       0
    4992     .07       0  5011.1     .12       0  5072.4      .1       0
  5300.2     .05       0
Bank Sta=4992,5011.1
XS Rating Curve= 0 ,0
Exp/Cntr=0.3,0.1

Type RM Length L Ch R = 1 ,5327    ,179,179,179
BEGIN DESCRIPTION:
Mapping XS ab68c716
END DESCRIPTION:
XS GIS Cut Line= 2
      2039067.51     13445524.56      2038254.13     13445663.11
#Sta/Elev= 30
  4569.6     386  4683.7  386.03  4720.2  384.87  4785.4  384.74  4835.5  383.18
  4840.6  383.63  4876.5  381.81  4886.6  380.57  4900.8   380.9  4939.7  377.19
  4977.9  373.83  4988.1  371.89  4988.6  370.89  4991.1  370.09  5005.2  370.09
  5007.7  370.89  5008.3  372.85  5016.1  374.58  5040.4  376.39  5069.2  376.06
  5076.3  377.35  5081.4  377.05  5099.7  381.56  5119.9  381.06  5211.2  382.31
  5251.8  380.92    5257  379.86  5272.1  379.88  5323.8  381.99  5394.7  384.11
#Mann= 7 ,-1 , 0
  4569.6     .05       0  4939.7      .1       0  4988.6     .07       0
  5007.7      .1       0  5040.4     .07       0  5099.7      .1       0
  5323.8     .05       0
Bank Sta=4988.6,5007.7
XS Rating Curve= 0 ,0
Exp/Cntr=0.3,0.1

Type RM Length L Ch R = 1 ,5148    ,149,149,149
BEGIN DESCRIPTION:
Mapping XS aaa22acb
END DESCRIPTION:
XS GIS Cut Line= 2
      2038757.63      13445364.5      2038219.75     13445574.44
#Sta/Elev= 30
  4840.1   383.4    4887  381.94  4918.5  382.56  4928.8  383.11    4936  382.54
  4941.3  381.02  4950.3  379.87  4965.8  378.85  4971.7  376.53  4982.5  374.14
  4990.3  371.36  4994.4  371.09  4996.9  370.29    5011  370.29  5013.5  371.09
  5014.7  372.72  5025.5  373.42  5044.6  373.07  5057.6  374.44  5079.9     375
  5089.8  377.08  5104.3   378.9  5128.8  377.21  5207.7   376.9    5213  377.53
  5218.6     377  5267.4  380.63  5281.3  380.99  5321.7  383.09  5417.5  385.28
#Mann= 5 ,-1 , 0
  4840.1     .05       0  4918.5      .1       0  4994.4     .07       0
  5013.5      .1       0  5281.3     .05       0
Bank Sta=4994.4,5013.5
XS Rating Curve= 0 ,0
Exp/Cntr=0.3,0.1

Type RM Length L Ch R = 1 ,4999    ,181,181,181
BEGIN DESCRIPTION:
Mapping XS 370fb679
END DESCRIPTION:
XS GIS Cut Line= 3
      2038623.29     13445273.39      2038568.75     13445275.07
      2038203.78     13445513.82
#Sta/Elev= 30
  4889.5  382.07  4917.8  381.28  4937.8  379.94  4960.5  380.67  4974.9  377.28
    4984  374.35  4986.8  372.09  4989.3  371.29  5003.4  371.29  5005.9  372.09
  5011.1  372.75  5020.2  372.53  5032.2  374.24  5056.1  373.85  5068.4  375.19
  5077.5  374.93  5083.5  373.98  5091.9   374.1  5113.7  374.71  5119.7  375.42
  5163.6  376.49  5184.1  377.59  5243.3   380.5  5300.6  382.72  5315.7  382.91
  5321.7   383.8  5330.8  383.65  5336.8  384.44  5351.9  384.25  5380.2  385.19
#Mann= 4 ,-1 , 0
  4889.5      .1       0  4986.8     .07       0  5005.9      .1       0
  5184.1     .05       0
Bank Sta=4986.8,5005.9
XS Rating Curve= 0 ,0
Exp/Cntr=0.3,0.1

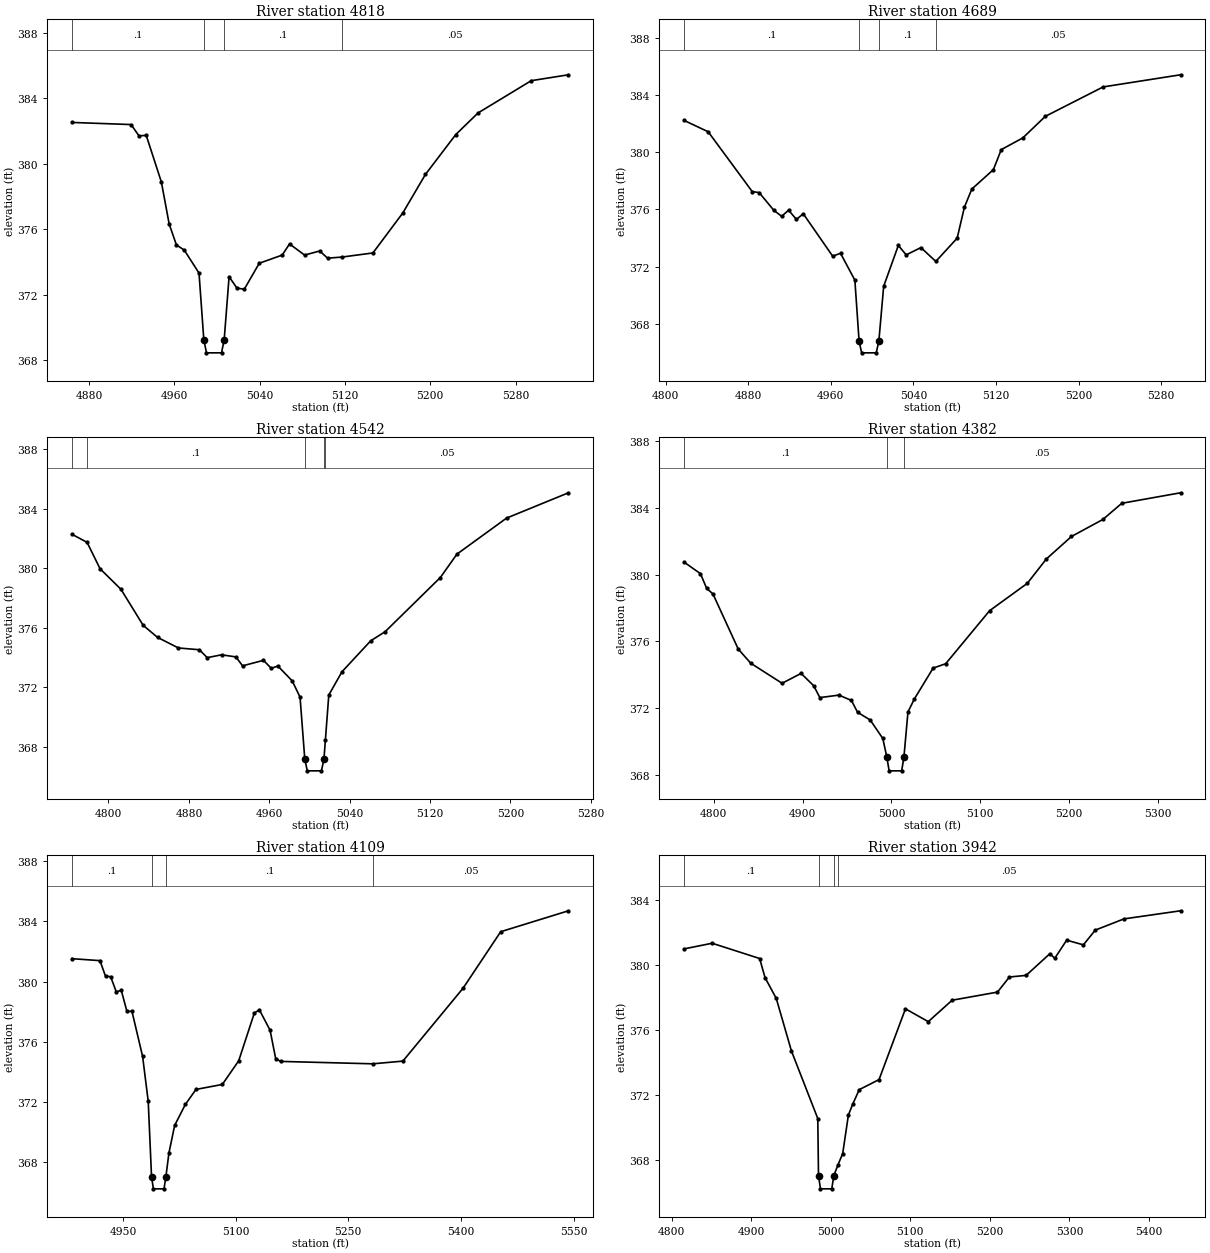
Type RM Length L Ch R = 1 ,4818    ,129,129,129
BEGIN DESCRIPTION:
Mapping XS d0ef983c
END DESCRIPTION:
XS GIS Cut Line= 2
      2038502.41     13445093.67      2038161.14     13445410.69
#Sta/Elev= 30
  4863.8  382.51  4919.4  382.38  4926.8  381.69  4933.6  381.72  4947.8  378.87
  4955.1  376.31  4961.9  375.03  4969.3  374.71  4983.1  373.31  4987.6  369.24
  4990.1  368.44  5004.2  368.44  5006.7  369.24  5011.3  373.09  5018.6   372.4
  5025.5  372.32  5039.6  373.91  5061.1  374.41    5068  375.09  5082.1  374.41
  5096.3  374.66  5103.7  374.22  5117.3  374.29  5146.2  374.54  5174.2  376.98
  5195.5  379.34  5223.9  381.77  5244.8  383.09  5294.7  385.06  5329.6  385.42
#Mann= 4 ,-1 , 0
  4863.8      .1       0  4987.6     .07       0  5006.7      .1       0
  5117.3     .05       0
Bank Sta=4987.6,5006.7
XS Rating Curve= 0 ,0
Exp/Cntr=0.3,0.1

Type RM Length L Ch R = 1 ,4689    ,147,147,147
BEGIN DESCRIPTION:
Mapping XS aa1d7f47
END DESCRIPTION:
XS GIS Cut Line= 2
      2038439.91     13444996.45      2038077.09     13445312.39
#Sta/Elev= 30
  4817.7  382.24  4841.2  381.44  4883.9  377.25  4890.6  377.18  4904.8  375.94
  4912.4  375.52  4919.1  375.95  4926.7   375.3  4933.3   375.7  4961.8  372.73
  4969.4  372.93  4983.3  371.05  4987.4  366.76  4989.9  365.96    5004  365.96
  5006.5  366.76  5011.2  370.62  5025.4  373.48    5033  372.82  5047.3  373.33
  5061.7  372.36  5082.4  373.99  5089.4  376.16  5096.6  377.43  5117.5  378.79
  5125.1  380.19    5146  381.01  5167.8  382.52  5223.8  384.58  5298.8  385.43
#Mann= 4 ,-1 , 0
  4817.7      .1       0  4987.4     .07       0  5006.5      .1       0
  5061.7     .05       0
Bank Sta=4987.4,5006.5
XS Rating Curve= 0 ,0
Exp/Cntr=0.3,0.1

Type RM Length L Ch R = 1 ,4542    ,160,160,160
BEGIN DESCRIPTION:
Mapping XS d01d99af
END DESCRIPTION:
XS GIS Cut Line= 2
      2038380.89     13444871.44      2038002.38     13445189.18
#Sta/Elev= 30
  4763.5  382.29  4778.7  381.74  4791.6  379.97  4812.4  378.59  4834.5  376.17
  4848.8  375.36  4869.6  374.65  4890.5  374.53  4898.2     374  4912.5  374.19
  4926.8  374.05  4933.4  373.45  4954.2  373.82    4962  373.28  4968.5  373.44
  4982.8  372.44  4990.6  371.35  4995.3   367.2  4997.8   366.4  5011.9   366.4
  5014.4   367.2  5015.8  368.45  5019.2  371.49  5032.3  373.05  5060.9  375.13
  5075.2  375.74  5130.2  379.38  5146.7  380.95  5196.1  383.37  5257.7  385.07
#Mann= 5 ,-1 , 0
  4763.5     .05       0  4778.7      .1       0  4995.3     .07       0
  5014.4      .1       0  5015.8     .05       0
Bank Sta=4995.3,5014.4
XS Rating Curve= 0 ,0
Exp/Cntr=0.3,0.1

Type RM Length L Ch R = 1 ,4382    ,273,273,273
BEGIN DESCRIPTION:
Mapping XS 2c35f40d
END DESCRIPTION:
XS GIS Cut Line= 2
      2038283.63     13444727.37       2037897.4     13445130.93
#Sta/Elev= 30
  4766.6  380.76  4785.2  380.06  4792.1  379.19  4799.3  378.84  4827.7  375.54
  4841.8  374.69    4877  373.49  4898.4  374.08  4912.6  373.34  4919.5  372.63
  4940.9  372.78    4955  372.46  4961.9  371.75  4976.1  371.29  4990.3  370.18
  4994.9  369.04  4997.4  368.24  5011.5  368.24    5014  369.04  5018.6  371.77
  5025.8  372.55  5046.9   374.4    5061  374.66  5110.4  377.84  5152.8  379.48
  5174.2  380.94  5202.5  382.29  5237.8  383.31  5259.1  384.28  5325.2  384.91
#Mann= 3 ,-1 , 0
  4766.6      .1       0  4994.9     .07       0    5014     .05       0
Bank Sta=4994.9,5014
XS Rating Curve= 0 ,0
Exp/Cntr=0.3,0.1

Type RM Length L Ch R = 1 ,4109    ,167,167,167
BEGIN DESCRIPTION:
Mapping XS 496b9483
END DESCRIPTION:
XS GIS Cut Line= 3
      2038151.49     13444568.21       2037897.6     13444793.89
       2037875.9     13445115.07
#Sta/Elev= 30
  4881.7  381.52  4919.2  381.39  4926.7  380.34  4933.4  380.33  4940.9  379.32
  4947.6  379.42  4955.1  378.02  4961.8  378.03    4976  375.03  4983.5  372.04
  4987.9  367.04  4990.4  366.24  5004.5  366.24    5007  367.04  5011.1  368.63
  5018.7  370.45  5032.9  371.84  5047.1  372.84  5082.2  373.17    5104  374.74
  5124.9  377.92  5131.6  378.12  5145.8  376.77  5153.3  374.88    5160   374.7
  5282.7  374.54  5322.7  374.72  5402.9  379.56    5453  383.31  5543.3   384.7
#Mann= 4 ,-1 , 0
  4881.7      .1       0  4987.9     .07       0    5007      .1       0
  5282.7     .05       0
Bank Sta=4987.9,5007
XS Rating Curve= 0 ,0
Exp/Cntr=0.3,0.1

Type RM Length L Ch R = 1 ,3942    ,186,186,186
BEGIN DESCRIPTION:
Mapping XS 58a1a47b
END DESCRIPTION:
XS GIS Cut Line= 3
      2038136.31     13444470.54      2037858.53     13444553.01
      2037580.76     13444739.64
#Sta/Elev= 30
  4815.4     381  4850.9  381.35  4910.6  380.41  4917.4  379.23  4931.5  377.95
  4950.6  374.71  4983.7  370.55  4984.6  367.02  4987.1  366.22  5001.3  366.22
  5003.8  367.02  5009.1   367.7    5015  368.39  5022.2  370.77  5027.5  371.42
  5035.8  372.33  5060.7  372.95  5093.9  377.31  5122.6  376.52  5152.6  377.84
  5209.6  378.34  5224.6  379.27  5245.6  379.37  5275.6  380.71  5281.6  380.42
  5296.6  381.54  5317.6  381.25  5332.6  382.16  5368.6  382.85  5439.8  383.35
#Mann= 4 ,-1 , 0
  4815.4      .1       0  4984.6     .07       0  5003.8      .1       0
  5009.1     .05       0
Bank Sta=4984.6,5003.8
XS Rating Curve= 0 ,0
Exp/Cntr=0.3,0.1

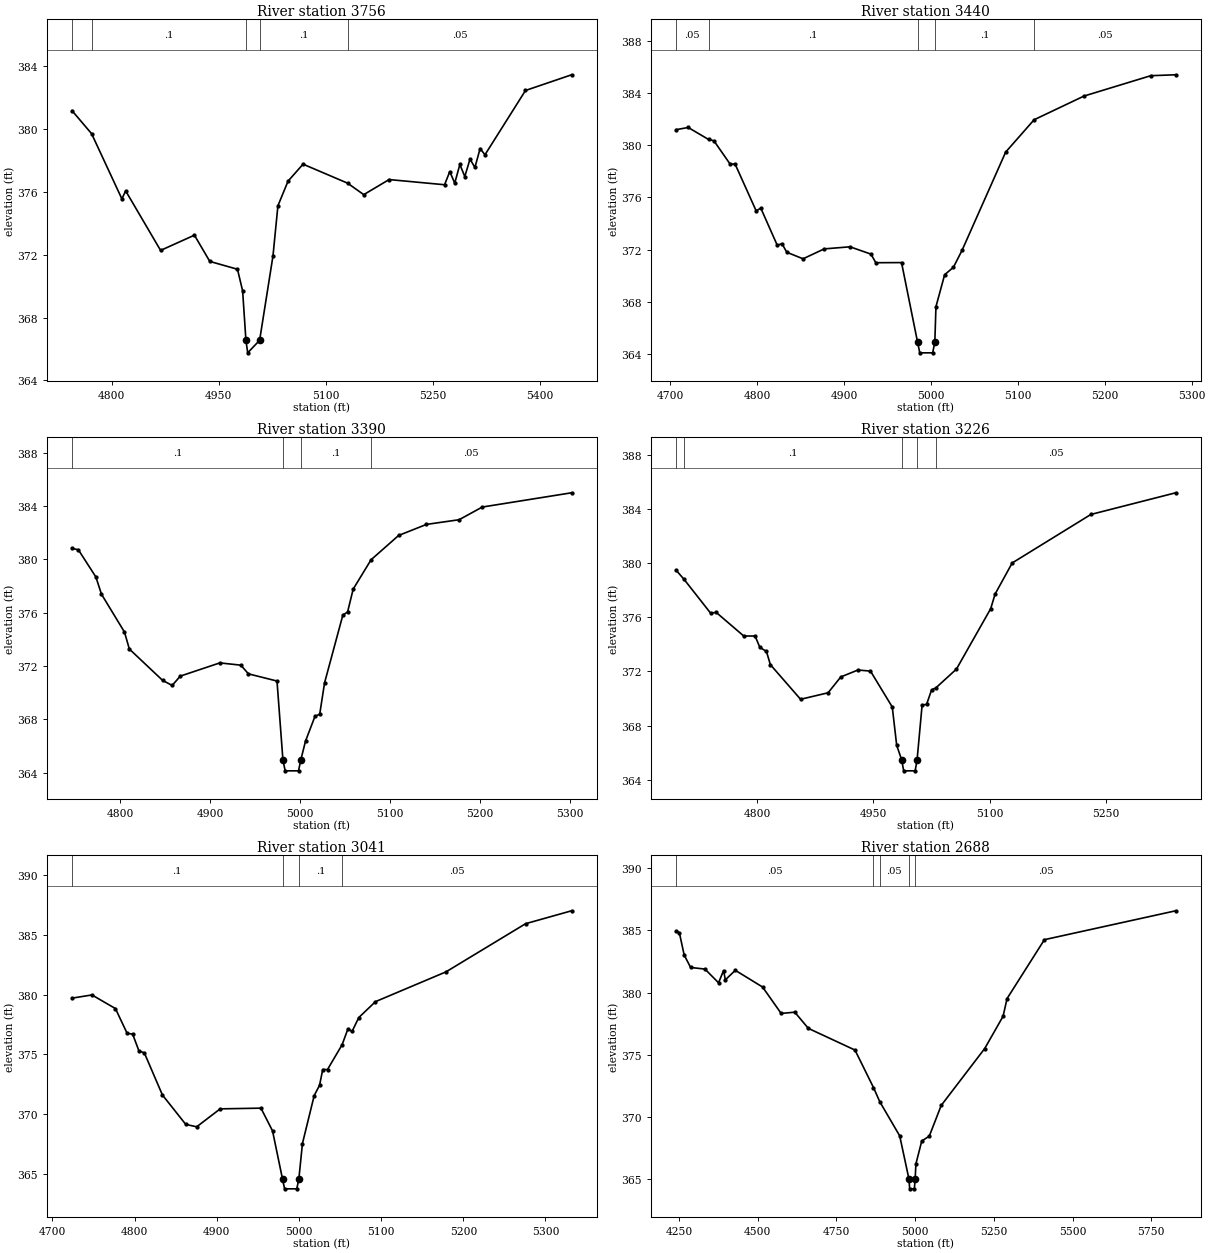
Type RM Length L Ch R = 1 ,3756    ,316,316,316
BEGIN DESCRIPTION:
Mapping XS 870a4154
END DESCRIPTION:
XS GIS Cut Line= 3
      2038074.66     13444284.35      2037857.67     13444369.42
       2037536.5     13444707.94
#Sta/Elev= 30
  4744.3  381.18  4771.8  379.71  4814.2  375.56  4819.5  376.07  4868.4  372.28
  4915.8  373.25  4937.3  371.58  4976.1  371.08  4983.3   369.7  4987.9  366.56
  4990.4  365.76  5007.1  366.56  5025.8  371.93  5032.7  375.12  5046.9  376.69
  5067.9  377.77  5130.3  376.56  5152.9  375.83  5188.4  376.79  5266.1  376.46
  5273.4   377.3  5280.3  376.56  5287.5  377.75  5294.4  376.98  5301.7  378.09
  5308.6  377.56  5315.8  378.76  5322.7  378.37  5379.4  382.46    5444  383.46
#Mann= 5 ,-1 , 0
  4744.3     .05       0  4771.8      .1       0  4987.9     .07       0
  5007.1      .1       0  5130.3     .05       0
Bank Sta=4987.9,5007.1
XS Rating Curve= 0 ,0
Exp/Cntr=0.3,0.1

Type RM Length L Ch R = 1 ,3440    ,50,50,50
BEGIN DESCRIPTION:
Mapping XS c3fc4f2d
END DESCRIPTION:
XS GIS Cut Line= 3
      2038083.39     13444214.91      2037812.53     13444107.26
      2037529.74     13444088.18
#Sta/Elev= 30
  4706.8  381.19  4720.7  381.36  4744.2  380.44  4750.3  380.34  4769.2  378.53
  4774.6  378.57  4798.9  374.97  4804.3  375.17  4823.2  372.33  4828.6  372.45
  4834.2  371.79  4852.9  371.29  4877.2  372.05  4906.9  372.21    4931  371.65
  4936.6  370.99  4966.2     371  4984.7  364.88  4987.2  364.08    5002  364.08
  5004.5  364.88  5005.8  367.62  5015.8  370.07  5025.9  370.64  5035.9  371.95
    5086  379.47  5118.7  381.95  5176.2  383.77    5253  385.33  5281.7   385.4
#Mann= 5 ,-1 , 0
  4706.8     .05       0  4744.2      .1       0  4984.7     .07       0
  5004.5      .1       0  5118.7     .05       0
Bank Sta=4984.7,5004.5
XS Rating Curve= 0 ,0
Exp/Cntr=0.3,0.1

Type RM Length L Ch R = 1 ,3390    ,164,164,164
BEGIN DESCRIPTION:
Mapping XS 45b4ae67
END DESCRIPTION:
XS GIS Cut Line= 2
      2038050.09     13444141.19      2037525.84     13443957.19
#Sta/Elev= 30
  4746.4  380.82  4753.5  380.72    4773  378.68  4779.2  377.39  4804.8  374.55
  4810.2  373.28  4847.2  370.93  4857.8  370.55  4866.9  371.25  4910.8  372.24
  4934.2  372.07  4942.6  371.42  4974.4  370.88    4981  364.95  4983.5  364.15
  4998.3  364.15  5000.8  364.95  5006.1  366.38  5016.6  368.23  5021.9   368.4
  5027.3  370.75  5047.6  375.82  5052.9  376.06  5059.1  377.77    5079  379.97
  5109.6  381.79  5140.6  382.62  5176.9  382.97  5202.6  383.92    5302  384.99
#Mann= 4 ,-1 , 0
  4746.4      .1       0    4981     .07       0  5000.8      .1       0
    5079     .05       0
Bank Sta=4981,5000.8
XS Rating Curve= 0 ,0
Exp/Cntr=0.3,0.1

Type RM Length L Ch R = 1 ,3226    ,185,185,185
BEGIN DESCRIPTION:
Mapping XS ade417b3
END DESCRIPTION:
XS GIS Cut Line= 4
      2038081.36     13444090.85      2038008.45      13443991.9
      2037704.63     13443833.91       2037525.8     13443821.76
#Sta/Elev= 30
  4695.4  379.47  4705.7  378.79  4739.9   376.3  4747.2  376.35  4782.7  374.61
  4797.3  374.61  4803.5  373.77    4812  373.47    4817   372.5    4856  369.94
  4891.5  370.42  4907.9  371.59    4930   372.1  4946.2  372.02  4974.3  369.37
    4980  366.54  4986.5  365.46    4989  364.66  5003.8  364.66  5006.3  365.46
  5012.8  369.52  5018.5  369.56  5025.1  370.64  5030.5  370.78  5057.1  372.17
  5101.3  376.63  5106.9   377.7    5129     380  5230.5  383.58    5340  385.18
#Mann= 5 ,-1 , 0
  4695.4     .05       0  4705.7      .1       0  4986.5     .07       0
  5006.3      .1       0  5030.5     .05       0
Bank Sta=4986.5,5006.3
XS Rating Curve= 0 ,0
Exp/Cntr=0.3,0.1

Type RM Length L Ch R = 1 ,3041    ,353,353,353
BEGIN DESCRIPTION:
Liveoak Creek 4.0
END DESCRIPTION:
XS GIS Cut Line= 3
       2038110.9     13443923.77        2037875.       13443725.
      2037579.78     13443673.78
#Sta/Elev= 30
  4723.7   379.7    4748  379.97  4776.6  378.83  4790.9  376.75  4797.5   376.7
  4805.2  375.29  4811.8  375.12  4833.8   371.6  4862.2  369.14  4875.5  368.94
  4904.1  370.44  4953.7   370.5  4967.8   368.6    4980  364.55  4982.5  363.75
  4997.3  363.75  4999.8  364.55  5004.2  367.54  5018.5  371.55    5025  372.41
  5028.9  373.73  5034.7  373.73  5052.5  375.81  5059.5  377.12  5064.6  376.92
  5072.8  378.08  5093.1  379.41  5178.9   381.9  5275.8  385.93  5331.8  387.01
#Mann= 4 ,-1 , 0
  4723.7      .1       0    4980     .07       0  4999.8      .1       0
  5052.5     .05       0
Bank Sta=4980,4999.8
XS Rating Curve= 0 ,0
Exp/Cntr=0.3,0.1

Type RM Length L Ch R = 1 ,2688    ,38,38,38
BEGIN DESCRIPTION:
Mapping XS 47e6a524
END DESCRIPTION:
XS GIS Cut Line= 6
      2038560.14      13444072.2      2038490.65       13444057.
      2038232.41     13443603.44      2038143.43     13443497.11
      2037696.38      13443410.3      2037301.42     13443462.38
#Sta/Elev= 30
  4240.7  384.92    4251  384.81  4266.4  383.01  4286.9  382.01  4332.4  381.88
  4375.6  380.78  4391.5  381.76  4397.2  381.02  4428.9  381.78  4515.4  380.44
  4574.5  378.32  4617.7  378.42  4660.9  377.12    4809  375.38  4867.8  372.37
  4887.8  371.23  4951.1  368.49  4980.3  365.04  4982.8  364.24  4997.6  364.24
  5000.1  365.04  5002.6  366.25  5021.1  368.08    5045  368.47    5083  370.94
    5221   375.5  5279.4  378.09    5292  379.51  5410.7  384.24  5827.9  386.56
#Mann= 5 ,-1 , 0
  4240.7     .05       0  4867.8     .08       0  4887.8     .05       0
  4980.3     .04       0  5000.1     .05       0
Bank Sta=4980.3,5000.1
XS Rating Curve= 0 ,0
Exp/Cntr=0.3,0.1

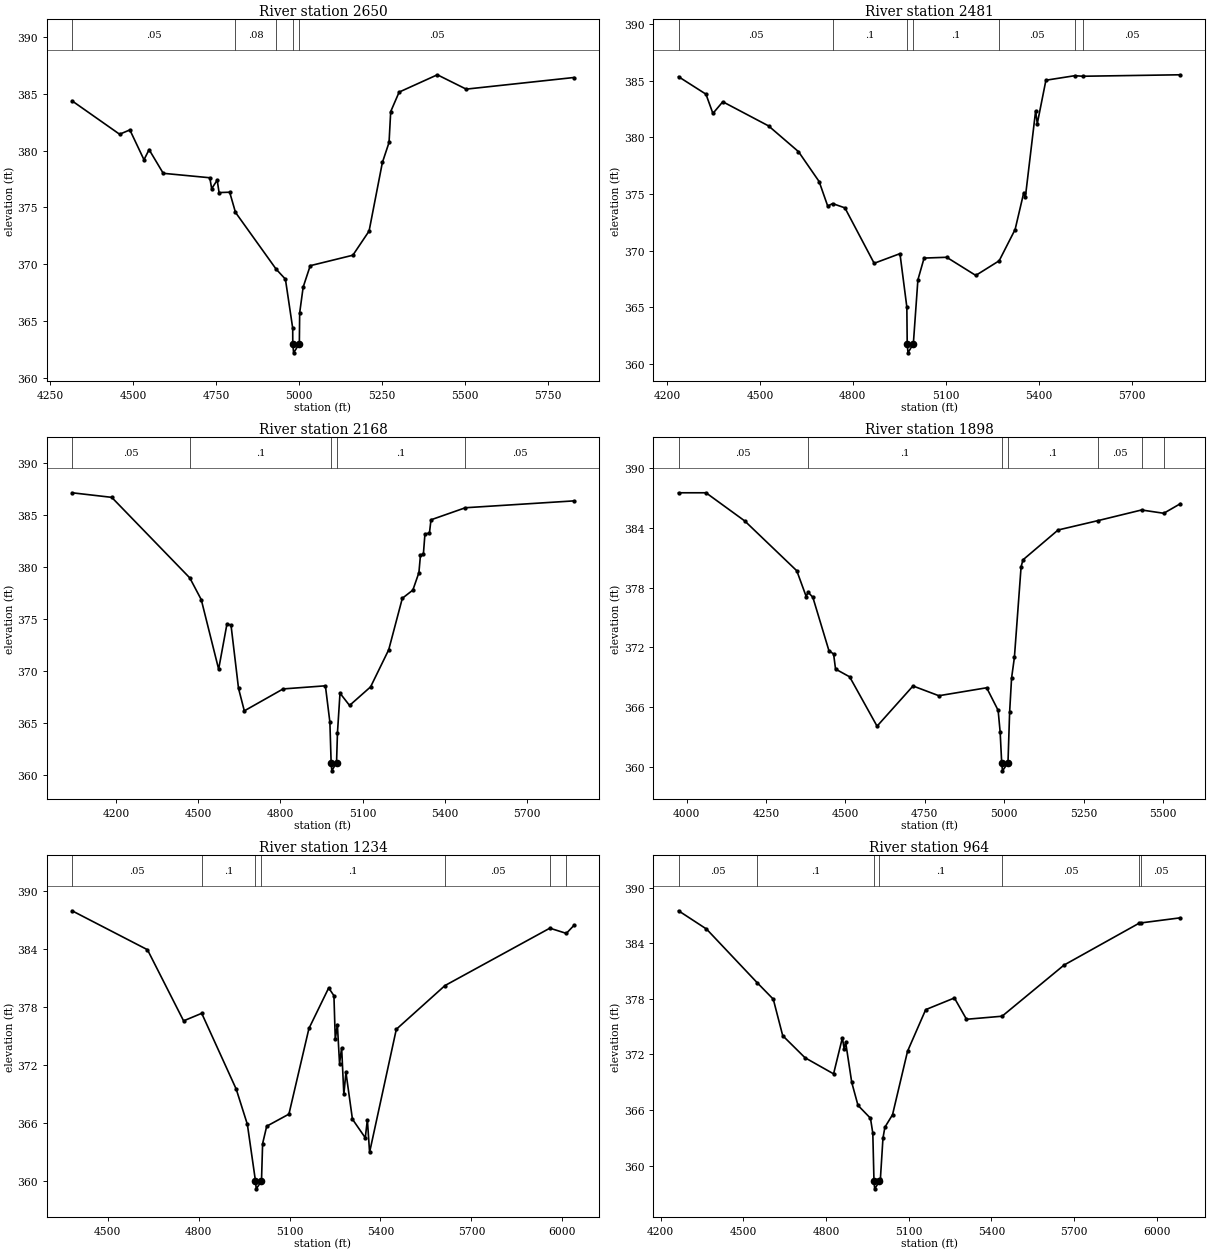
Type RM Length L Ch R = 1 ,2650    ,169,169,169
BEGIN DESCRIPTION:
Mapping XS b0508436
END DESCRIPTION:
XS GIS Cut Line= 6
      2038523.23     13444004.96       2038269.3     13443566.55
      2038195.51     13443477.57      2037965.48     13443403.79
      2037635.62     13443356.05      2037320.95     13443338.69
#Sta/Elev= 30
  4315.6  384.36  4458.9  381.43  4489.8  381.81  4532.4  379.19  4547.8  380.08
  4590.4     378  4730.8  377.61  4736.4  376.65  4753.1   377.4  4758.7  376.31
  4790.7  376.34  4808.2  374.57  4930.9  369.58  4958.7  368.71  4980.7   364.4
  4980.9  363.04  4983.4  362.24  5000.7  363.04  5001.7  365.75  5012.2  368.01
  5033.5  369.89    5162  370.81  5210.9  372.93    5251  378.95  5271.1  380.71
  5276.1  383.42  5301.5  385.13  5416.7  386.65  5503.6  385.39  5828.2  386.41
#Mann= 5 ,-1 , 0
  4315.6     .05       0  4808.2     .08       0  4930.9     .05       0
  4980.9     .04       0  5000.7     .05       0
Bank Sta=4980.9,5000.7
XS Rating Curve= 0 ,0
Exp/Cntr=0.3,0.1

Type RM Length L Ch R = 1 ,2481    ,313,313,313
BEGIN DESCRIPTION:
Liveoak Creek 3.0
END DESCRIPTION:
XS GIS Cut Line= 3
      2038893.84      13443666.8        2038225.       13443325.
      2037392.09     13443076.52
#Sta/Elev= 30
  4237.1  385.35  4325.6  383.81  4348.1  382.11    4380  383.14  4527.8  381.01
  4624.4  378.74  4691.1   376.1  4718.9  373.93  4734.3  374.16  4774.3  373.78
  4868.8  368.89  4952.1  369.74  4974.3  365.03  4975.5  361.79    4978  360.99
  4995.3  361.79    5010  367.43    5030  369.35    5103  369.42  5196.9  367.82
  5272.4  369.11  5323.9  371.87  5351.9  375.13  5357.1  374.74  5390.2  382.34
  5395.5  381.21  5423.4  385.04  5516.9  385.44  5542.1  385.39  5857.4  385.52
#Mann= 7 ,-1 , 0
  4237.1     .05       0  4734.3      .1       0  4975.5     .07       0
  4995.3      .1       0  5272.4     .05       0  5516.9     .08       0
  5542.1     .05       0
Bank Sta=4975.5,4995.3
XS Rating Curve= 0 ,0
Exp/Cntr=0.3,0.1

Type RM Length L Ch R = 1 ,2168    ,270,270,270
BEGIN DESCRIPTION:
Liveoak Creek 2.0
END DESCRIPTION:
XS GIS Cut Line= 3
      2039143.84       13443547.       2038602.2      13443199.8
      2037548.32     13442647.29
#Sta/Elev= 30
  4038.9  387.14  4183.8   386.7    4469  378.95  4510.9  376.86  4574.4  370.17
  4604.8  374.52  4619.6  374.41    4647  368.33  4668.2  366.16    4810  368.27
  4964.4  368.57  4980.8  365.08  4985.4  361.19  4987.9  360.39  5005.2  361.19
  5008.5  364.04  5017.8  367.86  5052.7  366.68  5129.6  368.47  5195.8  372.04
  5245.5  376.99    5284  377.78  5306.1  379.46  5311.7  381.12  5322.5  381.25
  5328.1  383.17  5344.6  383.27  5350.2  384.54  5475.8   385.7  5872.2  386.36
#Mann= 5 ,-1 , 0
  4038.9     .05       0    4469      .1       0  4985.4     .07       0
  5005.2      .1       0  5475.8     .05       0
Bank Sta=4985.4,5005.2
XS Rating Curve= 0 ,0
Exp/Cntr=0.3,0.1

Type RM Length L Ch R = 1 ,1898    ,664,664,664
BEGIN DESCRIPTION:
Mapping XS 21a11580
END DESCRIPTION:
XS GIS Cut Line= 4
      2039168.15     13443491.45      2038574.42      13443074.8
      2038366.09     13442758.82      2037890.41     13442741.46
#Sta/Elev= 30
  3974.9  387.53  4061.3  387.53  4183.3   384.7  4347.2  379.69  4376.8   377.1
  4382.6  377.54  4397.7  377.03  4448.3  371.67  4463.1  371.32  4469.2  369.81
  4513.6  369.03  4599.9  364.07  4713.1  368.11  4794.5  367.13    4945  367.93
  4981.1  365.66  4987.5  363.46  4992.3  360.38  4994.8  359.58  5012.1  360.38
  5017.3  365.49  5023.4   368.9  5032.3  370.98  5053.4   380.1  5059.4  380.79
  5169.9  383.79  5295.3  384.73  5432.6   385.8  5502.6  385.47  5554.7  386.43
#Mann= 7 ,-1 , 0
  3974.9     .05       0  4382.6      .1       0  4992.3     .07       0
  5012.1      .1       0  5295.3     .05       0  5432.6     .15       0
  5502.6     .05       0
Bank Sta=4992.3,5012.1
XS Rating Curve= 0 ,0
Exp/Cntr=0.3,0.1

Type RM Length L Ch R = 1 ,1234    ,270,270,270
BEGIN DESCRIPTION:
Mapping XS 7f2ab15b
END DESCRIPTION:
XS GIS Cut Line= 5
      2039244.53     13443422.01      2038925.11     13443251.88
      2038661.22      13442824.8      2038518.86     13442689.38
       2037925.1     13442727.58
#Sta/Elev= 30
  4382.6  387.92  4631.3  383.89  4750.5  376.53  4810.3  377.31  4924.2  369.46
  4960.9  365.82  4987.7  359.95  4990.2  359.15  5007.5  359.95  5011.2  363.83
  5024.7  365.63    5098  366.88    5164  375.74  5229.2  379.94  5246.5  379.13
  5250.9  374.61  5257.8  376.15    5265  372.11  5271.9  373.75  5279.2  368.92
  5286.1  371.21  5307.5  366.36  5349.9  364.43  5356.8   366.3  5364.1  362.93
  5452.3  375.66  5612.7  380.18  5958.8  386.12  6013.2  385.58    6038   386.4
#Mann= 7 ,-1 , 0
  4382.6     .05       0  4810.3      .1       0  4987.7     .07       0
  5007.5      .1       0  5612.7     .05       0  5958.8     .15       0
  6013.2     .05       0
Bank Sta=4987.7,5007.5
XS Rating Curve= 0 ,0
Exp/Cntr=0.3,0.1

Type RM Length L Ch R = 1 ,964     ,373,373,373
BEGIN DESCRIPTION:
Mapping XS e9bb41b4
END DESCRIPTION:
XS GIS Cut Line= 4
      2039331.37     13443335.23      2039098.72     13442918.55
      2038518.86     13442609.52      2037834.83     13442675.49
#Sta/Elev= 30
  4264.5   387.5    4366  385.53  4549.9  379.74  4608.4  377.96  4642.7  374.02
  4723.6  371.64  4827.3   369.9  4859.3  373.79  4865.6  372.61  4871.2  373.29
  4893.3  368.97  4915.9   366.5  4961.2  365.11  4969.7   363.5    4974  358.29
  4976.5  357.49  4993.8  358.29  4997.3  358.58  5006.6  362.97  5013.6  364.14
  5041.3  365.49  5095.8  372.34  5161.7  376.83  5265.9  378.09  5309.8  375.79
    5439  376.12  5663.9  381.64  5937.7  386.18    5943  386.19    6086  386.74
#Mann= 7 ,-1 , 0
  4264.5     .05       0  4549.9      .1       0    4974     .07       0
  4993.8      .1       0    5439     .05       0  5937.7     .15       0
    5943     .05       0
Bank Sta=4974,4993.8
XS Rating Curve= 0 ,0
Exp/Cntr=0.3,0.1

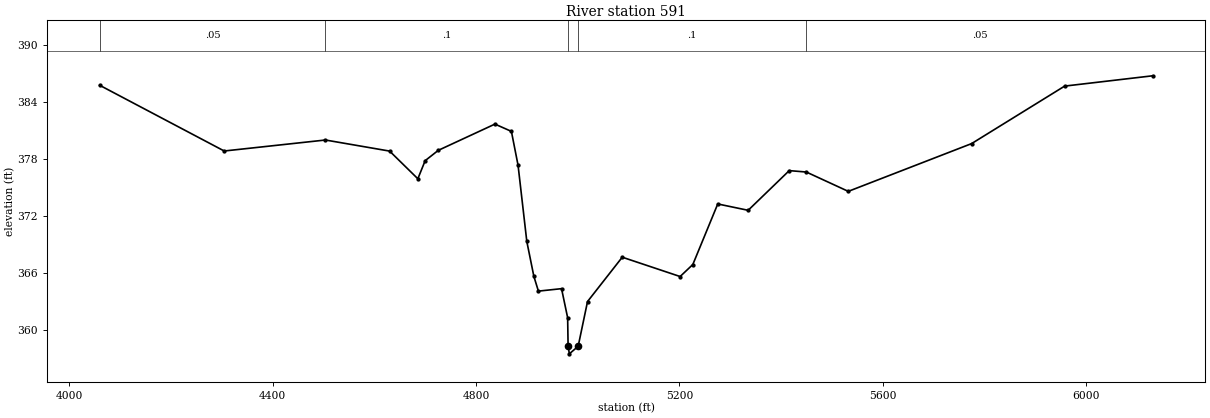
Type RM Length L Ch R = 1 ,591     ,0,0,0
BEGIN DESCRIPTION:
Liveoak Creek 1.0
END DESCRIPTION:
XS GIS Cut Line= 4
      2039375.01     13443225.03      2039246.29     13442595.63
      2038772.34     13442371.67      2037897.38     13442600.83
#Sta/Elev= 30
  4059.7   385.8  4304.7  378.86  4503.8  380.02    4630  378.85  4685.5  375.93
  4699.9  377.84  4725.7  378.93  4837.1   381.7  4869.5  380.93  4882.6  377.35
  4899.8  369.31  4913.7  365.62  4922.6  364.07  4968.1  364.33  4980.1  361.26
    4981  358.25  4983.5  357.45  5000.8  358.25  5019.2  362.97  5087.5  367.65
  5201.3  365.61  5226.3  366.88  5275.3  373.27  5335.1   372.6  5415.9  376.79
  5449.5  376.64    5532   374.6  5774.5  379.64  5957.5  385.71  6130.8   386.8
#Mann= 5 ,-1 , 0
  4059.7     .05       0  4503.8      .1       0    4981     .07       0
  5000.8      .1       0  5449.5     .05       0
Bank Sta=4981,5000.8
XS Rating Curve= 0 ,0
Exp/Cntr=0.3,0.1
LCMann Table=0

Chan Stop Cuts=-1
Use User Specified Reach Order=0
Composite Channel Slope=5