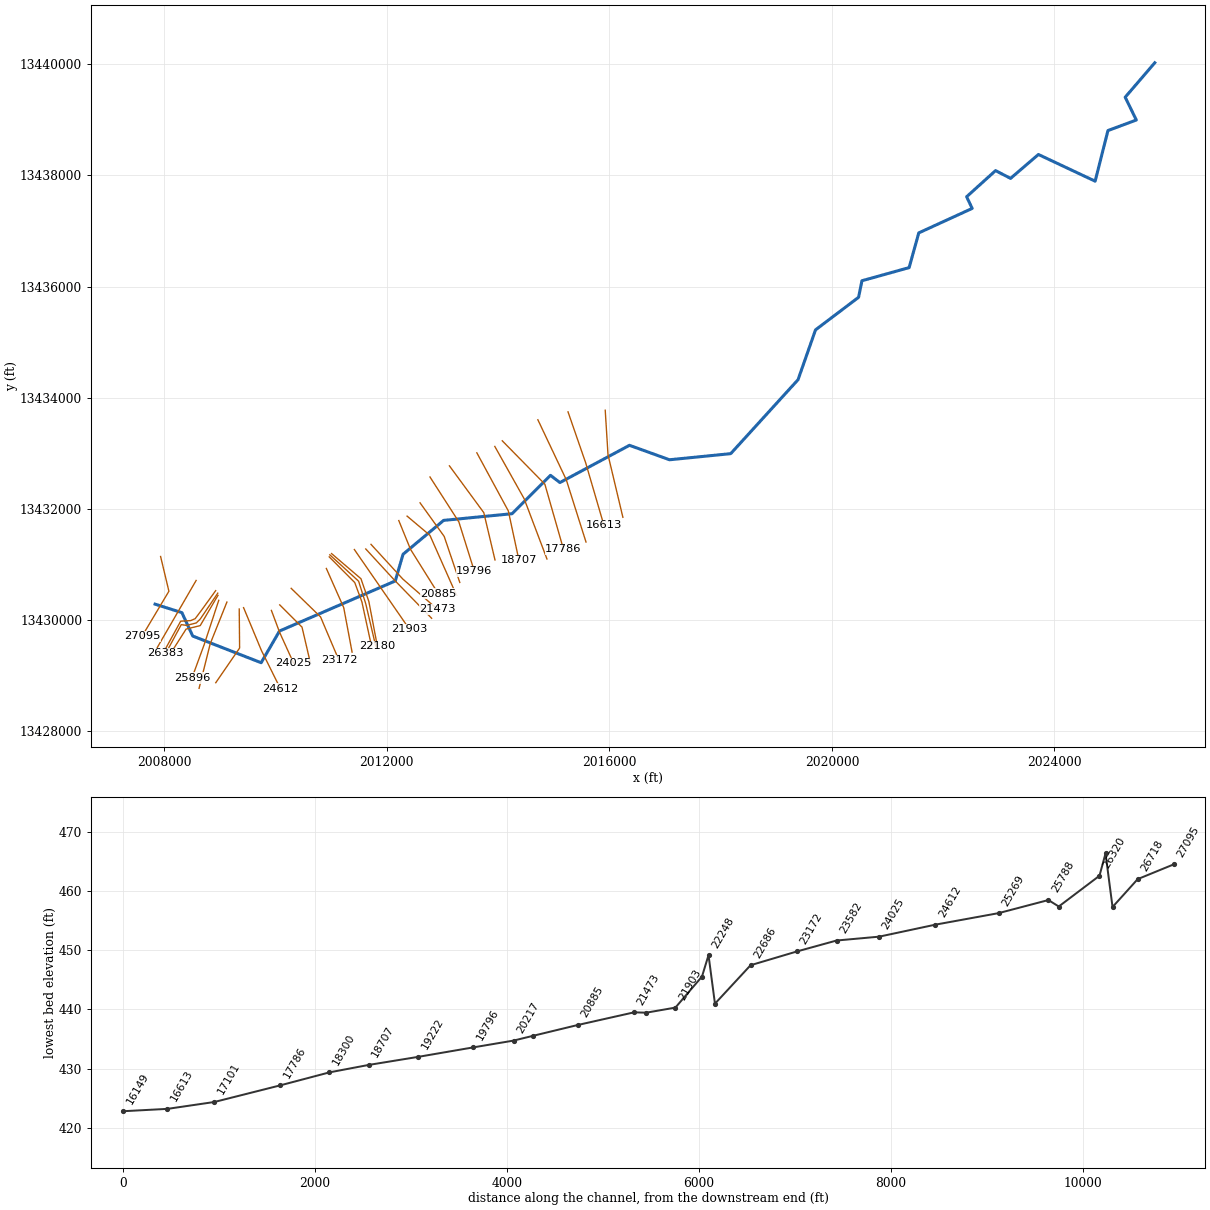
--- Mustang Creek.prj (project) ---

Proj Title=Mustang Creek Base Level Engineering
Current Plan=p01
Default Exp/Contr=0.3,0.1
English Units
Geom File=g01
Flow File=f01
Plan File=p01
Y Axis Title=Elevation
X Axis Title(PF)=Main Channel Distance
X Axis Title(XS)=Station
BEGIN DESCRIPTION:
Mustang Creek
END DESCRIPTION:
DSS Export Rating Curves= 0
DSS Export Rating Curve Sorted= 0
DSS Export Volume Flow Curves= 0
DXF OffsetX= 0
DXF OffsetY= 0
DXF ScaleX= 1
DXF ScaleY= 10

--- Mustang Creek.p01 (plan) ---

Plan Title=Multiple Run
Short Identifier=Multiple
Geom File=g01
Flow File=f01
Subcritical Flow
K Sum by GR= 0
Std Step Tol= 0.01
Critical Tol= 0.01
Num of Std Step Trials= 20
Max Error Tol= 0.3
Flow Tol Ratio= 0.001
Split Flow NTrial= 30
Split Flow Tol= 0.02
Split Flow Ratio= 0.02
Log Output Level= 0
Friction Slope Method= 1
Unsteady Friction Slope Method= 2
Unsteady Bridges Friction Slope Method= 1
Parabolic Critical Depth
Global Vel Dist=  1 , 1 , 1
Global Log Level= 0
CheckData=True
Encroach Param= -1, 0, 0, 0
BEGIN DESCRIPTION:
Multiple Run
END DESCRIPTION:

--- Mustang Creek.f01 (steady flow) ---

Flow Title=Multiple
Program Version=5.05
Number of Profiles= 7
Profile Names=10-year,25-year,50-year,1pct_min,100-year,1pct_plu,500-year
River Rch & RM=Mustang Creek,Reach-1         ,27095
     134     180     217     130     260     518     379
River Rch & RM=Mustang Creek,Reach-1         ,26718
     240     331     406     248     495     988     749
River Rch & RM=Mustang Creek,Reach-1         ,20885
     311     435     538     332     662    1320    1015
River Rch & RM=Mustang Creek,Reach-1         ,16613
     393     555     691     428     855    1705    1328
River Rch & RM=Mustang Creek,Reach-1         ,13324
     477     681     855     533    1064    2123    1676
River Rch & RM=Mustang Creek,Reach-1         ,11509
     500     714     895     557    1112    2219    1747
River Rch & RM=Mustang Creek,Reach-1         ,5845
     585     838    1054     658    1313    2619    2072
Boundary for River Rch & Prof#=Mustang Creek,Reach-1         , 1
Up Type= 0
Dn Type= 3
Dn Slope=0.00218
Boundary for River Rch & Prof#=Mustang Creek,Reach-1         , 2
Up Type= 0
Dn Type= 3
Dn Slope=0.00218
Boundary for River Rch & Prof#=Mustang Creek,Reach-1         , 3
Up Type= 0
Dn Type= 3
Dn Slope=0.00218
Boundary for River Rch & Prof#=Mustang Creek,Reach-1         , 4
Up Type= 0
Dn Type= 3
Dn Slope=0.00218
Boundary for River Rch & Prof#=Mustang Creek,Reach-1         , 5
Up Type= 0
Dn Type= 3
Dn Slope=0.00218
Boundary for River Rch & Prof#=Mustang Creek,Reach-1         , 6
Up Type= 0
Dn Type= 3
Dn Slope=0.00218
Boundary for River Rch & Prof#=Mustang Creek,Reach-1         , 7
Up Type= 0
Dn Type= 3
Dn Slope=0.00218
DSS Import GetInterval= 0
DSS Import GetPeak= 0
DSS Import FillOption= 0

--- Mustang Creek.g01 (geometry) ---

Geom Title=Existing Conditions
Program Version=5.05

River Reach=Mustang Creek   ,Reach-1
Reach XY= 30
      2007834.05     13430288.05      2008316.25     13430135.28
       2008510.8     13429714.54       2009740.8     13429234.54
       2010070.8     13429804.54      2012151.63     13430705.37
       2012290.8     13431184.54       2013020.8     13431794.54
       2014250.8     13431914.54       2014940.8     13432604.54
       2015110.8     13432474.54       2016360.8     13433144.54
       2017080.8     13432884.54       2018180.8     13432994.54
       2019390.8     13434324.54      2019704.67     13435220.44
      2020478.28     13435805.86      2020539.39     13436103.77
      2021387.31     13436339.88       2021560.8     13436964.54
       2022520.8     13437404.54       2022420.8     13437614.54
       2022940.8     13438084.54       2023210.8     13437944.54
       2023710.8     13438374.54       2024730.8     13437894.54
       2024960.8     13438804.54       2025470.8     13438994.54
       2025270.8     13439404.54      2025802.61     13440023.87

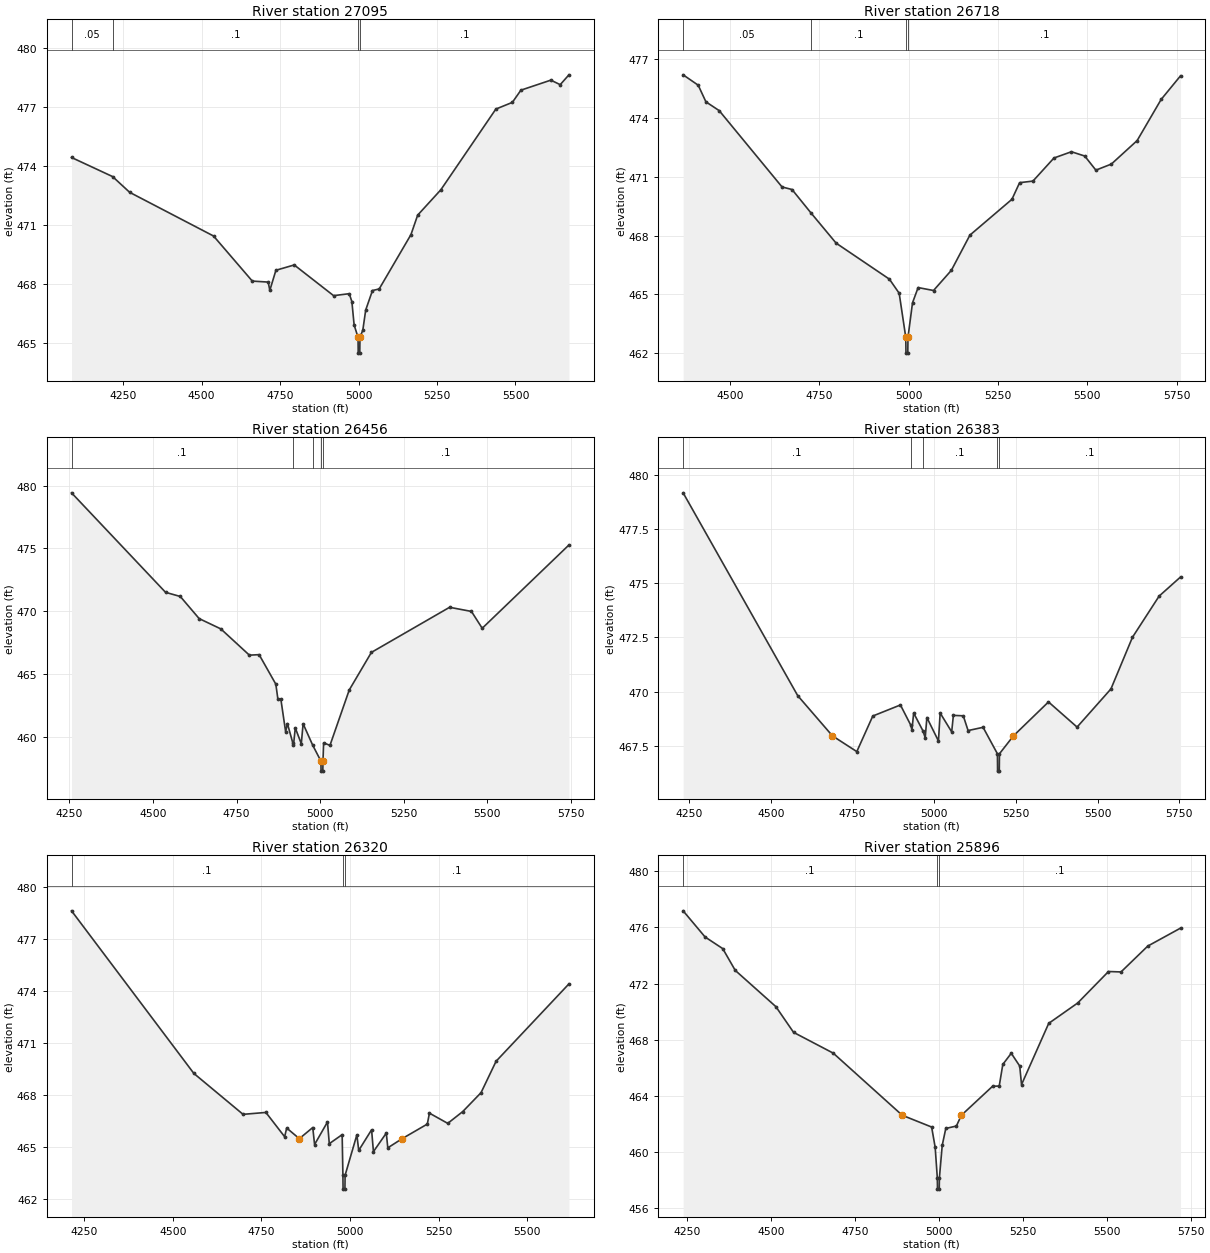
Type RM Length L Ch R = 1 ,27095   ,377,377,377
BEGIN DESCRIPTION:
Mustang Creek 50.0
END DESCRIPTION:
XS GIS Cut Line= 3
       2007933.4     13431145.12      2008082.71     13430520.11
      2007600.05     13429711.04
#Sta/Elev= 30
  4085.6  474.43  4216.4  473.46  4270.8  472.66  4538.1  470.44  4661.5  468.15
  4712.1   468.1  4717.3  467.68  4736.7   468.7  4795.1  468.97  4920.5  467.41
  4970.3  467.51  4978.7  467.11  4985.9  465.92  4998.4  465.29  4998.9  464.49
  5003.9  464.49  5004.4  465.29  5013.6  465.66  5022.8  466.68  5044.3  467.67
  5065.7  467.75  5166.9  470.51  5188.3   471.5  5262.2  472.79  5437.4  476.89
    5490  477.23  5517.2  477.85  5612.6  478.36  5642.4  478.13  5670.3  478.63
#Mann= 4 ,-1 , 0
  4085.6     .05       0  4216.4      .1       0  4998.4     .07       0
  5004.4      .1       0
Bank Sta=4998.4,5004.4
XS Rating Curve= 0 ,0
Exp/Cntr=0.3,0.1

Type RM Length L Ch R = 1 ,26718   ,262,262,262
BEGIN DESCRIPTION:
Mapping XS f2623e5d
END DESCRIPTION:
XS GIS Cut Line= 2
      2008572.31     13430714.58      2007874.49     13429509.89
#Sta/Elev= 30
  4369.1  476.21  4411.3  475.68  4432.9  474.83  4470.1  474.38    4646  470.48
  4673.9  470.35  4726.2  469.17  4797.3  467.61  4946.4  465.77  4973.8  465.05
  4992.3  462.79  4992.8  461.99  4997.9  461.99  4998.4  462.79  5011.1  464.56
  5026.8  465.34  5069.9  465.19  5119.8  466.22  5171.8  468.02  5289.4  469.85
  5310.9   470.7  5348.2  470.78    5407  471.96  5455.9  472.28  5493.2  472.06
  5524.3  471.34  5567.7  471.65  5639.8  472.85  5706.9  474.95  5761.3  476.16
#Mann= 4 ,-1 , 0
  4369.1     .05       0  4726.2      .1       0  4992.3     .07       0
  4998.4      .1       0
Bank Sta=4992.3,4998.4
XS Rating Curve= 0 ,0
Exp/Cntr=0.3,0.1

Type RM Length L Ch R = 1 ,26456   ,73,73,73
BEGIN DESCRIPTION:
Mapping XS 617d1efc
END DESCRIPTION:
XS GIS Cut Line= 6
        2008923.     13430530.54      2008669.51     13430179.83
      2008554.93     13430027.05      2008475.07     13429992.33
      2008294.51     13429981.92      2008006.96     13429458.78
#Sta/Elev= 30
  4256.3  479.43  4537.7  471.51  4581.8  471.18  4638.2  469.42  4703.1   468.6
  4788.5  466.51  4817.7  466.55  4867.7   464.2  4873.9     463  4882.7  463.01
    4897  460.42  4902.4  461.06  4918.8  459.49  4920.4  459.32  4925.9  460.72
  4943.9  459.46  4949.3  461.05  4978.1  459.34  5002.6  458.08  5003.1  457.28
  5008.3  457.28  5008.8  458.08  5010.7  459.53  5029.7  459.33  5087.4  463.74
  5153.7  466.73  5387.7  470.32  5453.1  469.99  5485.3  468.65  5744.9  475.28
#Mann= 5 ,-1 , 0
  4256.3      .1       0  4918.8     .12       0  4978.1      .1       0
  5002.6     .07       0  5008.8      .1       0
Bank Sta=5002.6,5008.8
XS Rating Curve= 0 ,0
Exp/Cntr=0.3,0.1

Type RM Length L Ch R = 1 ,26383   ,63,63,63
BEGIN DESCRIPTION:
Mapping XS 9c91947f
END DESCRIPTION:
XS GIS Cut Line= 6
      2008961.21     13430485.43      2008648.68     13430023.58
      2008575.76     13429950.67      2008402.15     13429905.53
      2008304.93     13429919.42      2008027.16     13429405.54
#Sta/Elev= 30
  4231.1  479.16  4581.8  469.81 4688.15467.9556  4762.7  467.23  4811.6  468.87
  4896.2  469.38  4927.5  468.46  4931.5  468.23  4936.7  469.01  4964.7   468.2
  4972.1  467.87  4977.2   468.8  5012.6  467.72  5017.8  469.01  5053.1  468.14
  5058.3   468.9  5088.6  468.88  5103.3   468.2  5149.2  468.35  5193.1  467.13
  5193.6  466.33  5198.8  466.33  5199.3  467.13 5242.11467.9555  5349.4  469.52
  5436.9  468.36  5540.6  470.12  5606.4   472.5  5688.1   474.4  5753.6  475.28
#Mann= 5 ,-1 , 0
  4231.1      .1       0  4927.5     .12       0  4964.7      .1       0
  5193.1     .07       0  5199.3      .1       0
Bank Sta=4688.15,5242.11
XS Rating Curve= 0 ,0
Exp/Cntr=0.3,0.1

Type RM Length L Ch R = 1 ,26320   ,424,424,424
BEGIN DESCRIPTION:
Mapping XS c827791b
END DESCRIPTION:
XS GIS Cut Line= 4
      2008964.64     13430447.17      2008645.21     13429902.05
      2008391.74     13429839.55      2008117.75     13429409.49
#Sta/Elev= 30
  4214.7   478.6  4559.6  469.23  4698.4  466.87  4762.8  466.98  4815.7  465.58
  4821.5  466.08 4857.15465.4692    4895  466.11  4900.1  465.13  4936.5  466.43
  4941.6  465.18  4977.9   465.7    4980  463.36  4980.5  462.56  4985.7  462.56
  4986.2  463.36  5019.4  465.69  5024.6  464.79  5060.9  465.98  5066.1  464.72
  5102.4  465.79  5106.6  464.94 5147.14465.4689  5218.1  466.31    5224  466.94
  5275.7  466.35    5318  467.03  5369.6  468.12    5412  469.93  5617.5  474.39
#Mann= 3 ,-1 , 0
  4214.7      .1       0    4980     .07       0  4986.2      .1       0
Bank Sta=4857.15,5147.14
XS Rating Curve= 0 ,0
Exp/Cntr=0.3,0.1

Type RM Length L Ch R = 1 ,25896   ,108,108,108
BEGIN DESCRIPTION:
Mustang Creek 49.0
END DESCRIPTION:
XS GIS Cut Line= 3
      2008978.55     13430356.94      2008714.65     13429554.83
      2008496.33     13428958.77
#Sta/Elev= 30
  4239.5  477.18  4304.7  475.32  4357.3  474.49  4394.5  472.94  4515.3  470.36
  4567.9  468.53  4685.9  467.05 4891.12462.6273  4978.5  461.79    4989  460.35
  4995.4  458.17  4995.9  457.37  5001.1  457.37  5001.6  458.17    5010  460.49
  5020.6  461.69  5052.1  461.86  5066.9 462.627  5159.6  464.69  5179.5  464.71
  5190.2  466.25  5215.3  467.04  5240.5  466.13  5245.8  464.81  5326.7  469.17
  5412.9  470.62  5504.4  472.86  5541.7  472.83  5621.2  474.67  5718.7  475.95
#Mann= 3 ,-1 , 0
  4239.5      .1       0  4995.4     .07       0  5001.6      .1       0
Bank Sta=4891.12,5066.9
XS Rating Curve= 0 ,0
Exp/Cntr=0.3,0.1

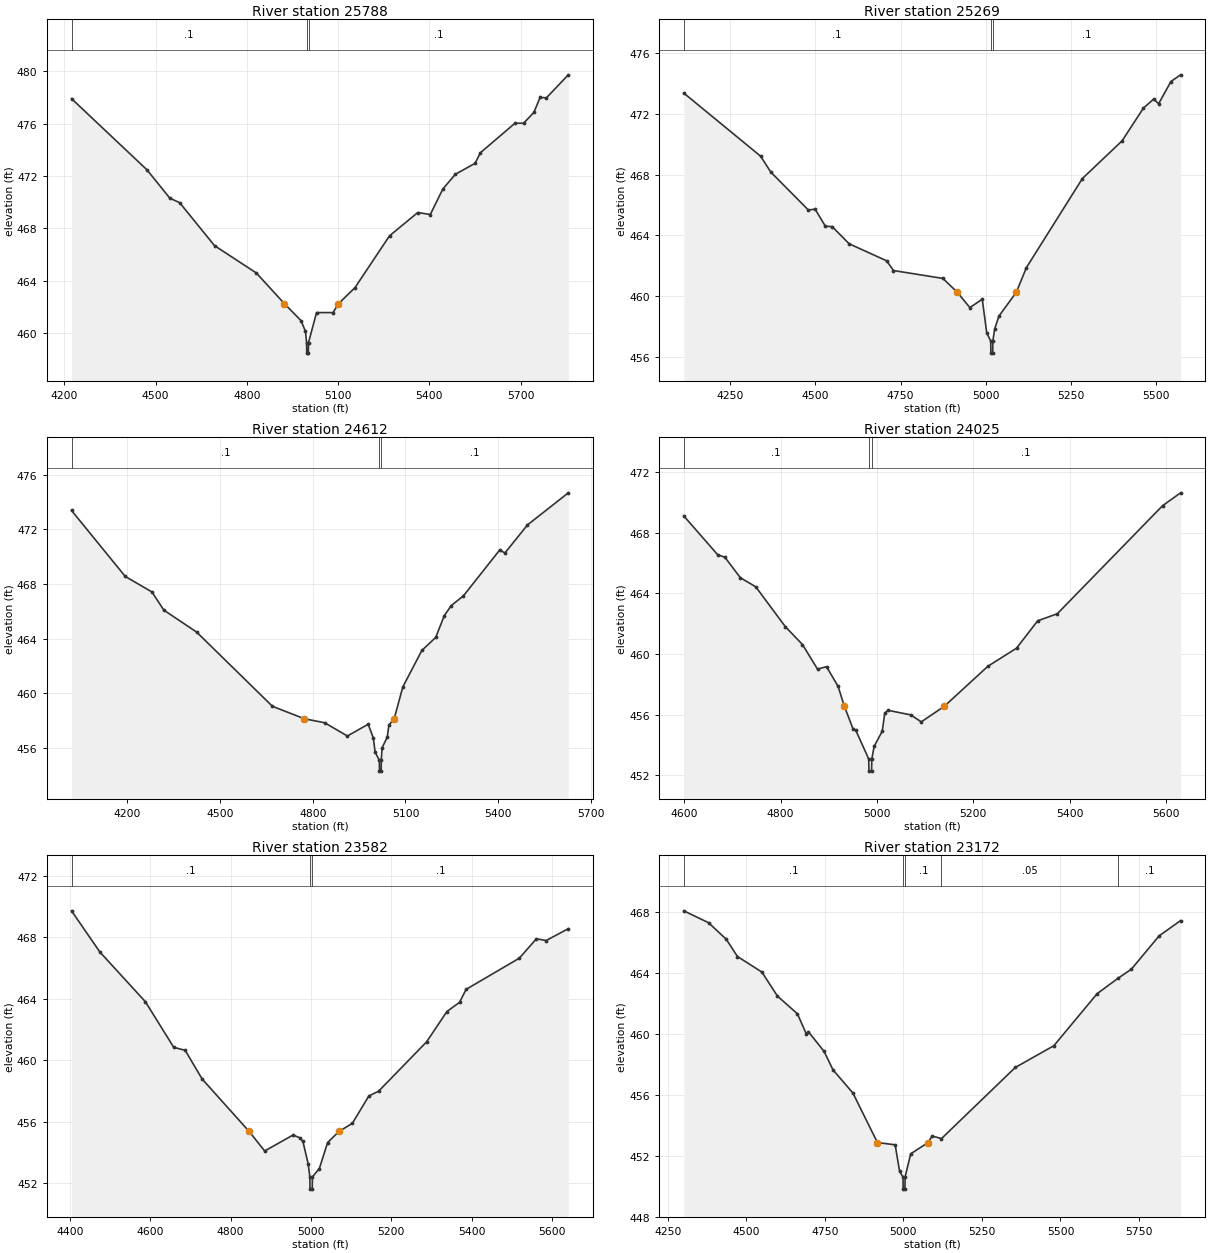
Type RM Length L Ch R = 1 ,25788   ,519,519,519
BEGIN DESCRIPTION:
Mustang Creek 48.0
END DESCRIPTION:
XS GIS Cut Line= 3
      2009125.01     13430325.04        2008825.       13429575.
      2008625.01     13428775.03
#Sta/Elev= 30
    4224  477.92  4471.8  472.48  4547.1  470.31  4579.5  469.96  4693.9  466.68
  4831.2  464.59 4923.61462.2409    4978  460.95  4992.8  460.12  4996.4  459.26
  4996.9  458.46  5002.2  458.46  5002.7  459.26  5029.1  461.56  5083.4  461.56
 5101.24462.2408  5155.5  463.47  5268.9  467.43  5361.7  469.21  5402.9  469.06
  5444.1  471.01  5485.4  472.14  5549.8  472.97  5567.8  473.79  5681.2  476.04
  5709.5  476.04    5743  476.86  5763.7  478.01  5784.3  477.98  5856.4  479.74
#Mann= 3 ,-1 , 0
    4224      .1       0  4996.4     .07       0  5002.7      .1       0
Bank Sta=4923.61,5101.24
XS Rating Curve= 0 ,0
Exp/Cntr=0.3,0.1

Type RM Length L Ch R = 1 ,25269   ,657,657,657
BEGIN DESCRIPTION:
Mustang Creek 47.0
END DESCRIPTION:
XS GIS Cut Line= 3
       2009346.6     13430200.65      2009353.54     13429499.28
      2008925.01     13428875.02
#Sta/Elev= 30
  4113.4  473.38  4339.1  469.22  4369.1  468.17  4479.1  465.68  4499.1  465.73
  4529.1  464.61  4549.1  464.58  4599.1  463.45  4709.1  462.33  4729.1  461.69
  4874.3  461.17 4916.35460.2596  4953.4  459.25  4989.8   459.8  5002.9  457.58
  5014.6  457.05  5015.1  456.25  5020.4  456.25  5020.9  457.05  5026.2  457.84
  5038.7  458.69 5089.82  460.26  5119.3  461.88  5283.7  467.75  5400.2  470.23
    5463  472.39  5492.8  472.98  5507.7  472.68  5543.6  474.14    5572  474.58
#Mann= 3 ,-1 , 0
  4113.4      .1       0  5014.6     .07       0  5020.9      .1       0
Bank Sta=4916.35,5089.82
XS Rating Curve= 0 ,0
Exp/Cntr=0.3,0.1

Type RM Length L Ch R = 1 ,24612   ,587,587,587
BEGIN DESCRIPTION:
Mustang Creek 46.0
END DESCRIPTION:
XS GIS Cut Line= 3
      2009424.98     13430225.04       2009745.9     13429454.14
      2010089.66     13428763.16
#Sta/Elev= 30
  4019.9  473.38  4193.9  468.55  4279.9  467.42  4318.5  466.09  4424.7  464.48
  4669.9  459.05 4773.35  458.14  4838.7  457.85  4912.2  456.88  4979.4  457.74
  4996.2  456.73  5001.8   455.7  5015.4  455.11  5015.9  454.31  5021.3  454.31
  5021.8  455.11  5024.2  456.01    5041  456.79  5046.6  457.69 5063.47458.1397
  5091.4  460.47    5153  463.14  5197.8  464.09  5225.7  465.69  5248.1  466.42
  5287.3  467.13  5404.9  470.49  5421.7  470.27  5494.5  472.32  5626.7  474.67
#Mann= 3 ,-1 , 0
  4019.9      .1       0  5015.4     .07       0  5021.8      .1       0
Bank Sta=4773.35,5063.47
XS Rating Curve= 0 ,0
Exp/Cntr=0.3,0.1

Type RM Length L Ch R = 1 ,24025   ,443,443,443
BEGIN DESCRIPTION:
Mustang Creek 45.0
END DESCRIPTION:
XS GIS Cut Line= 3
        2009925.     13430175.01        2010075.       13429775.
      2010325.02     13429224.96
#Sta/Elev= 30
    4599  469.12  4669.3  466.56  4684.4  466.39  4716.5  465.04  4748.5  464.44
  4809.9  461.81  4845.5  460.63  4876.7  459.01  4895.4  459.17  4919.4  457.87
 4932.42456.5597  4950.6  455.05  4955.9  454.99    4983  453.08  4983.5  452.28
  4988.9  452.28  4989.4  453.08  4994.2  453.91  5011.1  454.92  5016.4  456.12
  5023.5  456.29  5070.1  455.99  5092.1  455.53 5139.95456.5597  5230.5   459.2
  5289.8  460.39  5333.8   462.2  5374.4  462.66    5593  469.79  5630.4  470.64
#Mann= 3 ,-1 , 0
    4599      .1       0    4983     .07       0  4989.4      .1       0
Bank Sta=4932.42,5139.95
XS Rating Curve= 0 ,0
Exp/Cntr=0.3,0.1

Type RM Length L Ch R = 1 ,23582   ,410,410,410
BEGIN DESCRIPTION:
Mustang Creek 44.0
END DESCRIPTION:
XS GIS Cut Line= 3
      2010074.98     13430275.02        2010475.       13429875.
      2010627.86     13429221.46
#Sta/Elev= 30
  4404.1  469.73  4474.8  467.05    4588  463.82  4658.7  460.85    4687  460.66
  4729.4  458.79 4846.43455.3799    4885  454.11  4955.7  455.15  4972.4  454.97
  4980.1  454.74  4993.6  453.25  4997.4  452.43  4997.9  451.63  5003.4  451.63
  5003.9  452.43  5021.2  452.97  5041.7  454.66 5070.01455.3799  5103.3  455.91
  5144.4  457.69  5168.7     458  5288.2  461.21  5338.7  463.18  5370.3  463.78
  5386.4  464.62    5519  466.65  5561.5  467.91    5586   467.8    5641  468.57
#Mann= 3 ,-1 , 0
  4404.1      .1       0  4997.4     .07       0  5003.9      .1       0
Bank Sta=4846.43,5070.01
XS Rating Curve= 0 ,0
Exp/Cntr=0.3,0.1

Type RM Length L Ch R = 1 ,23172   ,486,486,486
BEGIN DESCRIPTION:
Mustang Creek 43.0
END DESCRIPTION:
XS GIS Cut Line= 3
      2010280.65     13430572.17       2010808.4      13430058.3
      2011138.25     13429280.56
#Sta/Elev= 30
    4301  468.08  4379.8   467.3  4436.4  466.21  4471.9  465.08  4549.6  464.06
  4599.2  462.48  4662.7  461.32    4691     460    4698  460.13  4747.6  458.85
  4775.9  457.64  4839.5  456.11 4917.36452.8608  4973.9  452.71  4988.1  450.96
  4998.9   450.6  4999.4   449.8    5005   449.8  5005.5   450.6  5023.4  452.12
 5078.69452.8609  5091.5  453.29  5121.4  453.12  5356.2  457.79  5479.1  459.22
  5616.9  462.64    5684  463.66  5725.5  464.24  5813.9  466.43  5882.4  467.44
#Mann= 5 ,-1 , 0
    4301      .1       0  4998.9     .07       0  5005.5      .1       0
  5121.4     .05       0    5684      .1       0
Bank Sta=4917.36,5078.69
XS Rating Curve= 0 ,0
Exp/Cntr=0.3,0.1

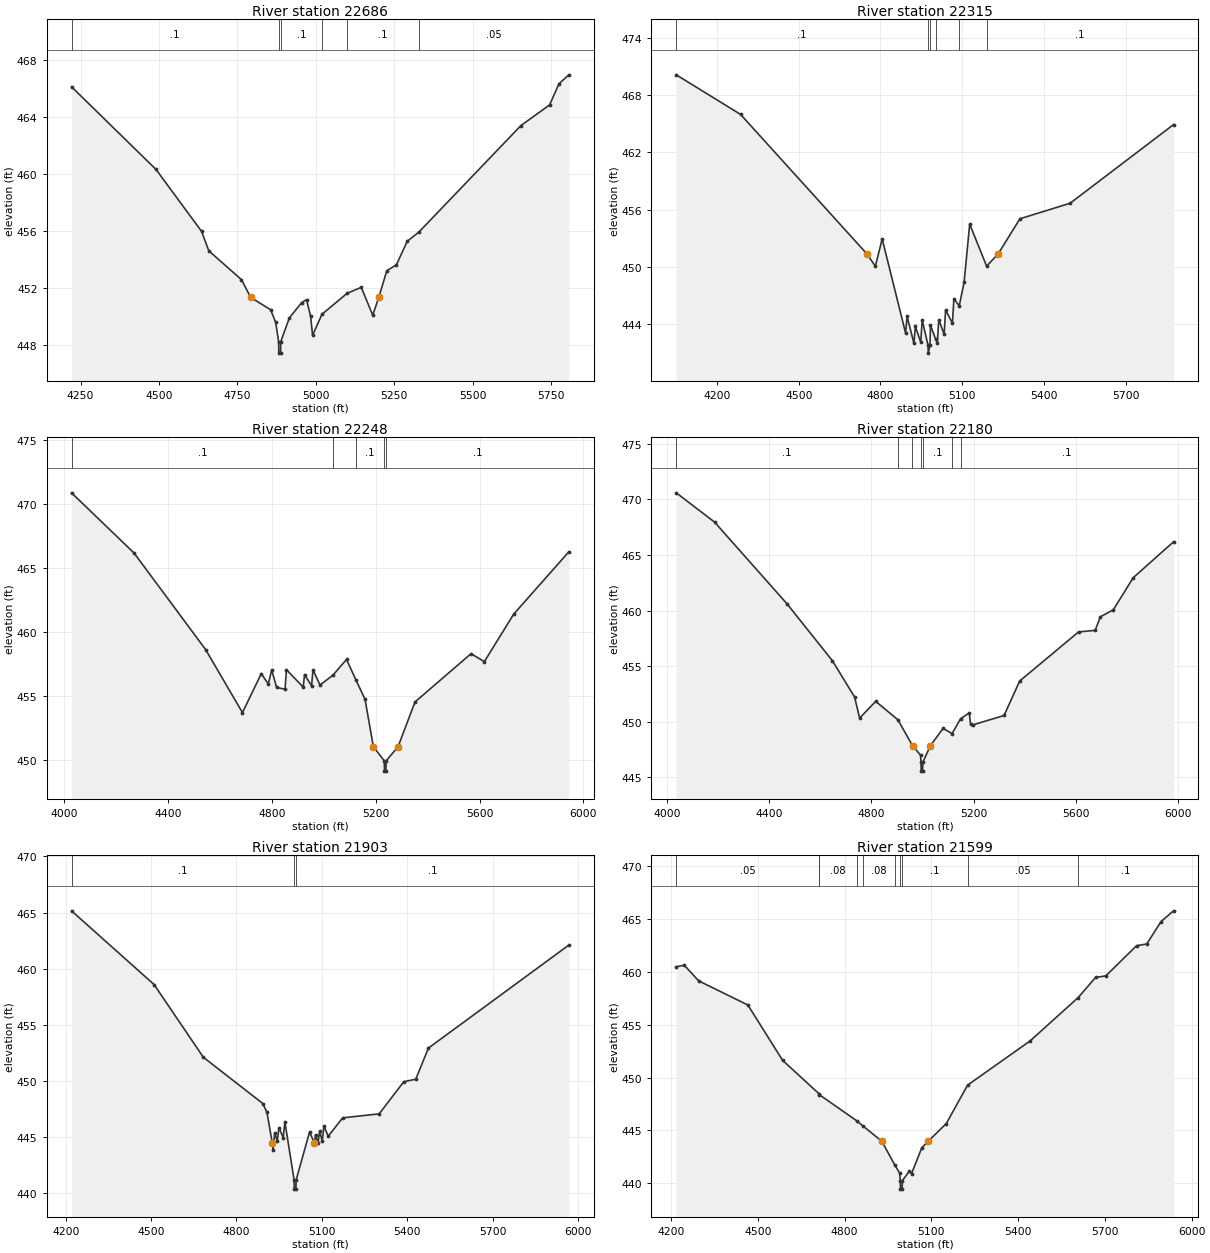
Type RM Length L Ch R = 1 ,22686   ,371,371,371
BEGIN DESCRIPTION:
Mustang Creek 42.0
END DESCRIPTION:
XS GIS Cut Line= 3
      2010912.55     13430929.87        2011225.       13430225.
      2011375.01     13429424.95
#Sta/Elev= 30
  4221.2  466.13  4490.4  460.34  4635.6     456  4658.8  454.63  4762.9  452.61
 4792.18451.3668    4856   450.5  4871.9  449.62  4881.4  448.26  4881.9  447.46
  4887.6  447.46  4888.1  448.26  4915.6  449.93  4954.6     451  4970.3  451.21
  4983.3  450.04  4989.5  448.71  5019.7  450.19  5100.1  451.66  5144.8  452.07
  5181.3  450.12 5200.54451.3669  5226.2  453.24  5256.7  453.65  5291.5  455.31
  5328.2  455.94  5653.5  463.41  5745.1  464.86  5774.8  466.34  5806.2  466.97
#Mann= 6 ,-1 , 0
  4221.2      .1       0  4881.4     .07       0  4888.1      .1       0
  5019.7     .12       0  5100.1      .1       0  5328.2     .05       0
Bank Sta=4792.18,5200.54
XS Rating Curve= 0 ,0
Exp/Cntr=0.3,0.1

Type RM Length L Ch R = 1 ,22315   ,67,67,67
BEGIN DESCRIPTION:
Mapping XS 9af0e1cf
END DESCRIPTION:
XS GIS Cut Line= 4
      2010964.63     13431138.18      2011422.99     13430676.36
      2011551.46     13430329.14      2011721.61     13429544.37
#Sta/Elev= 30
  4050.9  470.14  4286.8  465.99 4750.29451.3689  4781.2  450.08  4806.3  452.93
  4892.1  443.07  4897.5  444.83  4922.6     442  4927.9  443.77  4947.6  442.12
    4953  444.43  4974.6  441.77  4975.1  440.97  4981.4  441.77  4983.4  443.88
  5002.2  442.43  5008.4  442.05  5013.8  444.47  5033.5  442.95  5038.8  445.49
  5063.9  444.11  5069.2  446.65    5089  445.94  5106.7  448.39  5127.2   454.5
  5189.2  450.09 5231.57451.3691  5311.4  455.05  5495.6  456.68  5874.8  464.92
#Mann= 6 ,-1 , 0
  4050.9      .1       0  4974.6     .07       0  4981.4      .1       0
  5002.2     .12       0    5089     .07       0  5189.2      .1       0
Bank Sta=4750.29,5231.57
XS Rating Curve= 0 ,0
Exp/Cntr=0.3,0.1

Type RM Length L Ch R = 1 ,22248   ,68,68,68
BEGIN DESCRIPTION:
Mustang Creek 41.0
END DESCRIPTION:
XS GIS Cut Line= 4
      2010975.02     13431174.98      2011492.43     13430700.67
       2011620.9     13430294.42      2011801.11     13429528.53
#Sta/Elev= 30
  4028.8  470.89  4269.6  466.19  4545.2  458.65    4687  453.73  4759.4  456.77
  4786.4  455.97  4799.6  457.06  4818.7  455.69  4851.1  455.56  4856.3  457.08
  4920.9  455.72  4926.2   456.7  4953.2  455.82  4958.5  457.07  4985.6  455.88
  5035.8  456.66  5087.7  457.88    5124  456.28  5159.1  454.76 5191.05 451.075
  5233.3  449.96  5233.8  449.16  5239.6  449.16  5240.1  449.96 5286.32451.0744
  5351.4  454.56  5567.1  458.33  5618.5  457.71  5731.5  461.42  5943.6  466.28
#Mann= 5 ,-1 , 0
  4028.8      .1       0  5035.8     .16       0    5124      .1       0
  5233.3     .07       0  5240.1      .1       0
Bank Sta=5191.05,5286.32
XS Rating Curve= 0 ,0
Exp/Cntr=0.3,0.1

Type RM Length L Ch R = 1 ,22180   ,277,277,277
BEGIN DESCRIPTION:
Mapping XS f63b87c6
END DESCRIPTION:
XS GIS Cut Line= 4
      2011006.33     13431197.19       2011534.1      13430745.8
      2011676.46     13430336.08      2011829.23     13429534.02
#Sta/Elev= 30
    4037   470.6  4186.6  467.97  4469.8  460.62  4647.6  455.49  4734.5  452.22
  4754.1  450.32    4817  451.83  4903.5  450.18  4960.5  447.86 4961.19447.8427
  4992.4  446.99  4994.3  446.35  4994.8  445.55  5000.6  445.55  5001.1  446.35
 5031.22 447.843  5080.5   449.4  5115.8  448.93    5149  450.27  5182.9  450.79
    5188  449.78  5196.9  449.71    5319  450.56  5380.1  453.66  5610.4  458.08
  5675.3  458.22  5695.7  459.44  5746.6  460.08  5824.2  462.96  5981.7  466.19
#Mann= 7 ,-1 , 0
    4037      .1       0  4903.5     .12       0  4960.5      .1       0
  4994.3     .07       0  5001.1      .1       0  5115.8     .16       0
    5149      .1       0
Bank Sta=4961.19,5031.22
XS Rating Curve= 0 ,0
Exp/Cntr=0.3,0.1

Type RM Length L Ch R = 1 ,21903   ,304,304,304
BEGIN DESCRIPTION:
Mapping XS 5b286878
END DESCRIPTION:
XS GIS Cut Line= 2
      2011416.05     13431270.11      2012409.12     13429832.57
#Sta/Elev= 30
  4220.4  465.15  4510.5  458.57  4683.6  452.08  4892.5  447.95  4907.2  447.16
 4925.63444.4286  4928.3  443.84  4934.4  445.34  4943.2   444.6  4949.2   445.8
  4964.1  444.91  4970.2   446.3  5002.6  441.11  5003.1  440.31  5008.9  440.31
  5009.4  441.11  5056.7   445.4 5073.89444.4292  5077.7  445.16  5086.5  444.43
  5092.5  445.52  5101.3  444.57  5107.4  445.95  5122.3  445.03    5173  446.67
  5301.4  447.03  5387.9   449.9  5429.9  450.12  5474.5   452.9  5967.6  462.09
#Mann= 3 ,-1 , 0
  4220.4      .1       0  5002.6     .07       0  5009.4      .1       0
Bank Sta=4925.63,5073.89
XS Rating Curve= 0 ,0
Exp/Cntr=0.3,0.1

Type RM Length L Ch R = 1 ,21599   ,126,126,126
BEGIN DESCRIPTION:
Mustang Creek 40.0
END DESCRIPTION:
XS GIS Cut Line= 3
      2011620.91     13431280.52      2012141.74     13430714.55
      2012804.93       13430034.
#Sta/Elev= 30
  4217.9   460.5  4245.9  460.64  4295.3  459.16  4465.4  456.88  4585.6  451.64
  4710.6   448.5  4713.2  448.38  4842.4  445.91  4863.4  445.43 4928.95443.9753
  4972.7  441.77  4990.2  440.98  4992.7  440.25  4993.2  439.45  4999.1  439.45
  4999.6  440.25  5024.4  441.17  5031.4  440.91  5066.9  443.36 5088.78443.9755
  5151.7  445.66  5225.2  449.29  5441.6  453.48  5607.6  457.58    5668  459.49
  5703.2  459.63  5809.4  462.49  5844.7  462.65  5894.1  464.77  5937.3  465.79
#Mann= 10 ,-1 , 0
  4217.9     .05       0  4710.6      .1       0  4713.2     .08       0
  4842.4      .1       0  4863.4     .08       0  4972.7      .1       0
  4992.7     .07       0  4999.6      .1       0  5225.2     .05       0
  5607.6      .1       0
Bank Sta=4928.95,5088.78
XS Rating Curve= 0 ,0
Exp/Cntr=0.3,0.1

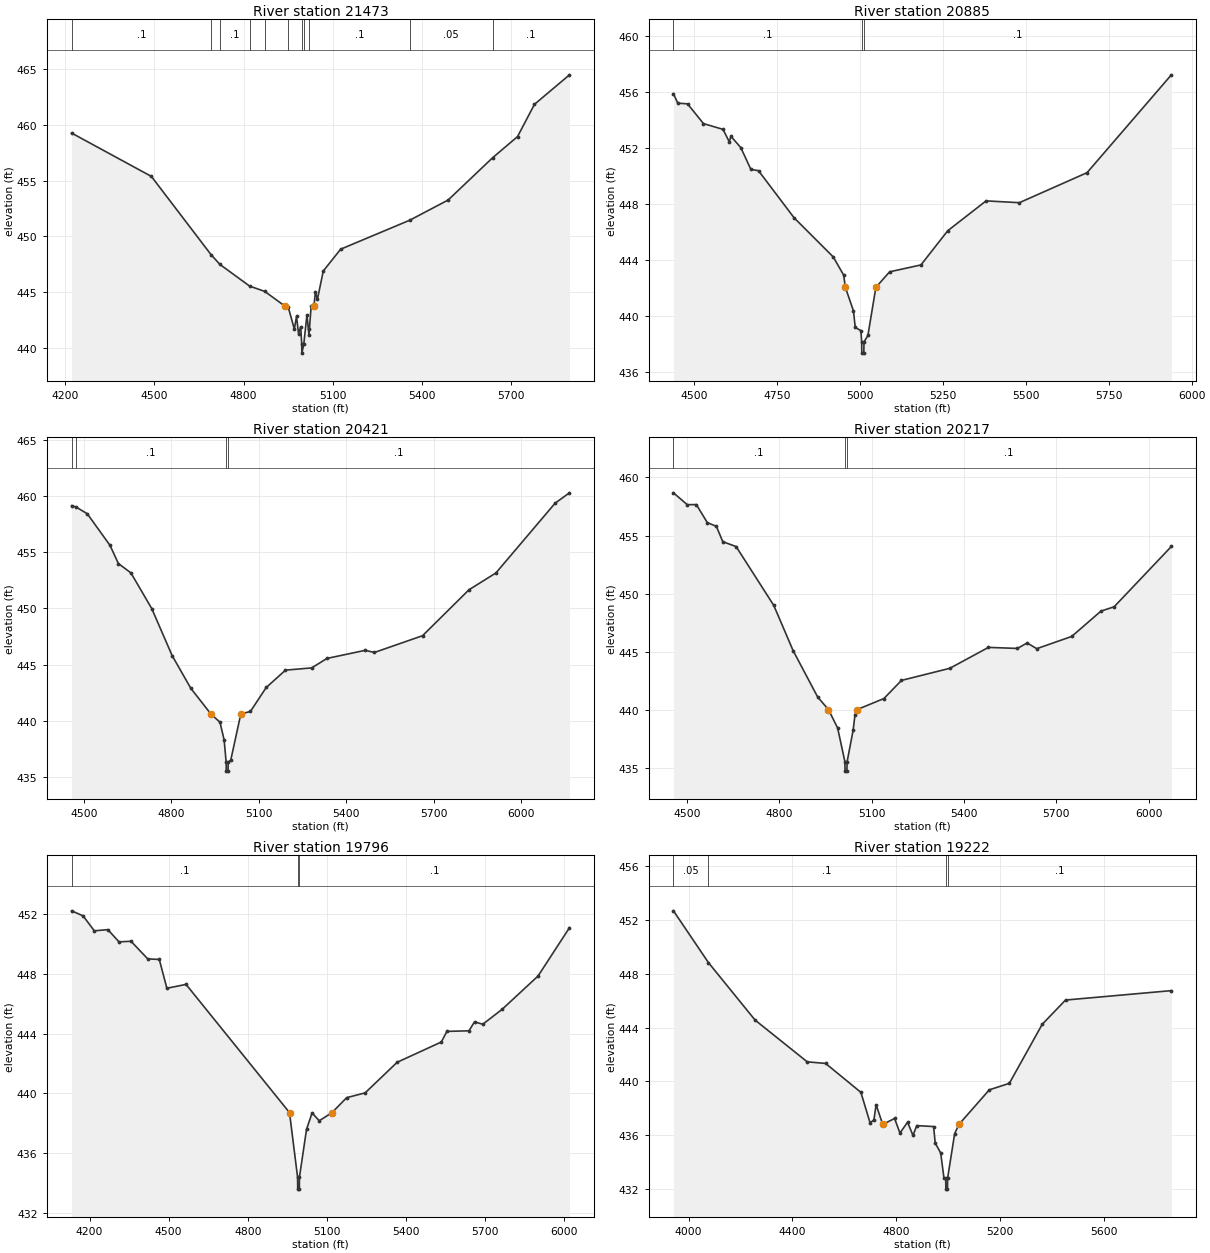
Type RM Length L Ch R = 1 ,21473   ,588,588,588
BEGIN DESCRIPTION:
Mustang Creek 39.0
END DESCRIPTION:
XS GIS Cut Line= 3
      2011714.68     13431363.83      2012287.57     13430738.86
      2012911.32     13430194.81
#Sta/Elev= 30
  4221.4  459.29    4490  455.39  4690.7  448.36  4720.7  447.48  4820.8  445.53
  4871.3  445.06 4938.55443.7503  4950.8  443.62    4971  441.67  4978.4  442.81
  4985.1  441.27  4992.5  441.87  4995.9  440.31  4996.4  439.51  5002.8  440.31
  5013.5  442.96  5020.3  441.16  5021.8  441.69  5027.7  443.75 5037.14  443.75
  5041.9  445.03  5048.7  444.34  5068.4  446.89  5126.9  448.85  5359.8  451.46
  5488.6  453.27  5638.3  457.07  5722.1  458.97  5779.1  461.87  5896.9  464.52
#Mann= 11 ,-1 , 0
  4221.4      .1       0  4690.7     .08       0  4720.7      .1       0
  4820.8     .05       0  4871.3      .1       0  4950.8     .08       0
  4995.9     .07       0  5002.8     .08       0  5021.8      .1       0
  5359.8     .05       0  5638.3      .1       0
Bank Sta=4938.55,5037.14
XS Rating Curve= 0 ,0
Exp/Cntr=0.3,0.1

Type RM Length L Ch R = 1 ,20885   ,464,464,464
BEGIN DESCRIPTION:
Mustang Creek 38.0
END DESCRIPTION:
XS GIS Cut Line= 3
      2012214.66     13431790.93        2012425.       13431275.
      2012925.02     13430474.96
#Sta/Elev= 30
  4438.3  455.87  4451.3   455.2  4480.7  455.15  4528.8  453.74  4587.7  453.33
  4606.3  452.45  4611.7  452.83  4641.2  452.03  4671.5  450.48  4694.7  450.38
  4801.6  447.03  4919.9  444.23  4951.3  442.93  4956.4442.0612  4980.7  440.39
  4986.1  439.21  5003.1  438.97  5005.5  438.17    5006  437.37    5012  437.37
  5012.5  438.17  5024.3  438.63 5048.31442.0617  5089.8  443.17  5184.1  443.66
  5264.9   446.1  5380.5  448.23  5480.7   448.1  5684.7  450.24  5938.9  457.22
#Mann= 3 ,-1 , 0
  4438.3      .1       0  5005.5     .07       0  5012.5      .1       0
Bank Sta=4956.4,5048.31
XS Rating Curve= 0 ,0
Exp/Cntr=0.3,0.1

Type RM Length L Ch R = 1 ,20421   ,204,204,204
BEGIN DESCRIPTION:
Mustang Creek 37.0
END DESCRIPTION:
XS GIS Cut Line= 3
      2012363.96      13431870.8        2012775.       13431525.
      2013249.38     13430454.12
#Sta/Elev= 30
  4458.1  459.13  4473.4  459.01  4512.1  458.41  4590.1   455.6  4618.7  453.99
  4661.7  453.16  4733.2  449.99  4803.4   445.8  4867.2  442.91 4935.94440.6337
  4967.3  439.89  4981.6  438.32  4988.5  436.35    4989  435.55    4995  435.55
  4995.5  436.35  5004.2  436.52 5038.92440.6336  5071.8  440.85    5126  442.98
  5192.1  444.52  5282.1  444.72  5334.3  445.56  5465.6  446.28  5497.1  446.09
  5662.4  447.58  5821.7  451.66    5914  453.15  6117.5  459.36  6166.5  460.27
#Mann= 4 ,-1 , 0
  4458.1     .05       0  4473.4      .1       0  4988.5     .07       0
  4995.5      .1       0
Bank Sta=4935.94,5038.92
XS Rating Curve= 0 ,0
Exp/Cntr=0.3,0.1

Type RM Length L Ch R = 1 ,20217   ,421,421,421
BEGIN DESCRIPTION:
Mustang Creek 36.0
END DESCRIPTION:
XS GIS Cut Line= 3
       2012596.6     13432110.38      2013030.63     13431506.22
      2013311.26     13430678.18
#Sta/Elev= 30
  4455.4  458.67  4500.3  457.65  4529.8  457.66  4565.4  456.11  4594.8  455.79
  4615.7  454.47    4659  454.05  4781.4  448.99  4844.1  445.11  4923.9  441.12
 4959.24440.0254  4988.9  438.45  5012.6  435.54  5013.1  434.74  5019.1  434.74
  5019.7  435.54  5039.3  438.25  5045.4  439.59 5051.53440.0255  5139.2  440.98
  5196.4  442.54  5353.4  443.58  5479.1  445.38  5573.3  445.29  5604.7  445.76
  5636.1  445.27  5749.6  446.32  5844.7   448.5  5887.5  448.87  6073.6  454.06
#Mann= 3 ,-1 , 0
  4455.4      .1       0  5012.6     .07       0  5019.7      .1       0
Bank Sta=4959.24,5051.53
XS Rating Curve= 0 ,0
Exp/Cntr=0.3,0.1

Type RM Length L Ch R = 1 ,19796   ,574,574,574
BEGIN DESCRIPTION:
Mustang Creek 35.0
END DESCRIPTION:
XS GIS Cut Line= 3
        2012775.     13432574.99      2013294.51     13431766.64
       2013572.3     13430881.19
#Sta/Elev= 30
  4131.7  452.24  4175.6   451.9  4217.9   450.9  4269.4  450.98  4311.7  450.16
  4357.2   450.2  4420.7  449.02  4464.5  448.98  4493.3  447.05    4566  447.31
 4958.48438.7191  4989.1  434.39  4989.6  433.59  4995.7  433.59  4996.2  434.39
    5023  437.59  5044.2   438.7  5071.2  438.17 5119.89438.7186  5175.3  439.72
  5245.4  440.04  5366.8  442.09  5534.5  443.45  5555.5  444.16  5639.3   444.2
  5660.3   444.8  5691.7  444.64  5765.1  445.64  5901.3  447.87  6020.6  451.11
#Mann= 3 ,-1 , 0
  4131.7      .1       0  4989.1     .07       0  4996.2      .1       0
Bank Sta=4958.48,5119.89
XS Rating Curve= 0 ,0
Exp/Cntr=0.3,0.1

Type RM Length L Ch R = 1 ,19222   ,515,515,515
BEGIN DESCRIPTION:
Mustang Creek 34.0
END DESCRIPTION:
XS GIS Cut Line= 3
      2013125.01     13432774.99      2013742.43      13431933.3
      2013943.83     13431082.58
#Sta/Elev= 30
  3941.9  452.67  4076.7  448.82  4256.4  444.55  4457.1  441.45  4528.1  441.33
  4663.9  439.18  4699.4  436.91  4714.1  437.14  4722.5  438.26 4748.08436.7952
  4793.6  437.24  4814.4  436.16  4843.7  436.96  4864.6  435.98  4879.2  436.71
    4944  436.64  4950.2  435.41  4971.3  434.68  4983.7  432.85  4990.6  432.79
  4991.2  431.99  4997.4  431.99  4997.9  432.79  5025.1  436.11 5041.41436.7951
  5158.7  439.37  5235.7  439.85  5362.5  444.24  5452.2  446.04    5860  446.74
#Mann= 4 ,-1 , 0
  3941.9     .05       0  4076.7      .1       0  4990.6     .07       0
  4997.9      .1       0
Bank Sta=4748.08,5041.41
XS Rating Curve= 0 ,0
Exp/Cntr=0.3,0.1

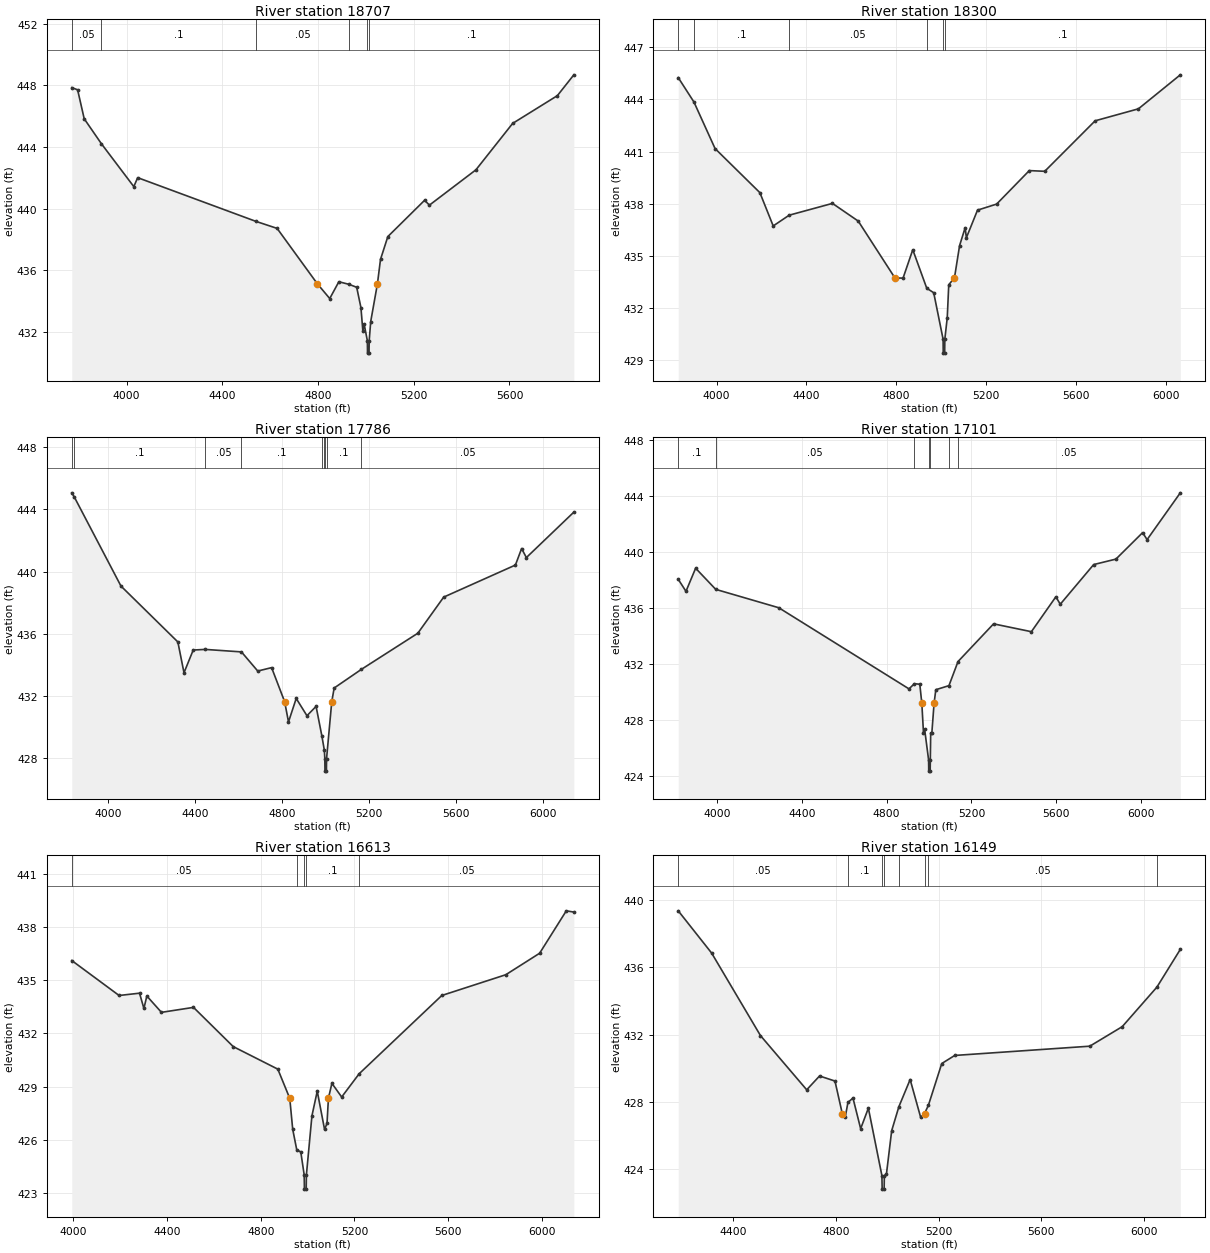
Type RM Length L Ch R = 1 ,18707   ,407,407,407
BEGIN DESCRIPTION:
Mustang Creek 33.0
END DESCRIPTION:
XS GIS Cut Line= 3
      2013617.42     13433009.71       2014183.4     13431964.55
        2014375.     13431075.02
#Sta/Elev= 30
  3770.5  447.85  3794.9  447.71  3822.5  445.83  3894.4  444.21  4029.8  441.43
    4046  442.01  4539.3  439.18  4628.8  438.72 4797.05435.1257  4848.7  434.17
  4886.8  435.26  4929.6  435.09  4961.4   434.9  4979.1  433.58  4987.3  432.04
  4992.4  432.52    5006  431.43  5006.6  430.63    5013  430.63  5013.6  431.43
    5020  432.68 5048.06435.1251  5060.9  436.71  5091.6  438.19    5245  440.54
  5265.5  440.23  5459.8  442.52  5613.3  445.53  5800.2  447.33    5869  448.68
#Mann= 6 ,-1 , 0
  3770.5     .05       0  3894.4      .1       0  4539.3     .05       0
  4929.6      .1       0    5006     .07       0  5013.6      .1       0
Bank Sta=4797.05,5048.06
XS Rating Curve= 0 ,0
Exp/Cntr=0.3,0.1

Type RM Length L Ch R = 1 ,18300   ,514,514,514
BEGIN DESCRIPTION:
Mustang Creek 32.0
END DESCRIPTION:
XS GIS Cut Line= 3
      2013940.37     13433124.24      2014468.13      13432183.3
      2014877.83     13431100.03
#Sta/Elev= 30
  3828.8  445.26  3898.9  443.85  3992.9  441.17  4192.5  438.63  4251.9  436.71
  4323.1  437.33  4515.9  438.01  4630.8  436.99 4793.81433.7229  4830.4   433.7
  4873.8  435.34  4936.1  433.12  4967.1  432.86  5008.9  430.18  5009.5  429.38
  5015.9  429.38  5016.6  430.18  5027.4  431.42  5034.1  433.32 5059.56433.7227
  5082.4  435.58  5107.2  436.61  5112.6  436.03  5162.2  437.62  5247.4  437.97
  5392.9   439.9  5461.8  439.86  5686.3  442.77  5879.1  443.46  6065.8  445.42
#Mann= 6 ,-1 , 0
  3828.8     .05       0  3898.9      .1       0  4323.1     .05       0
  4936.1      .1       0  5008.9     .07       0  5016.6      .1       0
Bank Sta=4793.81,5059.56
XS Rating Curve= 0 ,0
Exp/Cntr=0.3,0.1

Type RM Length L Ch R = 1 ,17786   ,685,685,685
BEGIN DESCRIPTION:
Mustang Creek 31.0
END DESCRIPTION:
XS GIS Cut Line= 3
      2014074.98     13433225.02      2014839.65     13432446.15
        2015175.     13431275.01
#Sta/Elev= 30
  3833.5  445.06  3845.2  444.79  4059.8  439.07  4321.5  435.48  4349.8   433.5
  4392.2  434.96  4447.2     435  4614.1  434.84  4689.1  433.61  4752.8  433.83
 4812.89431.6363  4830.5  430.34    4866  431.85  4915.4  430.74  4957.4  431.34
  4984.3  429.42  4995.6  428.51  4997.6  427.98  4998.3  427.18  5004.9  427.18
  5005.6  427.98 5029.49431.6365  5040.6  432.52    5166  433.72  5425.5  436.04
  5544.5  438.36  5874.4  440.42  5902.9  441.48  5924.8   440.9  6143.2  443.82
#Mann= 9 ,-1 , 0
  3833.5     .05       0  3845.2      .1       0  4447.2     .05       0
  4614.1      .1       0  4984.3     .12       0  4995.6      .1       0
  4997.6     .07       0  5005.6      .1       0    5166     .05       0
Bank Sta=4812.89,5029.49
XS Rating Curve= 0 ,0
Exp/Cntr=0.3,0.1

Type RM Length L Ch R = 1 ,17101   ,488,488,488
BEGIN DESCRIPTION:
Mustang Creek 30.0
END DESCRIPTION:
XS GIS Cut Line= 3
      2014714.63     13433603.49        2015225.       13432525.
      2015579.23     13431405.56
#Sta/Elev= 30
  3817.4  438.07  3853.9  437.21  3899.4  438.86  3994.3  437.35  4291.4  436.04
  4905.4  430.25    4931  430.62  4956.4  430.58 4965.94429.2116  4973.7  427.13
  4979.2  427.36  4997.9  425.18  4998.5  424.38  5005.3  424.38    5006  425.18
  5007.8  427.11  5013.2  427.11 5023.65429.2104  5031.9  430.19  5093.8  430.48
  5136.6   432.2  5304.2  434.89  5482.5  434.33  5597.9  436.82  5618.7  436.29
  5776.2  439.12  5881.1  439.51    6007   441.4    6028   440.9  6184.7  444.24
#Mann= 7 ,-1 , 0
  3817.4      .1       0  3994.3     .05       0    4931     .07       0
  4997.9     .07       0    5006     .07       0  5093.8      .1       0
  5136.6     .05       0
Bank Sta=4965.94,5023.65
XS Rating Curve= 0 ,0
Exp/Cntr=0.3,0.1

Type RM Length L Ch R = 1 ,16613   ,464,464,464
BEGIN DESCRIPTION:
Mustang Creek 29.0
END DESCRIPTION:
XS GIS Cut Line= 3
      2015256.33     13433745.78        2015575.       13432825.
      2015902.15     13431704.14
#Sta/Elev= 30
  3993.9   436.1  4195.8  434.13    4283  434.26  4301.6   433.4  4314.2   434.1
  4376.5  433.18  4513.2  433.46  4682.8  431.25    4873  429.98 4923.91428.3344
  4936.5  426.59    4954  425.42  4970.9  425.32  4985.5  424.02  4986.4  423.22
    4994  423.22  4994.9  424.02  5018.5  427.35  5041.2  428.74  5072.4  426.58
  5082.9  426.93 5088.81428.3346  5103.7  429.18  5145.4  428.41    5220  429.72
  5572.5  434.13  5845.6   435.3  5989.9  436.51  6103.7   438.9  6135.9  438.83
#Mann= 5 ,-1 , 0
  3993.9     .05       0    4954      .1       0  4985.5     .07       0
  4994.9      .1       0    5220     .05       0
Bank Sta=4923.91,5088.81
XS Rating Curve= 0 ,0
Exp/Cntr=0.3,0.1

Type RM Length L Ch R = 1 ,16149   ,465,465,465
BEGIN DESCRIPTION:
Mustang Creek 28.0
END DESCRIPTION:
XS GIS Cut Line= 3
        2015925.     13433775.04        2015975.       13432975.
      2016242.44     13431849.95
#Sta/Elev= 30
  4184.9  439.35  4315.2  436.84  4505.6  431.94  4685.9  428.72    4736  429.54
  4796.1  429.24 4824.66 427.307  4836.2   427.1  4846.7  427.97  4866.3  428.23
  4896.3  426.41  4926.4  427.63  4979.2  423.62  4980.2  422.82  4987.8  422.82
  4988.7  423.62  4996.8  423.71  5017.3  426.29  5045.2  427.71  5089.3  429.33
  5130.4  427.08  5145.4 427.307  5145.8  427.32  5160.5   427.8  5212.6  430.28
  5263.2  430.76  5789.9  431.31  5916.4  432.47  6051.7  434.82  6142.9  437.06
#Mann= 8 ,-1 , 0
  4184.9     .05       0  4846.7      .1       0  4979.2     .07       0
  4988.7      .1       0  5045.2     .07       0  5145.8      .1       0
  5160.5     .05       0  6051.7     .08       0
Bank Sta=4824.66,5145.4
XS Rating Curve= 0 ,0
Exp/Cntr=0.3,0.1