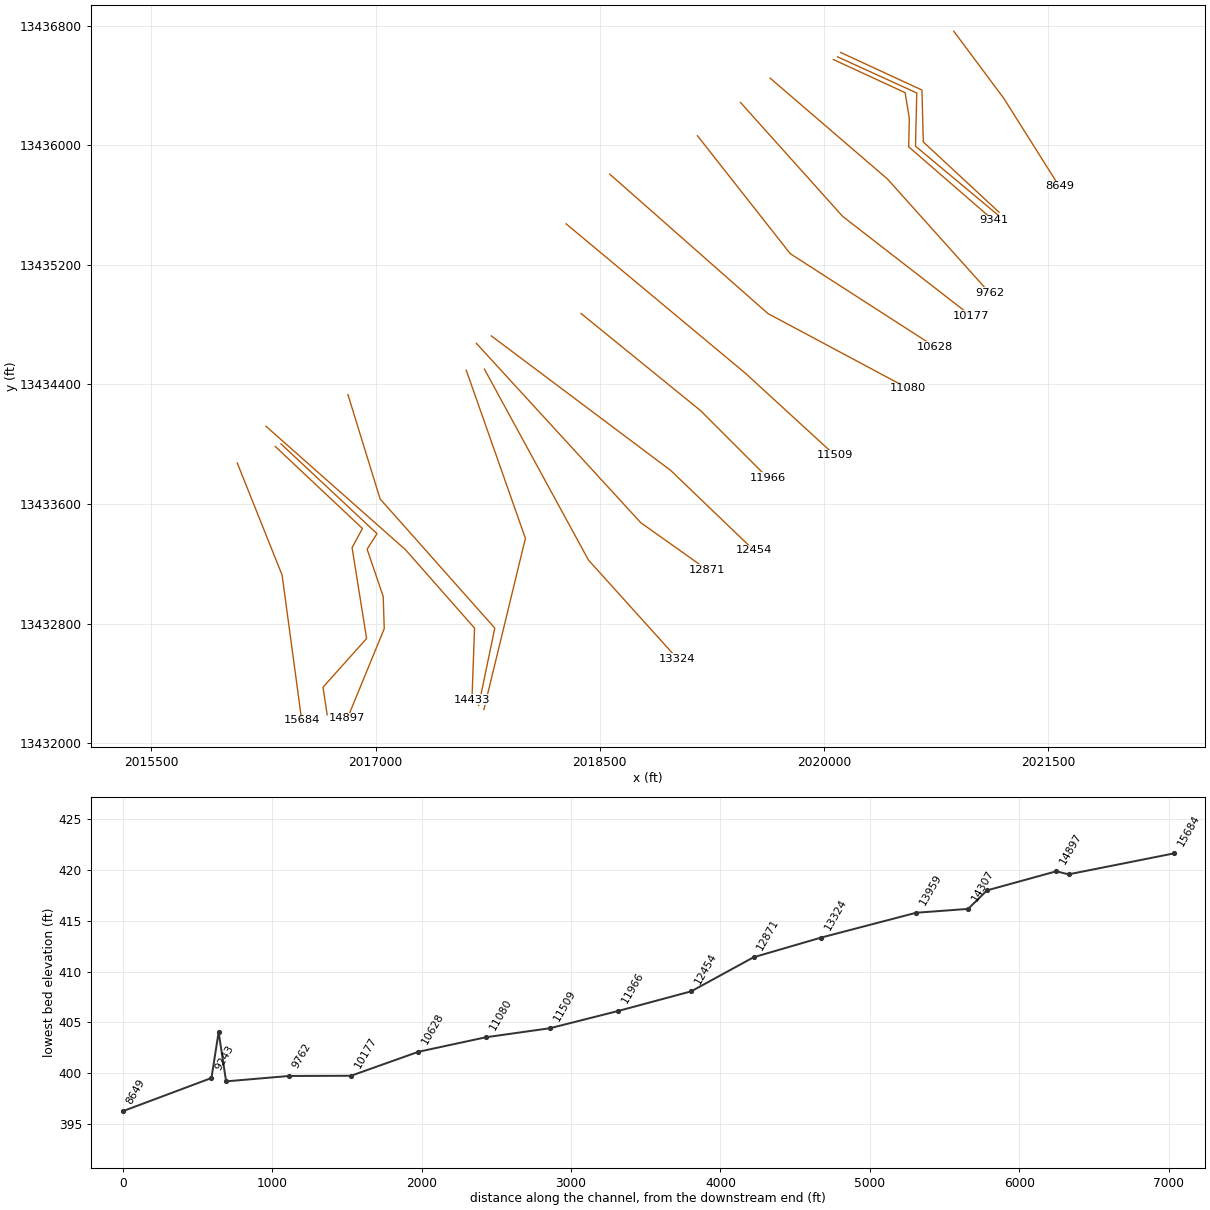
HEC-RAS study Mustang Creek.prj: Mustang Creek Base Level Engineering

--- Mustang Creek.g01 (geometry) --- (continued)

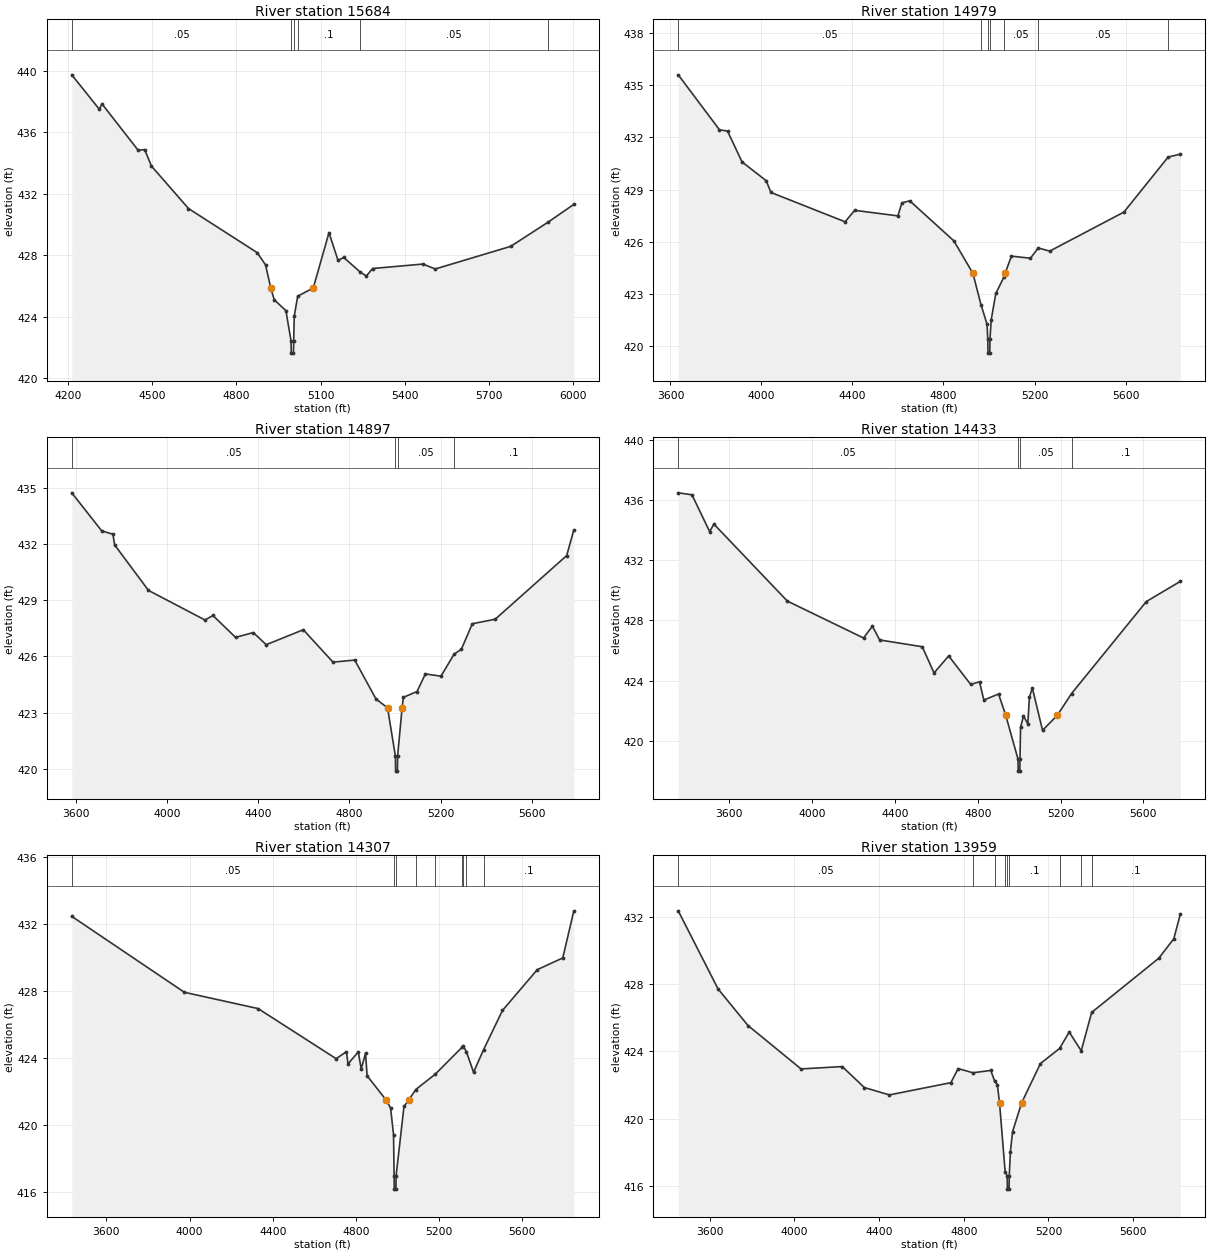
Type RM Length L Ch R = 1 ,15684   ,705,705,705
BEGIN DESCRIPTION:
Mustang Creek 27.0
END DESCRIPTION:
XS GIS Cut Line= 3
      2016075.01     13433874.97        2016375.       13433125.
      2016506.32     13432152.06
#Sta/Elev= 30
  4213.3  439.72  4311.5  437.48    4321  437.83  4450.2  434.81  4473.1  434.86
  4497.3  433.79  4629.3  431.03  4874.3  428.16  4903.9  427.37 4922.53425.8656
  4934.9   425.1  4976.6  424.39  4994.8  422.43  4995.7  421.63  5003.4  421.63
  5004.3  422.43  5006.2  424.02  5018.5  425.33 5074.08425.8651  5130.1  429.46
  5162.3  427.66  5182.5  427.85  5240.7  426.91  5263.2  426.64  5285.6  427.13
    5465  427.42  5508.7   427.1  5777.8  428.57  5910.8  430.14  6002.8   431.3
#Mann= 6 ,-1 , 0
  4213.3     .05       0  4994.8     .03       0  5004.3     .05       0
  5018.5      .1       0  5240.7     .05       0  5910.8     .08       0
Bank Sta=4922.53,5074.08
XS Rating Curve= 0 ,0
Exp/Cntr=0.3,0.1

Type RM Length L Ch R = 1 ,14979   ,82,82,82
BEGIN DESCRIPTION:
Mapping XS 6f7e2a1a
END DESCRIPTION:
XS GIS Cut Line= 6
      2016329.21     13433985.41      2016912.57     13433436.78
      2016843.13      13433308.3      2016940.35     13432700.67
      2016648.68     13432374.28      2016676.45     13432190.29
#Sta/Elev= 30
  3634.3  435.61  3815.6  432.44  3850.8  432.37  3914.7  430.59  4020.7  429.51
  4041.8  428.83  4367.5  427.14    4410   427.8  4599.6  427.48  4617.4  428.23
  4651.6  428.35  4845.7  426.04 4929.26424.1677  4964.9  422.36  4991.5  421.23
  4994.7  420.37  4995.7  419.57  5003.4  419.57  5004.3  420.37  5009.7  421.49
    5030  423.01  5065.5  423.95 5070.89424.1681  5098.5  425.16  5182.2  425.04
  5216.5  425.63    5267  425.45  5593.1   427.7  5787.3  430.87  5840.8  431.04
#Mann= 7 ,-1 , 0
  3634.3     .05       0  4964.9      .1       0  4994.7     .07       0
  5004.3      .1       0  5065.5     .05       0  5216.5     .05       0
  5787.3      .1       0
Bank Sta=4929.26,5070.89
XS Rating Curve= 0 ,0
Exp/Cntr=0.3,0.1

Type RM Length L Ch R = 1 ,14897   ,464,464,464
BEGIN DESCRIPTION:
Mapping XS 53cebff0
END DESCRIPTION:
XS GIS Cut Line= 6
      2016367.46     13434002.72      2017009.79     13433402.05
      2016943.82     13433297.89      2017051.46     13432981.92
       2017058.4     13432766.64      2016811.88     13432165.96
#Sta/Elev= 30
  3582.2  434.73  3713.4   432.7  3762.8  432.52  3770.1  431.95  3918.6  429.52
  4166.3  427.94  4201.4  428.18  4300.6  427.01  4378.3  427.27  4434.9  426.62
  4597.6  427.42  4727.7  425.69  4823.2   425.8  4916.4  423.72  4967.1423.2484
  5001.4  420.67  5002.4  419.87  5010.2  419.87  5011.1  420.67 5030.85423.2487
  5036.3  423.81  5096.3  424.12    5133  425.06  5201.3  424.94  5258.5  426.11
  5290.9  426.38  5338.8  427.74  5439.1  427.98  5752.6  431.38    5784  432.75
#Mann= 4 ,-1 , 0
  3582.2     .05       0  5001.4     .03       0  5011.1     .05       0
  5258.5      .1       0
Bank Sta=4967.1,5030.85
XS Rating Curve= 0 ,0
Exp/Cntr=0.3,0.1

Type RM Length L Ch R = 1 ,14433   ,126,126,126
BEGIN DESCRIPTION:
Mapping XS 69529a88
END DESCRIPTION:
XS GIS Cut Line= 4
      2016266.77     13434120.78      2017200.76     13433294.42
      2017662.57     13432770.11      2017645.21     13432290.89
#Sta/Elev= 30
  3353.3  436.47  3419.6  436.34  3504.9   433.9  3525.8  434.39  3880.5  429.28
  4248.5  426.83  4291.2  427.62  4326.3   426.7  4532.1  426.25    4589  424.51
  4659.7  425.64  4765.9  423.75  4808.6  423.92  4829.5  422.71  4900.6  423.11
 4935.14421.7039  4994.5  418.79  4995.5  417.99  5003.3  417.99  5004.2  418.79
  5006.9   420.9  5021.1  421.65    5042  421.13  5049.6   422.9  5063.8  423.51
  5113.1   420.7  5184.9421.7036  5253.1  423.14  5614.4  429.25  5778.6  430.59
#Mann= 4 ,-1 , 0
  3353.3     .05       0  4994.5     .04       0  5004.2     .05       0
  5253.1      .1       0
Bank Sta=4935.14,5184.9
XS Rating Curve= 0 ,0
Exp/Cntr=0.3,0.1

Type RM Length L Ch R = 1 ,14307   ,348,348,348
BEGIN DESCRIPTION:
Mustang Creek 26.0
END DESCRIPTION:
XS GIS Cut Line= 4
      2016815.34     13434332.65      2017030.63     13433634.69
      2017797.99     13432770.11      2017690.36     13432252.79
#Sta/Elev= 30
  3433.5  432.44  3975.2  427.91  4329.6  426.94  4705.1  423.95  4754.5  424.37
    4762  423.64  4811.4  424.35  4825.6  423.35  4846.5  424.27    4854  422.93
    4945421.4914  4966.9  421.01  4981.1  419.42  4983.8  416.97  4984.8  416.17
  4992.6  416.17  4993.5  416.97  5031.3   421.1 5054.79421.4916  5087.9  422.11
  5182.1  423.03  5310.4  424.63  5315.8  424.73  5331.3  424.37    5366  423.14
  5413.8  424.48  5505.1  426.83  5672.4  429.26    5795  429.96  5848.3  432.77
#Mann= 9 ,-1 , 0
  3433.5     .05       0  4983.8     .04       0  4993.5     .05       0
  5087.9      .1       0  5182.1     .08       0  5310.4     .05       0
  5315.8     .08       0  5331.3     .05       0  5413.8      .1       0
Bank Sta=4945,5054.79
XS Rating Curve= 0 ,0
Exp/Cntr=0.3,0.1

Type RM Length L Ch R = 1 ,13959   ,635,635,635
BEGIN DESCRIPTION:
Mustang Creek 25.0
END DESCRIPTION:
XS GIS Cut Line= 3
      2017607.02      13434495.8      2018002.85      13433370.8
        2017725.     13432225.01
#Sta/Elev= 30
  3451.1  432.39  3639.2  427.73  3780.6  425.55  4031.1  422.96  4225.8   423.1
  4330.2  421.85  4448.4  421.41  4738.9  422.14  4773.1  422.98  4843.1  422.73
  4927.5  422.87  4945.4  422.24  4958.4  422.02 4968.74420.9449  4995.4  416.81
  5004.9  416.59  5005.9  415.79  5013.8  415.79  5014.7  416.59  5020.1  418.03
  5030.4  419.22  5073.4420.9447    5162  423.28  5252.3  424.18  5297.9  425.16
  5354.6  424.04    5404  426.33  5720.8  429.56  5791.8  430.72  5822.7  432.19
#Mann= 9 ,-1 , 0
  3451.1     .05       0  4843.1      .1       0  4945.4     .05       0
  4995.4      .1       0  5004.9     .07       0  5014.7      .1       0
  5252.3     .08       0  5354.6     .05       0    5404      .1       0
Bank Sta=4968.74,5073.4
XS Rating Curve= 0 ,0
Exp/Cntr=0.3,0.1

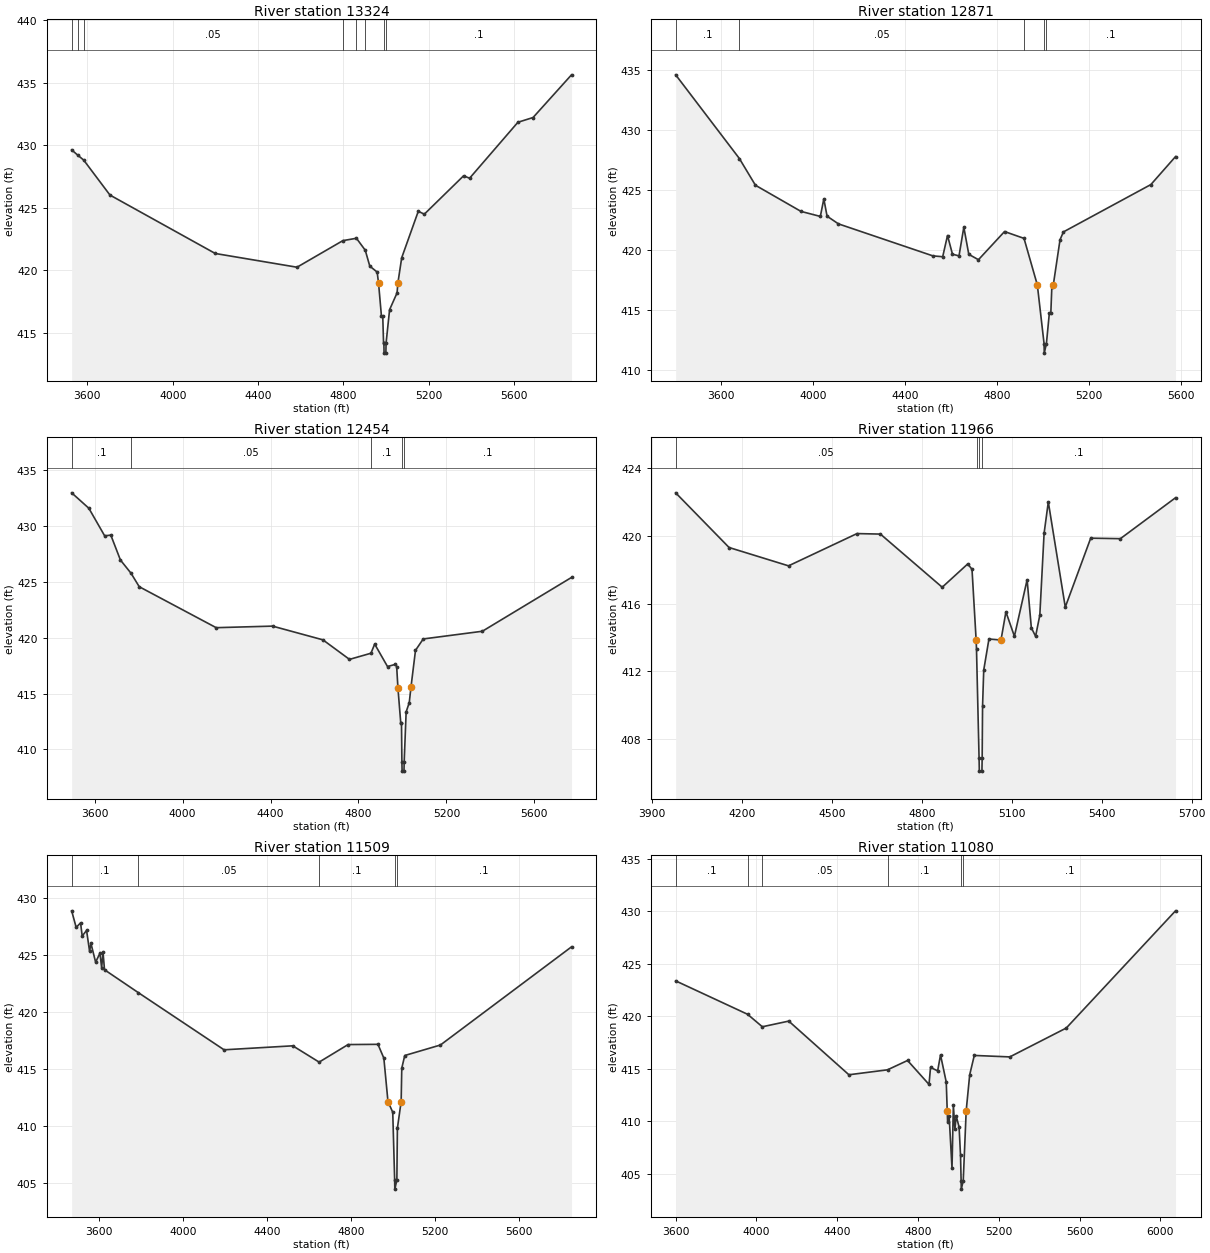
Type RM Length L Ch R = 1 ,13324   ,453,453,453
BEGIN DESCRIPTION:
Mustang Creek 24.0
END DESCRIPTION:
XS GIS Cut Line= 3
      2017728.55     13434502.73        2018425.       13433225.
       2019020.1     13432565.37
#Sta/Elev= 30
  3526.2  429.63  3554.5  429.21  3582.7  428.81  3705.8  426.01  4199.6  421.33
  4582.8  420.23  4797.8  422.36  4861.4  422.55  4902.8  421.59    4924  420.32
  4958.6  419.84 4965.13418.9548  4978.6  416.32  4984.8  416.32  4988.5  414.19
  4990.1  414.15    4991  413.35  4999.4  413.35  5000.4  414.15  5016.9  416.83
    5052  418.18 5055.63418.9544  5073.7  420.99  5151.4  424.71  5179.8  424.48
  5363.7  427.55  5392.1  427.36  5618.5  431.84  5689.5  432.22  5869.8  435.64
#Mann= 8 ,-1 , 0
  3526.2     .05       0  3554.5      .1       0  3582.7     .05       0
  4797.8     .08       0  4861.4     .05       0  4902.8      .1       0
  4990.1     .07       0  5000.4      .1       0
Bank Sta=4965.13,5055.63
XS Rating Curve= 0 ,0
Exp/Cntr=0.3,0.1

Type RM Length L Ch R = 1 ,12871   ,417,417,417
BEGIN DESCRIPTION:
Mustang Creek 23.0
END DESCRIPTION:
XS GIS Cut Line= 3
      2017675.02     13434674.98        2018775.       13433475.
      2019219.64     13433159.77
#Sta/Elev= 30
  3403.1  434.62    3680  427.64  3749.9  425.41  3947.9  423.23    4032  422.81
  4047.1  424.27  4061.3  422.83  4110.6  422.19  4521.3  419.52  4563.9  419.45
  4584.8  421.22  4606.4  419.66  4634.8  419.52  4655.7  421.91  4677.3  419.65
  4719.3   419.2  4832.7  421.55  4917.4  420.98 4975.27417.0984  5004.5  412.21
  5005.4  411.41  5014.8  412.21  5027.6  414.77    5034  414.77  5038.3  416.92
 5044.72417.0992    5074  420.87  5088.8  421.52    5469  425.47    5576   427.8
#Mann= 5 ,-1 , 0
  3403.1      .1       0    3680     .05       0  4917.4      .1       0
  5004.5     .07       0  5014.8      .1       0
Bank Sta=4975.27,5044.72
XS Rating Curve= 0 ,0
Exp/Cntr=0.3,0.1

Type RM Length L Ch R = 1 ,12454   ,488,488,488
BEGIN DESCRIPTION:
Mustang Creek 22.0
END DESCRIPTION:
XS GIS Cut Line= 3
      2017775.02     13434724.98        2018975.       13433825.
      2019532.85     13433289.57
#Sta/Elev= 30
  3495.6  432.99  3573.7  431.61  3645.6  429.14  3673.7   429.2  3717.4  426.97
  3765.5  425.79  3802.9  424.58  4152.9  420.91  4409.1  421.05  4638.3  419.82
  4759.1  418.07  4856.7  418.62  4873.7  419.44    4932  417.43  4967.4  417.62
  4973.7  417.43 4979.25 415.551  4992.4  412.34  4995.6  412.34  4997.5  408.86
  4998.4  408.06  5006.9  408.06  5007.8  408.86  5016.8  413.37  5030.9  414.19
 5038.55415.5526  5059.3  418.88  5094.5   419.9  5363.4  420.59  5768.8  425.41
#Mann= 5 ,-1 , 0
  3495.6      .1       0  3765.5     .05       0  4856.7      .1       0
  4997.5     .07       0  5007.8      .1       0
Bank Sta=4979.25,5038.55
XS Rating Curve= 0 ,0
Exp/Cntr=0.3,0.1

Type RM Length L Ch R = 1 ,11966   ,457,457,457
BEGIN DESCRIPTION:
Mustang Creek 21.0
END DESCRIPTION:
XS GIS Cut Line= 3
      2018375.01     13434874.99        2019175.       13434225.
      2019625.03     13433774.97
#Sta/Elev= 30
    3979  422.52  4157.1   419.3  4355.4  418.22  4583.8  420.12  4661.9  420.09
    4868  416.96    4953  418.33  4967.4  418.02 4981.16413.8531  4982.4   413.3
  4990.9  406.93  4991.8  406.13  5000.5  406.13  5001.3  406.93  5002.6  409.96
  5006.5  412.08  5023.9  413.91  5064.1413.8521  5080.5  415.51  5108.8  414.07
  5151.2   417.4  5165.3  414.57  5179.5  414.07  5193.6  415.32  5207.8  420.13
  5221.9  421.98  5278.5  415.79  5363.3  419.85  5462.3  419.82  5646.2  422.23
#Mann= 4 ,-1 , 0
    3979     .05       0  4982.4      .1       0  4990.9     .07       0
  5001.3      .1       0
Bank Sta=4981.16,5064.1
XS Rating Curve= 0 ,0
Exp/Cntr=0.3,0.1

Type RM Length L Ch R = 1 ,11509   ,429,429,429
BEGIN DESCRIPTION:
Mustang Creek 20.0
END DESCRIPTION:
XS GIS Cut Line= 3
      2018275.04     13435474.97        2019475.       13434475.
      2020074.97     13433925.03
#Sta/Elev= 30
  3471.6  428.84    3493  427.39  3513.9  427.78  3521.7  426.63  3542.5  427.12
  3556.8  425.29  3563.3  425.98  3585.5  424.34  3606.3  425.13  3614.1  423.85
  3620.6  425.21  3627.8  423.67    3788  421.67    4196  416.65  4522.7     417
  4647.9  415.57  4785.6  417.11  4927.5  417.13  4955.5  415.92 4975.08 412.114
  4997.8  411.17  5006.9  405.23  5007.7  404.43  5017.4  405.23  5019.9  409.77
 5037.77  412.11  5040.7  415.04  5054.9  416.15  5224.4  417.07  5847.5  425.68
#Mann= 5 ,-1 , 0
  3471.6      .1       0    3788     .05       0  4647.9      .1       0
  5006.9     .07       0  5017.4      .1       0
Bank Sta=4975.08,5037.77
XS Rating Curve= 0 ,0
Exp/Cntr=0.3,0.1

Type RM Length L Ch R = 1 ,11080   ,452,452,452
BEGIN DESCRIPTION:
Mustang Creek 19.0
END DESCRIPTION:
XS GIS Cut Line= 3
      2018567.06     13435807.46        2019625.       13434875.
      2020563.65     13434373.39
#Sta/Elev= 30
  3600.2  423.37  3956.1  420.19  4029.2     419    4160  419.54  4457.8  414.43
  4648.9   414.9  4748.1  415.79  4854.4  413.51  4861.9  415.13  4897.1   414.8
  4911.3  416.32  4939.7  413.73 4944.51411.0236  4946.4  409.96    4954   410.5
  4968.2  405.52  4974.9  411.55  4982.4  409.25  4989.1  410.49  5003.3  409.45
  5010.4  406.75  5013.3  404.34  5014.2  403.54  5023.8  404.34 5038.48411.0264
  5055.8  414.43  5078.5  416.27  5254.3  416.13  5533.9  418.88  6074.7  430.04
#Mann= 6 ,-1 , 0
  3600.2      .1       0  3956.1     .08       0  4029.2     .05       0
  4648.9      .1       0  5013.3     .07       0  5023.8      .1       0
Bank Sta=4944.51,5038.48
XS Rating Curve= 0 ,0
Exp/Cntr=0.3,0.1

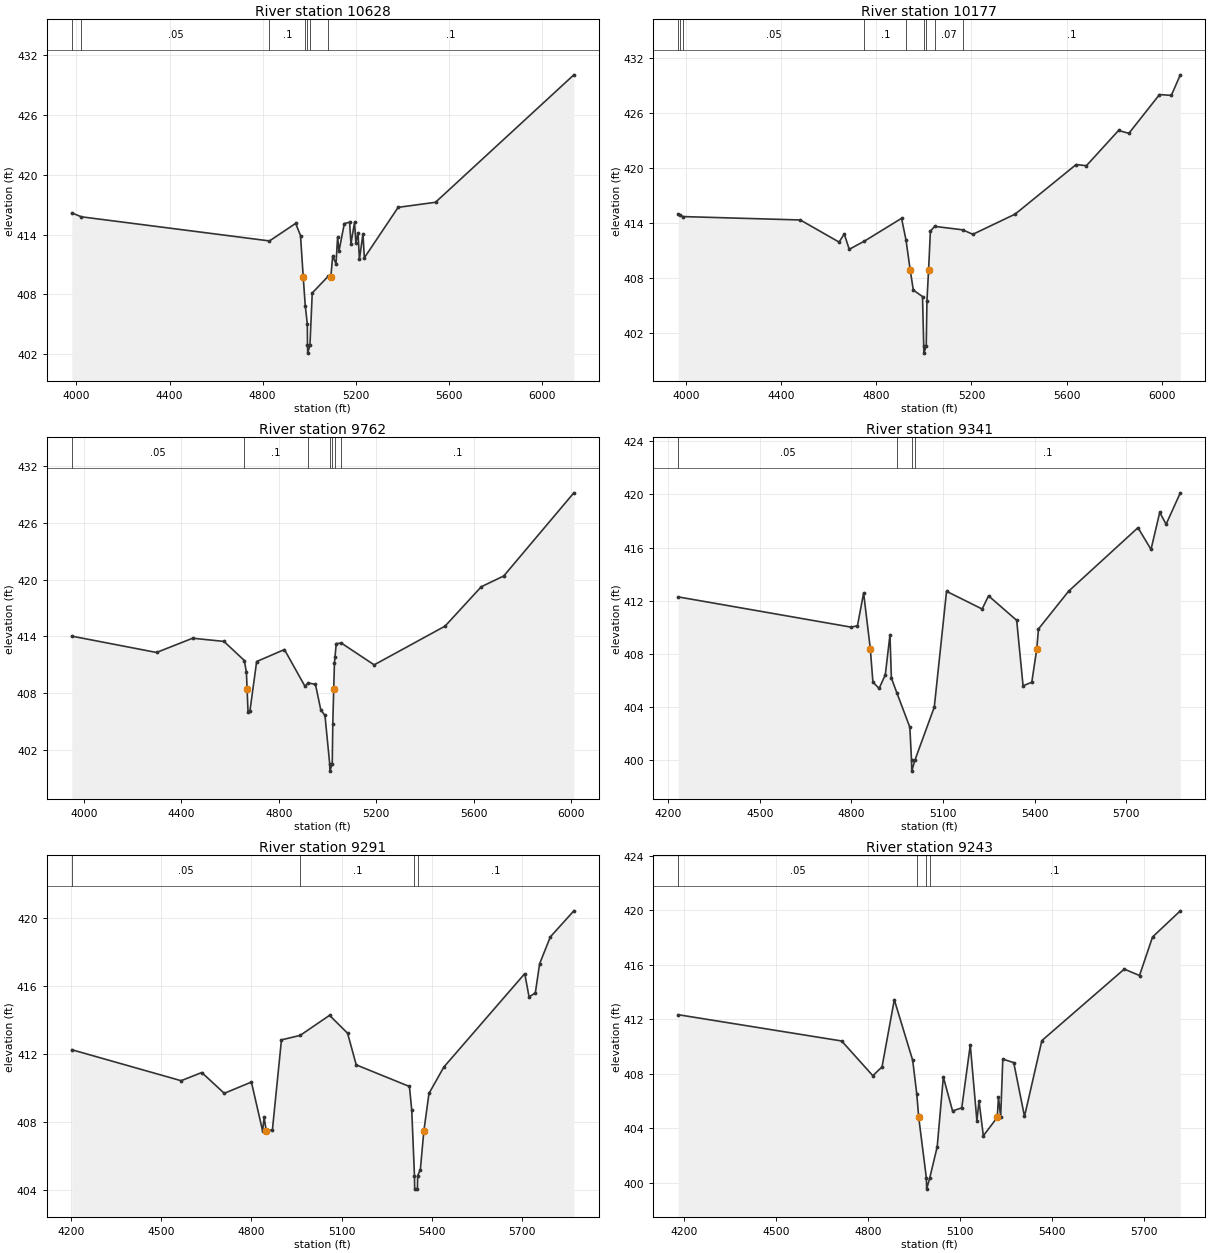
Type RM Length L Ch R = 1 ,10628   ,451,451,451
BEGIN DESCRIPTION:
Mustang Creek 18.0
END DESCRIPTION:
XS GIS Cut Line= 3
      2019153.91     13436064.36        2019775.       13435275.
      2020744.18     13434651.18
#Sta/Elev= 30
  3979.9  416.18  4021.5  415.79  4829.3  413.37  4941.8  415.13  4962.6  413.91
 4974.13409.7959    4983  406.87  4991.9  405.02  4992.6  402.91  4993.5  402.11
  5003.2  402.91    5013  408.15  5081.9  409.83 5093.03409.7951  5100.9  411.86
  5115.1  411.08    5122  413.75  5127.9  412.34  5150.8  415.11  5173.5  415.25
  5179.4   413.1  5194.6  415.22  5200.6  413.19  5209.8  414.18  5215.7  411.51
  5230.9  414.09  5236.9  411.68  5382.1  416.74  5542.6  417.25  6136.9  430.04
#Mann= 7 ,-1 , 0
  3979.9      .1       0  4021.5     .05       0  4829.3      .1       0
    4983     .12       0  4992.6     .07       0  5003.2     .12       0
  5081.9      .1       0
Bank Sta=4974.13,5093.03
XS Rating Curve= 0 ,0
Exp/Cntr=0.3,0.1

Type RM Length L Ch R = 1 ,10177   ,415,415,415
BEGIN DESCRIPTION:
Mustang Creek 17.0
END DESCRIPTION:
XS GIS Cut Line= 3
      2019442.07     13436286.62        2020125.       13435525.
      2020983.44     13434859.76
#Sta/Elev= 30
  3968.5  414.95  3974.9  414.87  3988.3  414.69  4481.2  414.32  4644.2   411.9
  4665.9  412.79  4686.8  411.11  4750.9  412.01  4906.6   414.5  4925.3  412.12
 4942.67408.8802    4956  406.65  4994.6  405.94  4999.7  400.55  5000.6  399.75
  5010.3  400.55  5013.2  405.48 5020.16408.8787  5027.7  413.09  5045.3  413.62
  5163.5  413.24    5206  412.75  5383.7  414.96  5639.7  420.38  5683.1  420.26
    5818  424.11  5861.5   423.8    5990  428.04  6039.8  427.95  6077.5   430.2
#Mann= 9 ,-1 , 0
  3968.5     .05       0  3974.9     .08       0  3988.3     .05       0
  4750.9      .1       0  4925.3     .12       0  4999.7     .07       0
  5010.3     .12       0  5045.3     .07       0  5163.5      .1       0
Bank Sta=4942.67,5020.16
XS Rating Curve= 0 ,0
Exp/Cntr=0.3,0.1

Type RM Length L Ch R = 1 ,9762    ,421,421,421
BEGIN DESCRIPTION:
Mustang Creek 16.0
END DESCRIPTION:
XS GIS Cut Line= 3
      2019639.97     13436449.82        2020425.       13435775.
      2021108.73     13435012.32
#Sta/Elev= 30
  3950.6  414.02  4298.3  412.29  4446.5   413.8  4574.9  413.46  4658.5  411.44
    4667  410.18 4669.73 408.451  4673.6     406  4681.3  406.08  4708.9  411.33
  4822.9   412.6  4907.4   408.7  4920.2  409.07  4950.2  408.91  4972.1  406.21
  4989.2  405.63  5008.5  400.53  5009.4  399.73  5019.1  400.53  5021.3  404.76
 5025.16408.4474    5028  411.16  5030.2  411.77  5035.5  413.23  5056.8  413.28
    5191  410.98  5481.8  415.08  5630.5  419.25  5722.6  420.39  6010.1  429.19
#Mann= 7 ,-1 , 0
  3950.6     .05       0  4658.5      .1       0  4920.2     .07       0
  5008.5     .07       0  5019.1     .07       0  5030.2     .12       0
  5056.8      .1       0
Bank Sta=4669.73,5025.16
XS Rating Curve= 0 ,0
Exp/Cntr=0.3,0.1

Type RM Length L Ch R = 1 ,9341    ,50,50,50
BEGIN DESCRIPTION:
Mapping XS 3e1eedd6
END DESCRIPTION:
XS GIS Cut Line= 5
       2020063.6     13436573.93      2020543.21     13436352.57
      2020571.42     13436181.13      2020567.08     13435990.16
      2021134.23     13435498.78
#Sta/Elev= 30
    4233  412.29  4798.6  410.02  4819.6  410.12  4839.8  412.58 4861.67408.4093
  4870.2  405.89  4890.5  405.41  4910.8  406.44  4926.1  409.45  4930.6   406.2
  4948.8  405.07  4991.1   402.5  4996.6     400  4997.4   399.2  5007.3     400
  5071.1  404.01  5111.2  412.71  5227.8  411.38  5248.7  412.37  5340.8  410.53
  5361.7  405.61  5390.2  405.88 5406.78408.4083  5412.1  409.88  5510.8  412.72
  5737.8  417.49  5780.5  415.86  5809.1  418.64  5829.9  417.75  5876.4  420.11
#Mann= 4 ,-1 , 0
    4233     .05       0  4948.8      .1       0  4996.6     .07       0
  5007.3      .1       0
Bank Sta=4861.67,5406.78
XS Rating Curve= 0 ,0
Exp/Cntr=0.3,0.1

Type RM Length L Ch R = 1 ,9291    ,48,48,48
BEGIN DESCRIPTION:
Mustang Creek 15.0
END DESCRIPTION:
XS GIS Cut Line= 4
      2020091.37     13436592.17      2020621.34      13436350.4
      2020612.66      13435994.5      2021175.01     13435524.99
#Sta/Elev= 30
  4201.8  412.24  4565.7  410.42  4634.5   410.9  4709.4  409.68  4799.7  410.34
    4837  407.47    4842  408.27 4849.37407.4373  4869.7  407.55  4899.7  412.82
  4961.8  413.08  5059.8  414.26  5119.8  413.21  5148.6  411.35  5325.7  410.08
  5333.4  408.69  5342.4  404.85  5343.2  404.05  5352.2  404.05  5353.1  404.85
    5362  405.19 5373.49407.4378  5390.7  409.67  5440.1  411.22  5709.5  416.71
  5723.9  415.34  5744.7  415.58    5759  417.29  5794.7  418.87  5872.9   420.4
#Mann= 4 ,-1 , 0
  4201.8     .05       0  4961.8      .1       0  5342.4     .07       0
  5353.1      .1       0
Bank Sta=4849.37,5373.49
XS Rating Curve= 0 ,0
Exp/Cntr=0.3,0.1

Type RM Length L Ch R = 1 ,9243    ,594,594,594
BEGIN DESCRIPTION:
Mapping XS 641747c8
END DESCRIPTION:
XS GIS Cut Line= 4
      2020111.39     13436621.66      2020656.06     13436369.94
      2020664.74     13436022.71       2021171.3     13435552.96
#Sta/Elev= 30
  4181.4  412.34  4714.7  410.41  4816.4  407.86  4846.4  408.51  4886.4  413.44
  4946.4  408.99  4959.7  406.52 4966.03404.8006  4991.1  400.33  4991.9  399.53
  5001.8  400.33  5026.4  402.64  5046.4  407.76  5076.5  405.27  5106.5   405.5
  5134.3  410.12  5155.9  404.54  5162.7  406.01  5176.9  403.45 5222.45   404.8
  5226.2   406.3  5233.5  404.85  5240.4  409.08  5276.1  408.82  5311.2  404.87
  5367.9  410.44  5636.7  415.69  5686.5  415.22    5729  418.05  5819.6  419.97
#Mann= 4 ,-1 , 0
  4181.4     .05       0  4959.7      .1       0  4991.1     .07       0
  5001.8      .1       0
Bank Sta=4966.03,5222.45
XS Rating Curve= 0 ,0
Exp/Cntr=0.3,0.1

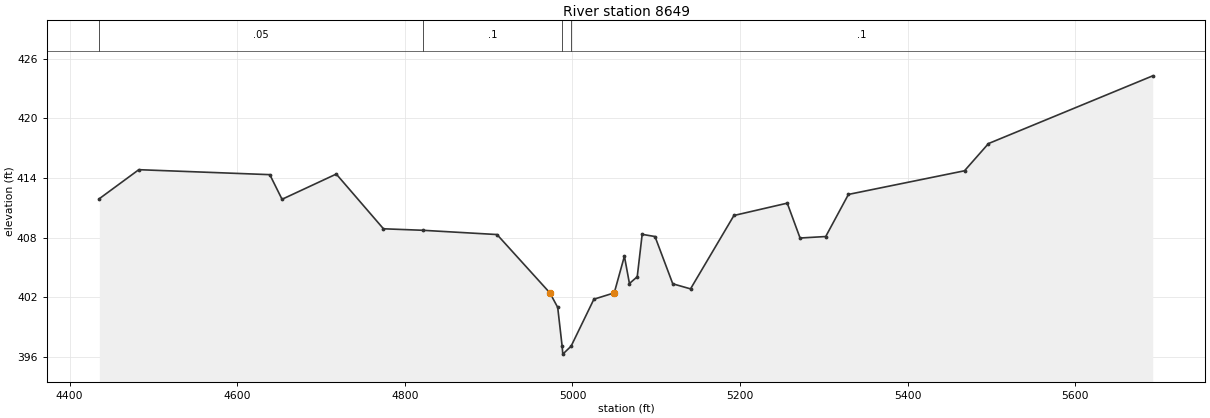
Type RM Length L Ch R = 1 ,8649    ,384,384,384
BEGIN DESCRIPTION:
Mustang Creek 14.0
END DESCRIPTION:
XS GIS Cut Line= 3
      2020868.76     13436763.56       2021203.8     13436313.95
      2021575.01     13435724.98
#Sta/Elev= 30
  4435.5  411.91  4482.6  414.83  4638.9  414.33  4653.5  411.85  4718.2  414.39
  4774.5  408.88  4821.1  408.73    4910   408.3 4973.06402.4286  4982.4  400.97
  4987.7  397.06  4988.5  396.26  4998.4  397.06  5025.6  401.79 5049.88402.4277
    5062  406.12    5068  403.37  5077.3  404.05  5083.2  408.32  5098.5   408.1
  5119.7  403.34  5140.9  402.83  5192.7  410.22  5256.3  411.46  5271.6  407.95
  5302.2   408.1  5329.3  412.34  5467.8  414.72  5496.4  417.46  5692.4  424.28
#Mann= 4 ,-1 , 0
  4435.5     .05       0  4821.1      .1       0  4987.7     .07       0
  4998.4      .1       0
Bank Sta=4973.06,5049.88
XS Rating Curve= 0 ,0
Exp/Cntr=0.3,0.1