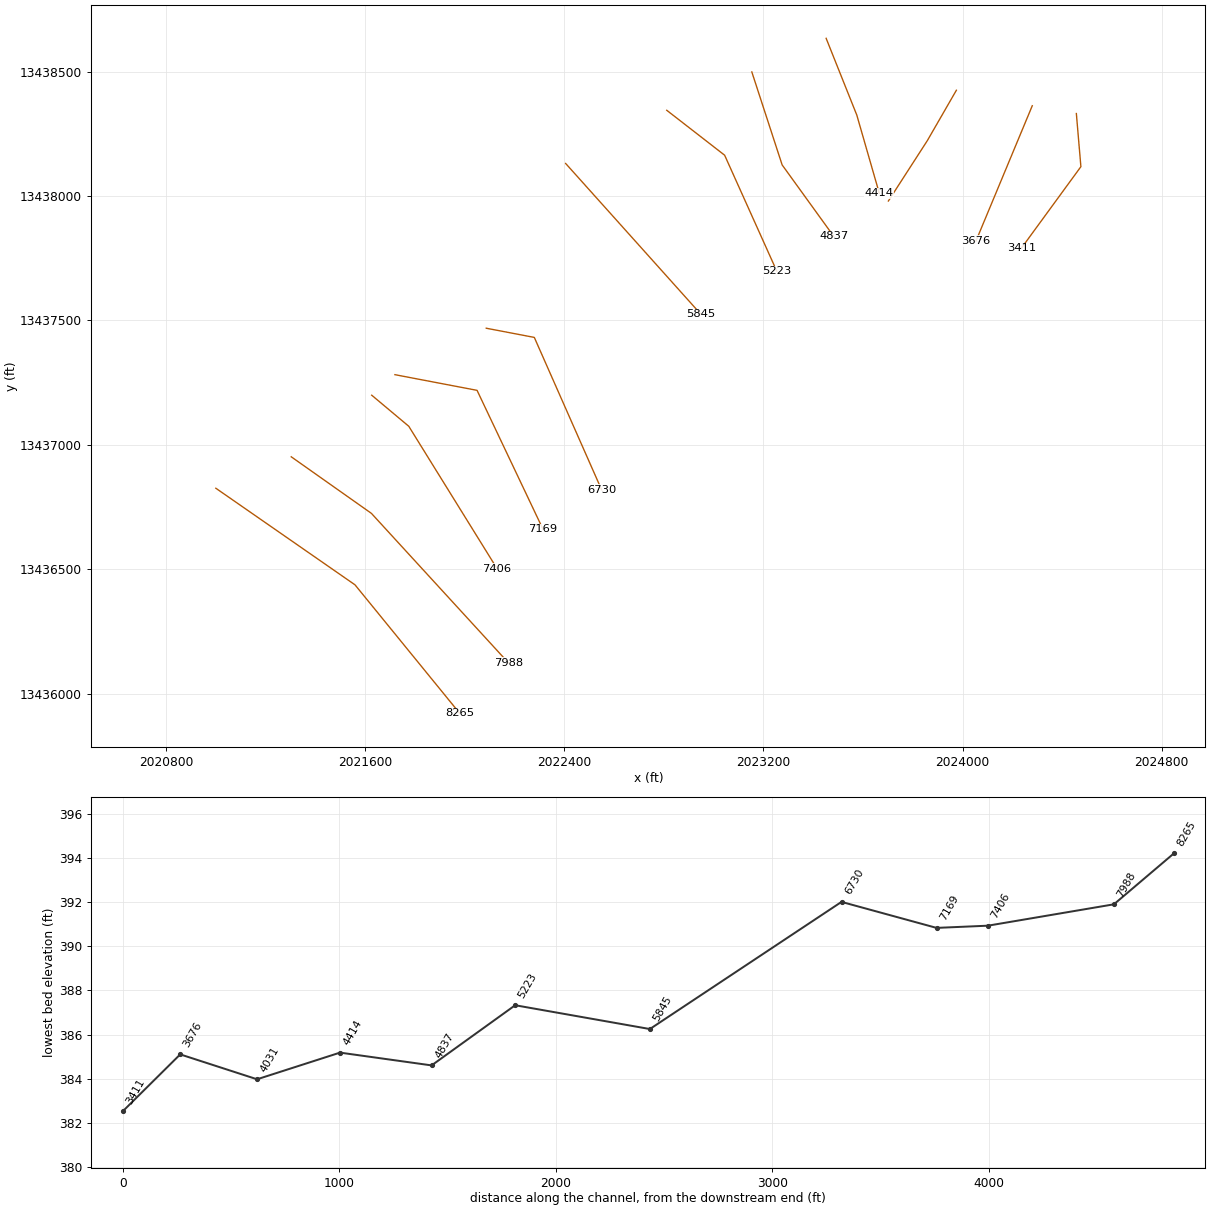
HEC-RAS study Mustang Creek.prj: Mustang Creek Base Level Engineering

--- Mustang Creek.g01 (geometry) --- (continued)

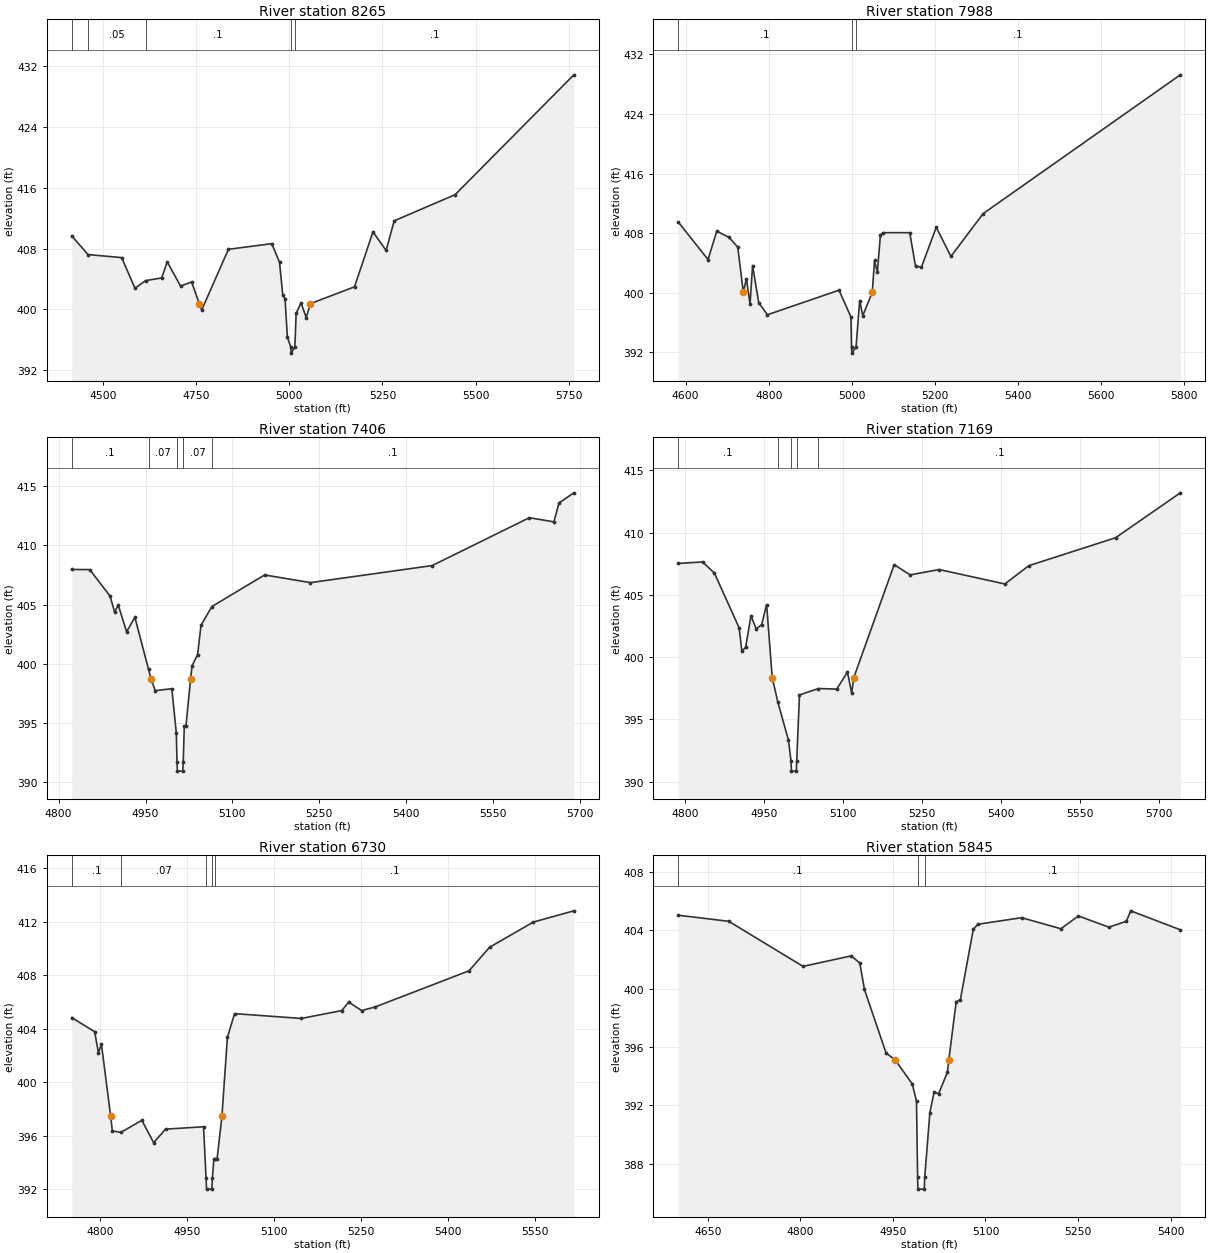
Type RM Length L Ch R = 1 ,8265    ,277,277,277
BEGIN DESCRIPTION:
Mustang Creek 13.0
END DESCRIPTION:
XS GIS Cut Line= 3
      2020999.79     13436826.11      2021558.84     13436438.08
      2021979.87     13435921.55
#Sta/Elev= 30
  4416.7  409.67  4460.3  407.21  4550.5  406.81  4586.3  402.76  4614.6  403.78
  4657.9  404.13  4672.8  406.25  4708.6  403.06  4738.3   403.6 4758.64400.7444
  4765.3  399.91  4836.9   407.9  4953.1  408.65    4974   406.2  4982.8  401.84
  4988.8  401.41  4995.2  396.28  5004.4  395.02  5005.2  394.22  5015.2  395.02
  5018.6  399.45  5031.7  400.84  5045.6   398.9 5057.01 400.743  5175.2  402.96
  5224.7   410.2  5259.9  407.76  5281.8  411.66  5445.2  415.11  5763.6   430.9
#Mann= 5 ,-1 , 0
  4416.7      .1       0  4460.3     .05       0  4614.6      .1       0
  5004.4     .07       0  5015.2      .1       0
Bank Sta=4758.64,5057.01
XS Rating Curve= 0 ,0
Exp/Cntr=0.3,0.1

Type RM Length L Ch R = 1 ,7988    ,582,582,582
BEGIN DESCRIPTION:
Mustang Creek 12.0
END DESCRIPTION:
XS GIS Cut Line= 3
      2021302.74     13436952.41        2021625.       13436725.
      2022175.03     13436124.97
#Sta/Elev= 30
  4582.2  409.51    4654  404.47  4674.9  408.29  4704.5  407.44  4725.4  406.15
 4738.83400.1016  4746.3   401.9    4755  398.49  4761.1  403.67  4775.9  398.69
  4796.8  397.06  4969.2  400.36  4997.9  396.76  4999.3  392.71  5000.1  391.91
  5010.1  392.71  5018.9  398.96  5026.3  396.93 5049.31400.0993  5054.6  404.36
  5061.4  402.76  5068.8  407.74  5075.6  408.08  5139.4  408.08  5153.3  403.58
  5167.5  403.45  5203.2  408.81  5238.4  404.89  5316.1  410.64  5790.6  429.27
#Mann= 3 ,-1 , 0
  4582.2      .1       0  4999.3     .07       0  5010.1      .1       0
Bank Sta=4738.83,5049.31
XS Rating Curve= 0 ,0
Exp/Cntr=0.3,0.1

Type RM Length L Ch R = 1 ,7406    ,237,237,237
BEGIN DESCRIPTION:
Mustang Creek 11.0
END DESCRIPTION:
XS GIS Cut Line= 3
      2021626.13     13437199.78        2021775.       13437075.
      2022129.59     13436503.17
#Sta/Elev= 30
  4822.6  407.96  4853.6  407.95  4888.7  405.72  4896.5  404.38    4903  404.94
  4917.3   402.7  4931.6  403.93  4955.2  399.52 4959.73398.6865  4966.8  397.73
  4995.4   397.9  5003.2  394.12  5004.3  391.74  5005.1  390.94  5014.3  390.94
  5015.1  391.74  5016.9  394.74  5019.8  394.74 5027.78398.6887  5030.4  399.83
  5039.9  400.78  5045.8  403.25  5064.5  404.83  5155.7   407.5  5234.8  406.85
  5445.1  408.29  5612.8  412.33  5655.3  411.98    5664  413.57  5689.7  414.43
#Mann= 5 ,-1 , 0
  4822.6      .1       0  4955.2     .07       0  5004.3     .07       0
  5015.1     .07       0  5064.5      .1       0
Bank Sta=4959.73,5027.78
XS Rating Curve= 0 ,0
Exp/Cntr=0.3,0.1

Type RM Length L Ch R = 1 ,7169    ,439,439,439
BEGIN DESCRIPTION:
Mustang Creek 10.0
END DESCRIPTION:
XS GIS Cut Line= 3
      2021719.39     13437282.27      2022049.29     13437219.33
      2022314.03     13436661.63
#Sta/Elev= 30
    4787  407.52  4833.4  407.64  4855.7  406.74  4902.7  402.34  4907.8  400.47
  4914.9  400.78  4925.1   403.3  4935.2  402.25  4945.4  402.61  4954.8  404.21
 4965.44398.3383  4976.1  396.39  4996.3  393.32  5001.1  391.64  5001.9  390.84
  5011.1  390.84  5011.9  391.64  5017.2  396.96  5053.1  397.47  5087.9  397.43
  5108.3  398.79  5116.3   397.1 5120.18398.3368    5197  407.42  5227.3   406.6
  5282.4  407.03  5407.1  405.87  5452.6  407.34  5617.2  409.58  5740.2  413.19
#Mann= 5 ,-1 , 0
    4787      .1       0  4976.1     .07       0  5001.1     .07       0
  5011.9     .07       0  5053.1      .1       0
Bank Sta=4965.44,5120.18
XS Rating Curve= 0 ,0
Exp/Cntr=0.3,0.1

Type RM Length L Ch R = 1 ,6730    ,885,885,885
BEGIN DESCRIPTION:
Mustang Creek 9.0
END DESCRIPTION:
XS GIS Cut Line= 3
       2022086.2     13437468.89      2022279.32       13437432.
      2022549.82     13436819.59
#Sta/Elev= 30
  4751.5  404.83    4791  403.78  4797.5  402.19  4802.6  402.87 4818.64 397.446
  4821.5  396.37  4836.2  396.26  4872.4  397.16  4892.8  395.49  4913.2   396.5
  4978.8  396.68  4983.2  392.82    4984  392.02  4993.2  392.02    4994  392.82
  4996.7  394.27    4998  394.27  5002.1  394.26 5010.46397.4472    5020  403.35
  5032.3  405.13  5147.4  404.77  5217.4  405.36  5229.1  405.99  5251.6  405.36
  5274.9  405.63  5436.8  408.33  5472.3  410.09  5547.7  411.97  5617.6  412.81
#Mann= 5 ,-1 , 0
  4751.5      .1       0  4836.2     .07       0  4983.2     .07       0
    4994     .07       0    4998      .1       0
Bank Sta=4818.64,5010.46
XS Rating Curve= 0 ,0
Exp/Cntr=0.3,0.1

Type RM Length L Ch R = 1 ,5845    ,622,622,622
BEGIN DESCRIPTION:
Mapping XS 5abb0f32
END DESCRIPTION:
XS GIS Cut Line= 2
      2022405.15     13438130.91       2022948.5     13437525.07
#Sta/Elev= 30
    4602  405.03    4684  404.61  4804.3  401.52  4882.1  402.24  4896.3  401.76
  4903.8  399.94  4938.9  395.58 4953.46395.1176  4981.5  393.45  4988.2  392.27
    4990  387.05  4990.6  386.25  5000.8  386.25  5001.5  387.05  5009.9   391.5
  5016.6  392.89  5024.1   392.8  5038.3  394.26 5040.59395.1187  5052.5  399.09
  5059.3  399.24  5080.2  404.06  5087.7  404.41  5158.7  404.86  5222.2   404.1
  5250.6  404.98    5300  404.21  5328.4  404.61  5335.3  405.33  5415.8  404.03
#Mann= 3 ,-1 , 0
    4602      .1       0    4990     .07       0  5001.5      .1       0
Bank Sta=4953.46,5040.59
XS Rating Curve= 0 ,0
Exp/Cntr=0.3,0.1

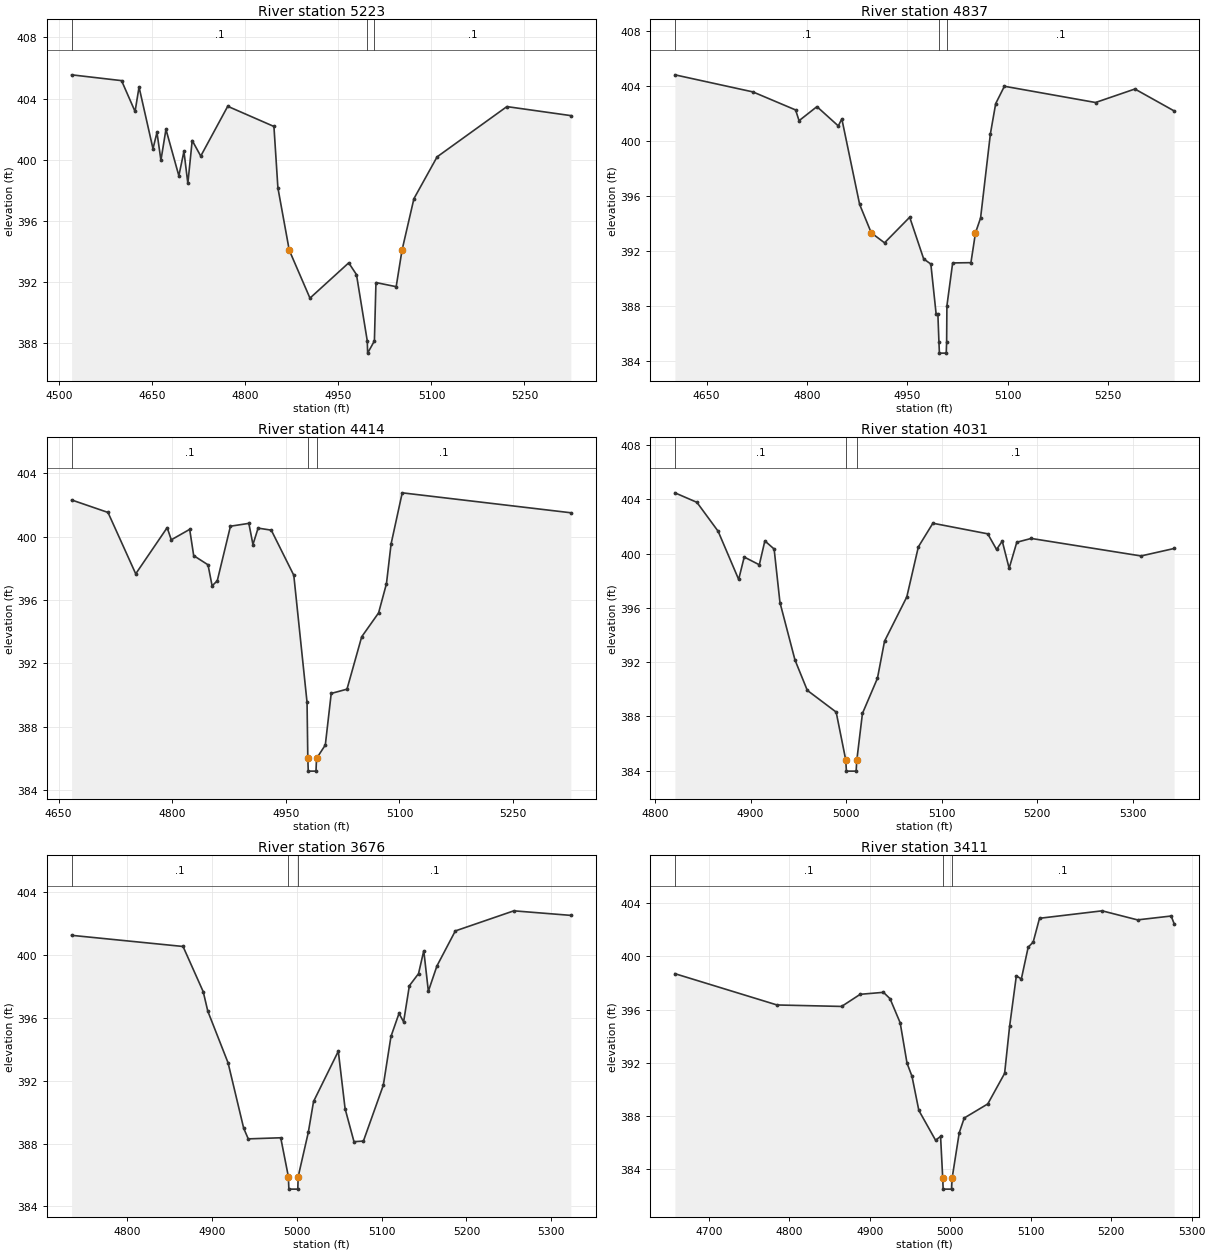
Type RM Length L Ch R = 1 ,5223    ,386,386,386
BEGIN DESCRIPTION:
Mapping XS 8ef5254b
END DESCRIPTION:
XS GIS Cut Line= 3
      2022811.39     13438344.47        2023044.     13438163.94
       2023253.4     13437698.42
#Sta/Elev= 30
  4519.8  405.55  4600.3  405.17  4622.1  403.15  4628.5  404.75    4651  400.71
  4657.4  401.78  4663.8  399.96  4671.9  401.98  4692.7  398.94  4700.9  400.54
  4707.2  398.44  4714.2  401.25    4728  400.23  4771.5  403.49    4846  402.17
  4852.4  398.15 4870.71394.0674  4904.1  390.93  4966.6  393.24  4979.1  392.47
  4996.5  388.13  4997.1  387.33    5008  388.13  5010.5  391.95  5043.1  391.68
 5052.52394.0669  5071.7  397.44  5109.1  400.18  5221.6  403.47  5324.7  402.88
#Mann= 3 ,-1 , 0
  4519.8      .1       0  4996.5     .07       0    5008      .1       0
Bank Sta=4870.71,5052.52
XS Rating Curve= 0 ,0
Exp/Cntr=0.3,0.1

Type RM Length L Ch R = 1 ,4837    ,423,423,423
BEGIN DESCRIPTION:
Mustang Creek 8.0
END DESCRIPTION:
XS GIS Cut Line= 3
      2023153.17     13438498.55        2023275.       13438125.
       2023481.7     13437838.87
#Sta/Elev= 30
  4602.6  404.81  4719.1  403.57  4782.9  402.26  4788.1  401.48  4814.8   402.5
  4846.7   401.1    4852  401.61  4878.6   395.4 4895.99393.3368  4915.8  392.61
  4953.4  394.47  4974.3  391.44    4985  391.07  4992.9  387.44  4995.5  387.44
  4997.1   385.4  4997.8   384.6    5008   384.6  5008.6   385.4    5009  388.03
  5017.6  391.15  5044.9  391.17 5051.71 393.336  5059.3  394.41    5074  400.53
  5081.9  402.72  5094.9  403.98  5231.1   402.8  5289.9  403.78  5348.5  402.19
#Mann= 3 ,-1 , 0
  4602.6      .1       0  4997.1     .07       0  5008.6      .1       0
Bank Sta=4895.99,5051.71
XS Rating Curve= 0 ,0
Exp/Cntr=0.3,0.1

Type RM Length L Ch R = 1 ,4414    ,383,383,383
BEGIN DESCRIPTION:
Mustang Creek 7.0
END DESCRIPTION:
XS GIS Cut Line= 3
      2023451.78     13438633.52        2023575.       13438325.
      2023665.31     13438011.16
#Sta/Elev= 30
  4667.3  402.32  4715.3  401.53  4751.9  397.65  4793.4  400.57  4798.8   399.8
  4823.1  400.46  4828.4   398.8  4847.3  398.22  4852.7  396.89  4859.5  397.21
  4876.9  400.66  4901.2  400.84  4906.6   399.5  4913.4  400.54  4930.8  400.41
  4960.5  397.56    4978  389.52    4979  385.98  4979.6  385.18  4989.8  385.18
  4990.5  385.98  5002.1  386.83  5009.9  390.09  5030.7  390.36  5050.1  393.67
  5072.4  395.18  5082.8  397.03  5088.9  399.54  5103.6  402.77  5326.1  401.51
#Mann= 3 ,-1 , 0
  4667.3      .1       0    4979     .07       0  4990.5      .1       0
Bank Sta=4979,4990.5
XS Rating Curve= 0 ,0
Exp/Cntr=0.3,0.1

Type RM Length L Ch R = 1 ,4031    ,355,355,355
BEGIN DESCRIPTION:
Mustang Creek 6.0
END DESCRIPTION:
XS GIS Cut Line= 3
      2023974.98     13438424.97      2023858.03     13438222.08
      2023701.83     13437979.97
#Sta/Elev= 30
  4820.9  404.47  4843.9  403.77  4866.1  401.64  4887.6  398.09  4893.4  399.74
  4909.2  399.17    4915  400.93  4924.7  400.33  4930.8  396.39  4946.5  392.16
  4959.4  389.92  4989.6  388.32  4999.7  384.77  5000.3  383.97  5010.5  383.97
  5011.2  384.77  5017.1  388.22  5032.8  390.81  5040.2  393.54  5063.5   396.8
  5075.6  400.49  5090.8  402.23  5148.2  401.45  5157.4   400.3  5163.4  400.91
  5170.6  398.91  5178.6  400.83  5193.7  401.11  5308.6  399.82  5343.2  400.37
#Mann= 3 ,-1 , 0
  4820.9      .1       0  4999.7     .07       0  5011.2      .1       0
Bank Sta=4999.7,5011.2
XS Rating Curve= 0 ,0
Exp/Cntr=0.3,0.1

Type RM Length L Ch R = 1 ,3676    ,265,265,265
BEGIN DESCRIPTION:
Mapping XS 7dbcf637
END DESCRIPTION:
XS GIS Cut Line= 2
       2024279.9     13438362.71      2024053.67     13437819.21
#Sta/Elev= 30
  4734.4  401.26  4865.8  400.55  4889.6  397.67    4895  396.43  4918.9  393.14
  4937.3  388.98  4942.7   388.3    4981  388.37    4990   385.9  4990.6   385.1
  5001.1   385.1  5001.6   385.9  5013.5  388.71  5019.7  390.68  5048.9  393.88
  5056.9  390.22  5067.4  388.12  5078.5  388.16    5102  391.72    5111  394.82
  5120.5  396.29  5125.9  395.75  5132.7  398.05  5143.5  398.82  5149.7  400.28
  5155.1   397.7  5165.2  399.31  5186.9  401.54  5255.9  402.82  5323.1  402.53
#Mann= 3 ,-1 , 0
  4734.4      .1       0    4990     .07       0  5001.6      .1       0
Bank Sta=4990,5001.6
XS Rating Curve= 0 ,0
Exp/Cntr=0.3,0.1

Type RM Length L Ch R = 1 ,3411    ,0,0,0
BEGIN DESCRIPTION:
Mapping XS 0a38ff82
END DESCRIPTION:
XS GIS Cut Line= 3
      2024456.99     13438331.44      2024475.22     13438117.91
      2024235.68     13437789.86
#Sta/Elev= 30
  4657.7   398.7  4784.6  396.35  4864.9  396.24    4888  397.15  4916.9   397.3
  4925.1  396.82  4937.7  395.01  4946.2  391.98  4952.4  390.99  4960.9  388.43
  4981.7  386.19  4987.9  386.48  4990.6  383.32  4991.1  382.52  5001.6  382.52
  5002.2  383.32  5011.1  386.75  5017.3  387.86  5046.6  388.92  5067.5  391.21
  5073.7  394.74  5082.1  398.54  5088.3   398.3  5096.8  400.69    5103  401.07
  5110.9  402.86  5188.7  403.42  5232.7  402.74  5274.5  403.03  5278.2  402.46
#Mann= 3 ,-1 , 0
  4657.7      .1       0  4990.6     .07       0  5002.2      .1       0
Bank Sta=4990.6,5002.2
XS Rating Curve= 0 ,0
Exp/Cntr=0.3,0.1
LCMann Table=0

Chan Stop Cuts=-1
Use User Specified Reach Order=0
Composite Channel Slope=5