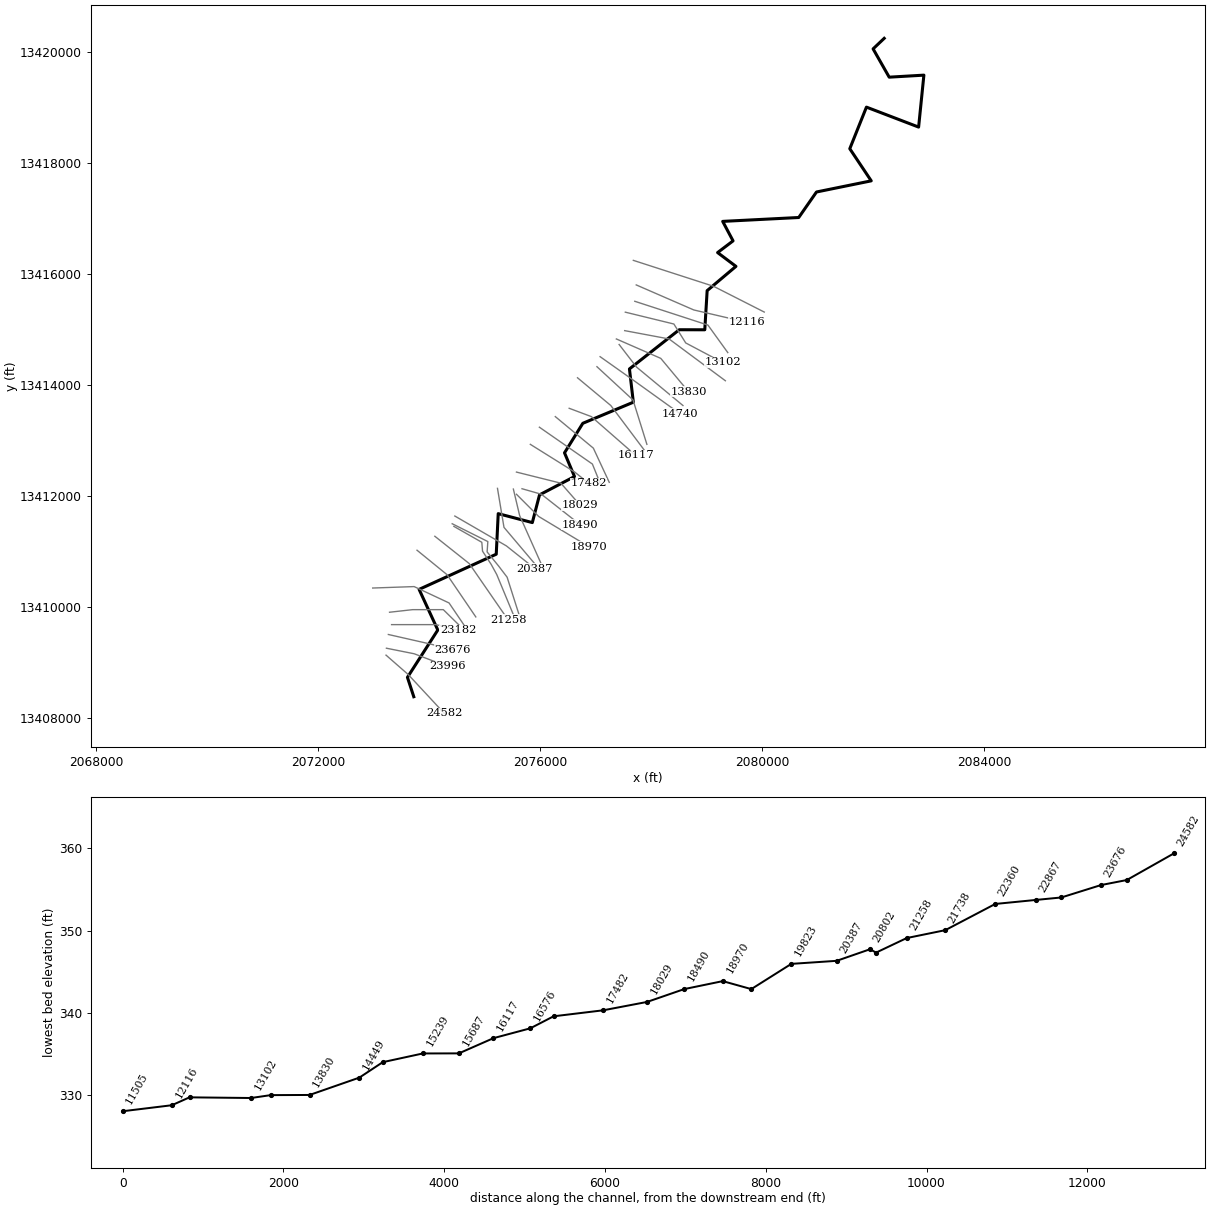
--- Prairie Creek.prj (project) ---

Proj Title=Prairie Creek Base Level Engineering
Current Plan=p01
Default Exp/Contr=0.3,0.1
English Units
Geom File=g01
Flow File=f01
Plan File=p01
Y Axis Title=Elevation
X Axis Title(PF)=Main Channel Distance
X Axis Title(XS)=Station
BEGIN DESCRIPTION:
Prairie Creek
END DESCRIPTION:
DSS Export Rating Curves= 0
DSS Export Rating Curve Sorted= 0
DSS Export Volume Flow Curves= 0
DXF OffsetX= 0
DXF OffsetY= 0
DXF ScaleX= 1
DXF ScaleY= 10

--- Prairie Creek.p01 (plan) ---

Plan Title=Multiple Run
Short Identifier=Multiple
Geom File=g01
Flow File=f01
Subcritical Flow
K Sum by GR= 0
Std Step Tol= 0.01
Critical Tol= 0.01
Num of Std Step Trials= 20
Max Error Tol= 0.3
Flow Tol Ratio= 0.001
Split Flow NTrial= 30
Split Flow Tol= 0.02
Split Flow Ratio= 0.02
Log Output Level= 0
Friction Slope Method= 1
Unsteady Friction Slope Method= 2
Unsteady Bridges Friction Slope Method= 1
Parabolic Critical Depth
Global Vel Dist=  1 , 1 , 1
Global Log Level= 0
CheckData=True
Encroach Param= -1, 0, 0, 0
BEGIN DESCRIPTION:
Multiple Run
END DESCRIPTION:

--- Prairie Creek.f01 (steady flow) ---

Flow Title=Multiple
Number of Profiles=7
Profile Names=10-year,25-year,50-year,1pct_min,100-year,1pct_plu,500-year
River Rch & RM= Prairie Creek,Reach-1,24582
     223     307     377     231     461     920     699
River Rch & RM= Prairie Creek,Reach-1,20387
     292     407     502     309     616    1229     942
River Rch & RM= Prairie Creek,Reach-1,15687
     319     445     549     337     672    1341    1026
River Rch & RM= Prairie Creek,Reach-1,9166
     363     508     628     387     771    1539    1181
Boundary for River Rch & Prof#=Prairie Creek,Reach-1,1
Up Type=0
Dn Type=3
Dn Slope=0.005
Boundary for River Rch & Prof#=Prairie Creek,Reach-1,2
Up Type=0
Dn Type=3
Dn Slope=0.005
Boundary for River Rch & Prof#=Prairie Creek,Reach-1,3
Up Type=0
Dn Type=3
Dn Slope=0.005
Boundary for River Rch & Prof#=Prairie Creek,Reach-1,4
Up Type=0
Dn Type=3
Dn Slope=0.005
Boundary for River Rch & Prof#=Prairie Creek,Reach-1,5
Up Type=0
Dn Type=3
Dn Slope=0.005
Boundary for River Rch & Prof#=Prairie Creek,Reach-1,6
Up Type=0
Dn Type=3
Dn Slope=0.005
Boundary for River Rch & Prof#=Prairie Creek,Reach-1,7
Up Type=0
Dn Type=3
Dn Slope=0.005

--- Prairie Creek.g01 (geometry) ---

Geom Title=Existing Conditions
Program Version=5.05

River Reach=Prairie Creek   ,Reach-1
Reach XY= 30
        2073725.       13408375.       2073610.8     13408724.54
      2074157.98     13409577.99        2073821.     13410310.28
       2075210.8     13410944.54      2075246.39     13411675.68
       2075860.8     13411514.54       2075990.8     13412014.54
       2076620.8     13412344.54       2076440.8     13412772.03
       2076770.8     13413304.54       2077680.8     13413684.54
       2077610.8     13414284.54      2078508.05     13414991.21
      2078968.12     13414990.34       2079010.8     13415696.07
      2079529.75     13416133.57      2079199.02     13416382.27
      2079477.67      13416593.2       2079290.8     13416944.54
       2080660.8     13417014.54       2080980.8     13417474.54
      2081967.21     13417675.37       2081580.8     13418254.54
       2081880.8     13419004.54       2082820.8     13418644.54
      2082915.82     13419580.91       2082290.8     13419544.54
       2082000.8     13420054.54       2082200.8     13420244.54

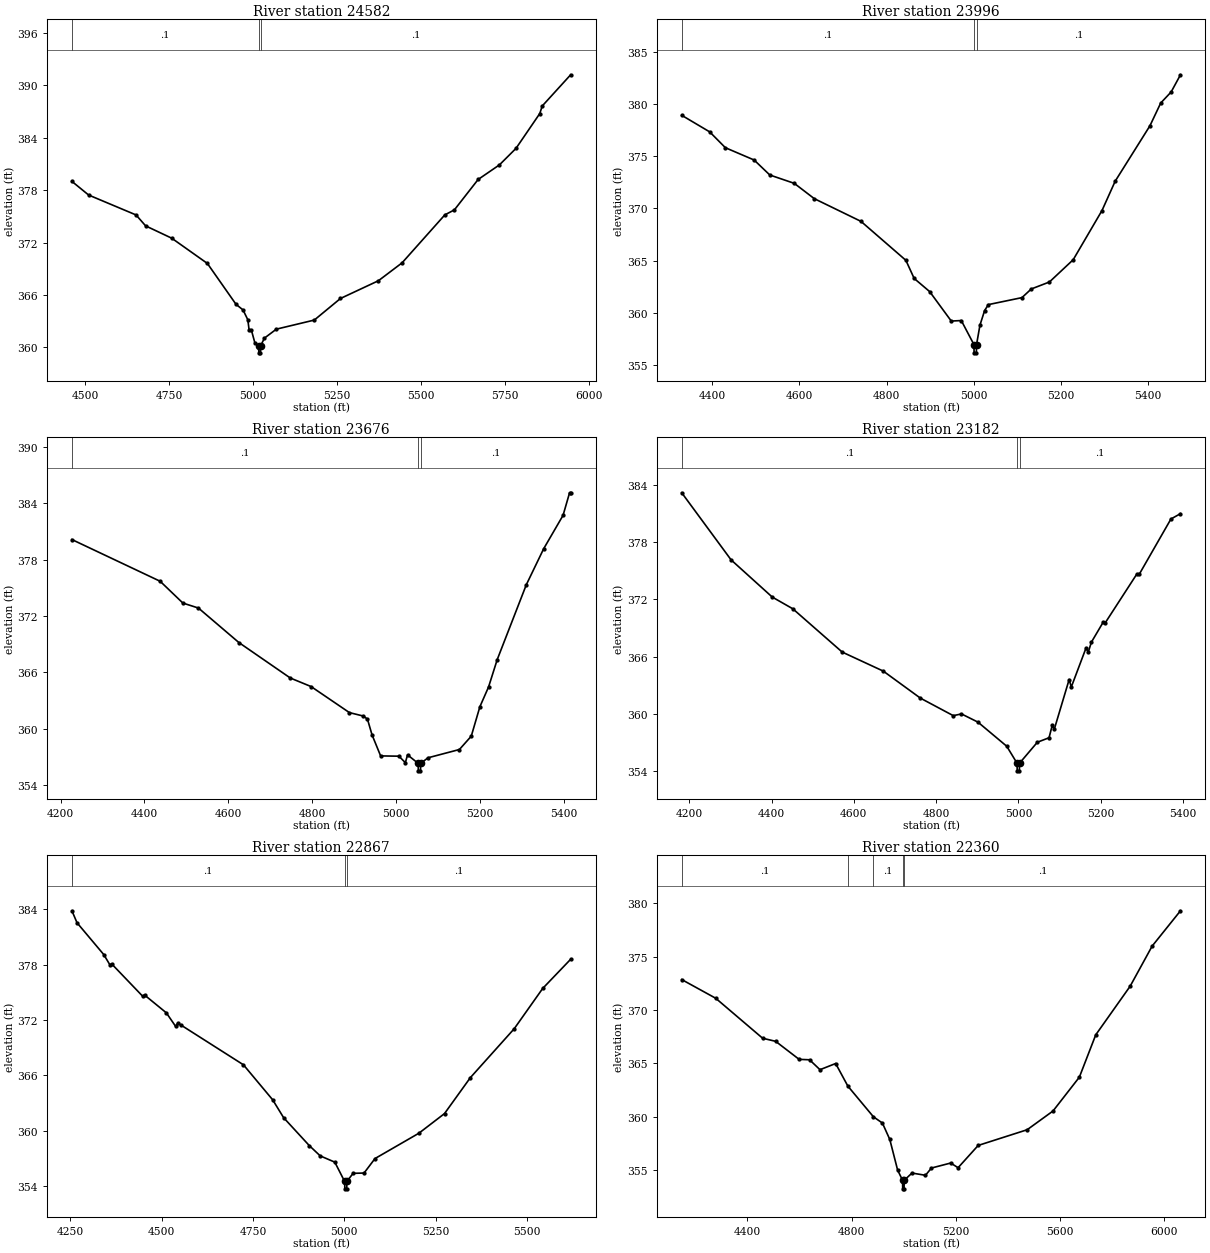
Type RM Length L Ch R = 1 ,24582   ,586,586,586
BEGIN DESCRIPTION:
Prairie Creek 36.0
END DESCRIPTION:
XS GIS Cut Line= 3
      2073225.02     13409124.98        2073625.       13408775.
      2074274.98     13408075.02
#Sta/Elev= 30
    4460     379  4509.8  377.44  4651.2  375.16  4679.7  373.91  4757.5   372.5
  4863.8  369.61  4949.2  364.93  4970.1  364.29  4984.4  363.16  4988.2  361.99
  4994.9  361.99  5005.4  360.52  5016.6  360.18  5017.1  359.38  5022.1  359.38
  5022.6  360.18  5033.7  361.06  5069.4  362.09  5182.5  363.13  5260.5   365.6
  5373.6  367.63  5444.2  369.68  5571.7  375.17  5600.1  375.74  5670.9  379.22
  5734.4  380.89  5783.8  382.78  5854.6  386.76    5862  387.63  5946.7   391.2
#Mann= 3 ,-1 , 0
    4460      .1       0  5016.6     .07       0  5022.6      .1       0
Bank Sta=5016.6,5022.6
XS Rating Curve= 0 ,0
Exp/Cntr=0.3,0.1

Type RM Length L Ch R = 1 ,23996   ,320,320,320
BEGIN DESCRIPTION:
Prairie Creek 35.0
END DESCRIPTION:
XS GIS Cut Line= 3
      2073232.18     13409249.69      2073732.15     13409149.69
      2074325.03     13408924.99
#Sta/Elev= 30
  4330.2  378.94  4394.3  377.35  4430.3  375.83  4496.2  374.65  4532.2  373.21
  4588.3  372.41  4634.2  370.94  4741.3  368.76  4844.3  365.02  4863.3  363.28
  4898.8  362.02  4948.4  359.19  4971.4  359.24  5000.3  356.94  5000.8  356.14
  5005.9  356.14  5006.4  356.94  5014.2   358.8  5024.9   360.2  5033.5  360.77
  5110.5  361.44  5131.9  362.27  5173.5  362.94  5228.1  365.08  5294.1   369.8
  5324.4  372.62    5404  377.93  5428.8  380.12  5452.7  381.18  5474.1  382.83
#Mann= 3 ,-1 , 0
  4330.2      .1       0  5000.3     .07       0  5006.4      .1       0
Bank Sta=5000.3,5006.4
XS Rating Curve= 0 ,0
Exp/Cntr=0.3,0.1

Type RM Length L Ch R = 1 ,23676   ,494,494,494
BEGIN DESCRIPTION:
Prairie Creek 34.0
END DESCRIPTION:
XS GIS Cut Line= 3
      2073266.91     13409497.08        2074025.       13409325.
      2074425.01       13409225.
#Sta/Elev= 30
  4227.2  380.15  4437.7  375.71  4491.9  373.39    4529  372.86  4625.4  369.19
  4748.2  365.41  4797.8   364.5  4889.1  361.73  4922.5  361.36  4932.2  361.03
  4943.1  359.36  4963.6  357.12  5007.2  357.09  5022.6   356.4  5027.8  357.23
  5053.1  356.33  5053.6  355.53  5058.7  355.53  5059.2  356.33  5076.7  356.92
  5151.5   357.8  5179.8  359.22  5200.4  362.36    5221  364.45  5241.7  367.37
  5311.2  375.35  5352.5  379.17  5398.8  382.73  5414.3  385.13  5416.9  385.13
#Mann= 3 ,-1 , 0
  4227.2      .1       0  5053.1     .07       0  5059.2      .1       0
Bank Sta=5053.1,5059.2
XS Rating Curve= 0 ,0
Exp/Cntr=0.3,0.1

Type RM Length L Ch R = 1 ,23182   ,315,315,315
BEGIN DESCRIPTION:
Prairie Creek 33.0
END DESCRIPTION:
XS GIS Cut Line= 3
      2073325.02       13409675.        2074125.       13409675.
      2074525.01       13409575.
#Sta/Elev= 30
  4181.6  383.19  4301.6  376.15  4401.6  372.25  4451.6  371.02  4571.6  366.48
  4671.6  364.48  4761.6  361.65  4841.6  359.81  4861.6  359.99  4901.6  359.13
  4971.6   356.6  4996.6  354.82  4997.1  354.02  5002.2  354.02  5002.7  354.82
    5046  357.02  5074.4  357.49  5082.1  358.78  5087.2  358.39  5123.3   363.6
  5128.5  362.81  5164.5  366.93  5169.7  366.47  5177.4  367.52  5205.8   369.6
  5210.9  369.54  5288.2  374.69  5293.4  374.62  5370.7  380.44  5393.9     381
#Mann= 3 ,-1 , 0
  4181.6      .1       0  4996.6     .07       0  5002.7      .1       0
Bank Sta=4996.6,5002.7
XS Rating Curve= 0 ,0
Exp/Cntr=0.3,0.1

Type RM Length L Ch R = 1 ,22867   ,507,507,507
BEGIN DESCRIPTION:
Mapping XS 341b2624
END DESCRIPTION:
XS GIS Cut Line= 4
      2073288.23      13409898.2      2073704.94     13409945.08
      2074257.02     13409945.08      2074537.77     13409669.53
#Sta/Elev= 30
  4254.8  383.83  4268.8  382.53  4342.1  379.08  4358.8  377.97  4363.8  378.07
  4448.8  374.56  4453.8   374.7  4513.2  372.78  4538.8   371.3  4543.8  371.64
  4553.4  371.45  4724.2  367.15  4804.2  363.36  4834.2  361.42  4904.2  358.41
  4934.2  357.29  4974.2  356.61  5001.1  354.52  5001.6  353.72  5006.8  353.72
  5007.3  354.52  5024.2   355.4  5054.2  355.43  5084.2     357  5204.2  359.74
  5274.4  361.87  5345.1  365.76  5465.2  371.06  5543.1  375.42  5619.6  378.58
#Mann= 3 ,-1 , 0
  4254.8      .1       0  5001.1     .07       0  5007.3      .1       0
Bank Sta=5001.1,5007.3
XS Rating Curve= 0 ,0
Exp/Cntr=0.3,0.1

Type RM Length L Ch R = 1 ,22360   ,622,622,622
BEGIN DESCRIPTION:
Prairie Creek 32.0
END DESCRIPTION:
XS GIS Cut Line= 4
      2072984.79     13410334.76      2073731.29      13410360.8
      2074360.63     13410065.67      2074625.02     13409674.98
#Sta/Elev= 30
  4148.4  372.85  4278.7   371.1  4458.8  367.35  4508.8  367.06  4598.9  365.37
  4638.9  365.33  4678.9   364.4    4739  364.98  4785.9  362.86  4884.1  359.98
  4918.4   359.4  4946.8  357.86  4976.8  354.99  4995.8  354.03  4996.3  353.23
  5001.5  353.23    5002  354.03    5032  354.71  5083.7   354.5  5106.5  355.18
  5180.5  355.65  5208.8  355.21    5286   357.3  5473.8  358.77  5573.2  360.53
  5674.2   363.7  5737.1  367.67  5868.9  372.22  5953.5  375.99  6062.2   379.3
#Mann= 5 ,-1 , 0
  4148.4      .1       0  4785.9     .05       0  4884.1      .1       0
  4995.8     .07       0    5002      .1       0
Bank Sta=4995.8,5002
XS Rating Curve= 0 ,0
Exp/Cntr=0.3,0.1

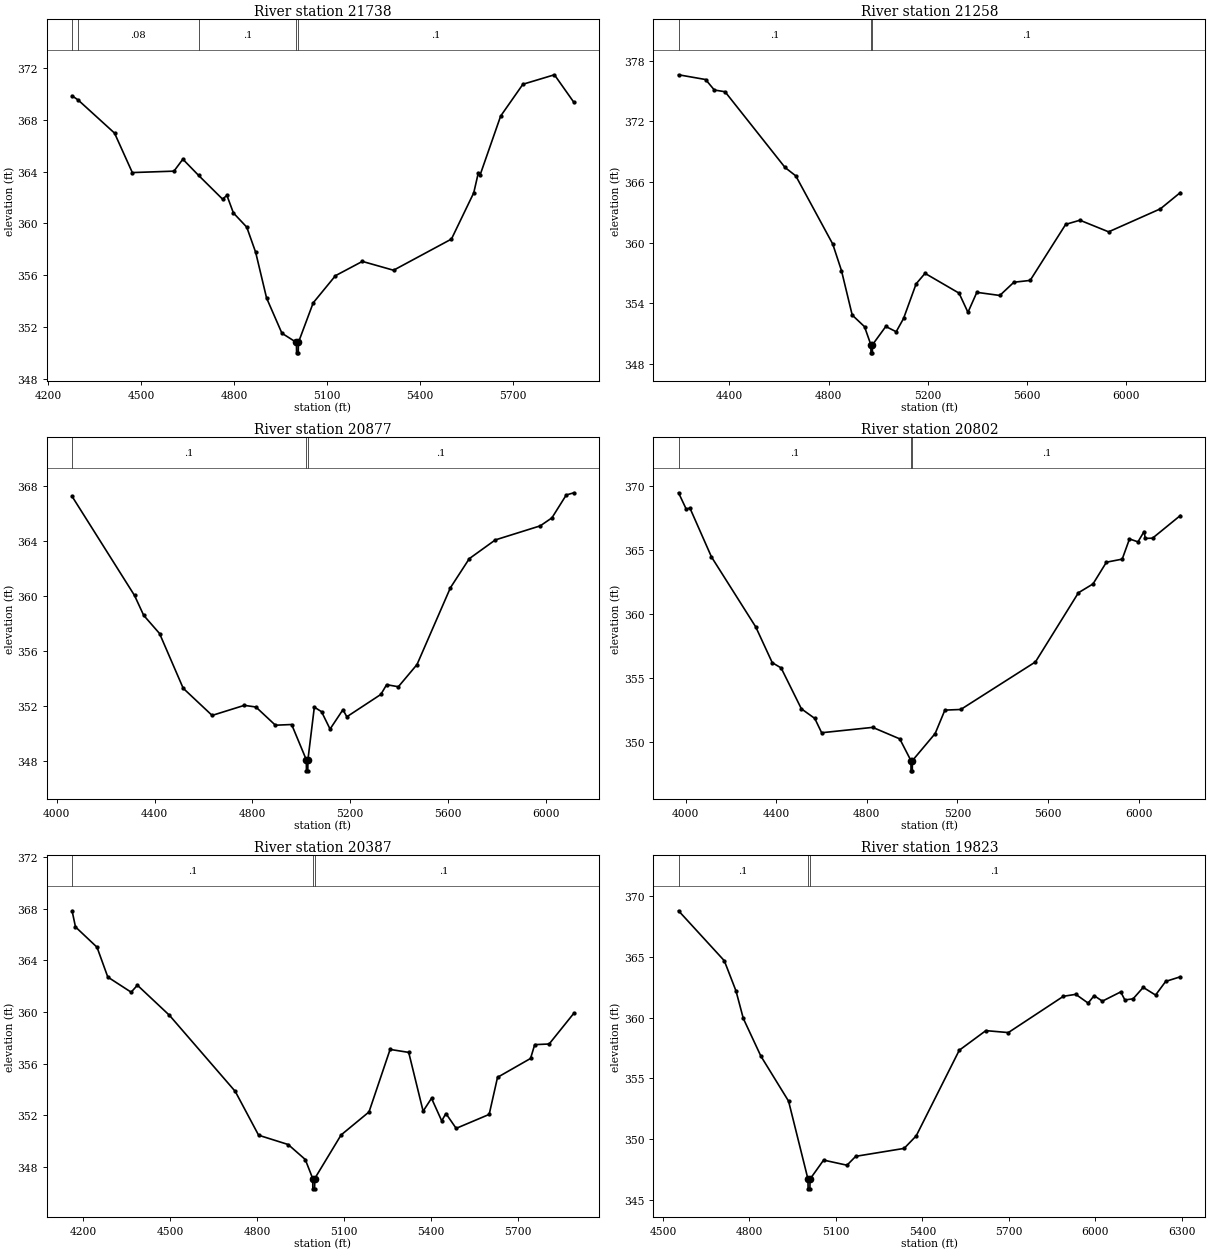
Type RM Length L Ch R = 1 ,21738   ,480,480,480
BEGIN DESCRIPTION:
Prairie Creek 31.0
END DESCRIPTION:
XS GIS Cut Line= 3
      2073783.38     13411016.17        2074325.       13410575.
      2074842.37     13409813.97
#Sta/Elev= 30
  4276.7  369.83  4296.2  369.51  4413.7  366.96  4471.1  363.92  4605.4  364.03
  4634.1  364.95    4685   363.7    4762  361.88  4776.3  362.16  4797.2  360.81
  4840.2  359.72    4869  357.78  4904.2  354.26  4953.7  351.55  5000.5  350.84
    5001  350.04  5006.4  350.04  5006.9  350.84  5054.6  353.89  5126.4  355.98
  5213.2  357.08  5313.8   356.4  5500.6   358.8  5572.5  362.36  5587.4  363.91
  5593.4  363.76  5659.3  368.27  5731.1  370.72  5832.8  371.45  5895.5  369.33
#Mann= 5 ,-1 , 0
  4276.7     .05       0  4296.2     .08       0    4685      .1       0
  5000.5     .07       0  5006.9      .1       0
Bank Sta=5000.5,5006.9
XS Rating Curve= 0 ,0
Exp/Cntr=0.3,0.1

Type RM Length L Ch R = 1 ,21258   ,381,381,381
BEGIN DESCRIPTION:
Prairie Creek 30.0
END DESCRIPTION:
XS GIS Cut Line= 3
      2074104.57      13411267.9        2074725.       13410775.
      2075424.01     13409761.82
#Sta/Elev= 30
  4194.9  376.61    4304  376.14  4339.3   375.1  4382.5  374.93  4624.4  367.43
  4667.7   366.6  4816.7  359.85  4851.9  357.22  4895.2  352.82  4944.8  351.67
  4970.4  349.88  4970.9  349.08  4976.4  349.08  4976.9  349.88  5030.6  351.69
  5072.5  351.17  5102.2  352.48  5152.9  355.91  5188.8  356.95    5326  354.99
  5361.9  353.09  5397.7  355.07  5490.3  354.76  5547.1  356.07  5612.7  356.25
    5756   361.8  5813.4  362.21  5929.1  361.06    6138  363.34  6218.2  364.95
#Mann= 3 ,-1 , 0
  4194.9      .1       0  4970.4     .07       0  4976.9      .1       0
Bank Sta=4970.4,4976.9
XS Rating Curve= 0 ,0
Exp/Cntr=0.3,0.1

Type RM Length L Ch R = 1 ,20877   ,75,75,75
BEGIN DESCRIPTION:
Mapping XS 66d9eb29
END DESCRIPTION:
XS GIS Cut Line= 6
      2074447.46     13411445.86       2074950.9     13411159.42
      2074963.93     13410998.82      2075120.18     13410760.11
        2075220.     13410577.82      2075532.49     13409822.65
#Sta/Elev= 30
  4062.8  367.22  4318.1  360.03  4355.5  358.59  4420.4  357.27    4517   353.3
  4635.2  351.33  4766.8  352.06  4814.2  351.94  4893.9  350.62  4960.3  350.67
  5020.3  348.11  5020.8  347.31  5026.3  347.31  5026.8  348.11    5053  351.93
  5082.5   351.6  5117.3  350.34  5170.1  351.75  5185.7  351.23  5324.7  352.85
  5348.6  353.56  5396.4  353.41  5472.7  355.02  5609.2  360.59  5686.3   362.7
  5792.7  364.06  5976.3  365.08  6024.1  365.66  6082.7  367.32  6113.8  367.48
#Mann= 3 ,-1 , 0
  4062.8      .1       0  5020.3     .07       0  5026.8      .1       0
Bank Sta=5020.3,5026.8
XS Rating Curve= 0 ,0
Exp/Cntr=0.3,0.1

Type RM Length L Ch R = 1 ,20802   ,415,415,415
BEGIN DESCRIPTION:
Mapping XS a9c4f508
END DESCRIPTION:
XS GIS Cut Line= 6
      2074417.02     13411493.63      2075059.41     13411172.44
      2075046.39      13410985.8      2075254.72     13410729.73
      2075406.63     13410530.07      2075627.99     13409835.63
#Sta/Elev= 30
  3969.1  369.47  4002.8   368.2  4019.5  368.27  4114.6  364.45  4310.2  358.97
  4382.9  356.18    4422  355.77  4511.5  352.57  4570.6  351.82  4600.9   350.7
  4826.3  351.12  4945.8  350.22  4995.1  348.52  4995.6  347.72  5001.1  347.72
  5001.6  348.52  5102.2  350.64    5145  352.47  5215.2  352.52  5544.9  356.24
  5734.6  361.65    5799  362.34  5858.2  364.04  5927.9  364.28  5960.1  365.86
  5997.5  365.63  6024.5  366.44  6029.7   365.9  6061.9  365.92  6184.5  367.69
#Mann= 3 ,-1 , 0
  3969.1      .1       0  4995.1     .07       0  5001.6      .1       0
Bank Sta=4995.1,5001.6
XS Rating Curve= 0 ,0
Exp/Cntr=0.3,0.1

Type RM Length L Ch R = 1 ,20387   ,564,564,564
BEGIN DESCRIPTION:
Mapping XS 2cdcdd29
END DESCRIPTION:
XS GIS Cut Line= 3
      2074464.79     13411632.51      2075393.61     13411094.31
      2075905.78     13410686.31
#Sta/Elev= 30
  4162.9  367.83  4174.7  366.58  4248.8  365.01    4286   362.7  4366.4  361.53
  4387.9  362.07  4498.3  359.74    4725  353.85  4805.4  350.46  4907.2  349.74
  4966.1  348.58  4991.7  347.11  4992.2  346.31  4998.3  346.31  4998.8  347.11
  5089.5  350.48  5185.6  352.26  5258.3   357.1  5322.4  356.87    5372  352.32
  5400.9  353.32  5436.1  351.57  5450.5  352.14  5485.8  350.99  5599.5  352.07
  5628.3  354.94    5742   356.4  5756.4  357.47  5806.1  357.52  5891.2   359.9
#Mann= 3 ,-1 , 0
  4162.9      .1       0  4991.7     .07       0  4998.8      .1       0
Bank Sta=4991.7,4998.8
XS Rating Curve= 0 ,0
Exp/Cntr=0.3,0.1

Type RM Length L Ch R = 1 ,19823   ,498,498,498
BEGIN DESCRIPTION:
Mapping XS 8bcb487b
END DESCRIPTION:
XS GIS Cut Line= 3
      2075233.02     13412131.67      2075350.21     13411428.51
      2076014.27     13410642.93
#Sta/Elev= 30
  4553.9  368.77  4712.7  364.67  4753.3  362.19  4778.7  359.93  4839.6  356.84
  4935.8  353.14  5003.1  346.74  5003.6  345.94  5009.8  345.94  5010.3  346.74
  5057.4   348.3  5138.5  347.88  5168.9  348.61  5336.8  349.26  5378.8  350.29
  5528.2  357.32  5620.5  358.93  5698.5  358.77  5889.7  361.75  5932.6  361.91
  5975.4  361.19  5996.3   361.8  6024.9  361.35  6088.6  362.11  6102.9  361.45
  6131.4  361.54  6166.6  362.48  6209.5  361.85  6244.6  362.97  6295.4  363.35
#Mann= 3 ,-1 , 0
  4553.9      .1       0  5003.1     .07       0  5010.3      .1       0
Bank Sta=5003.1,5010.3
XS Rating Curve= 0 ,0
Exp/Cntr=0.3,0.1

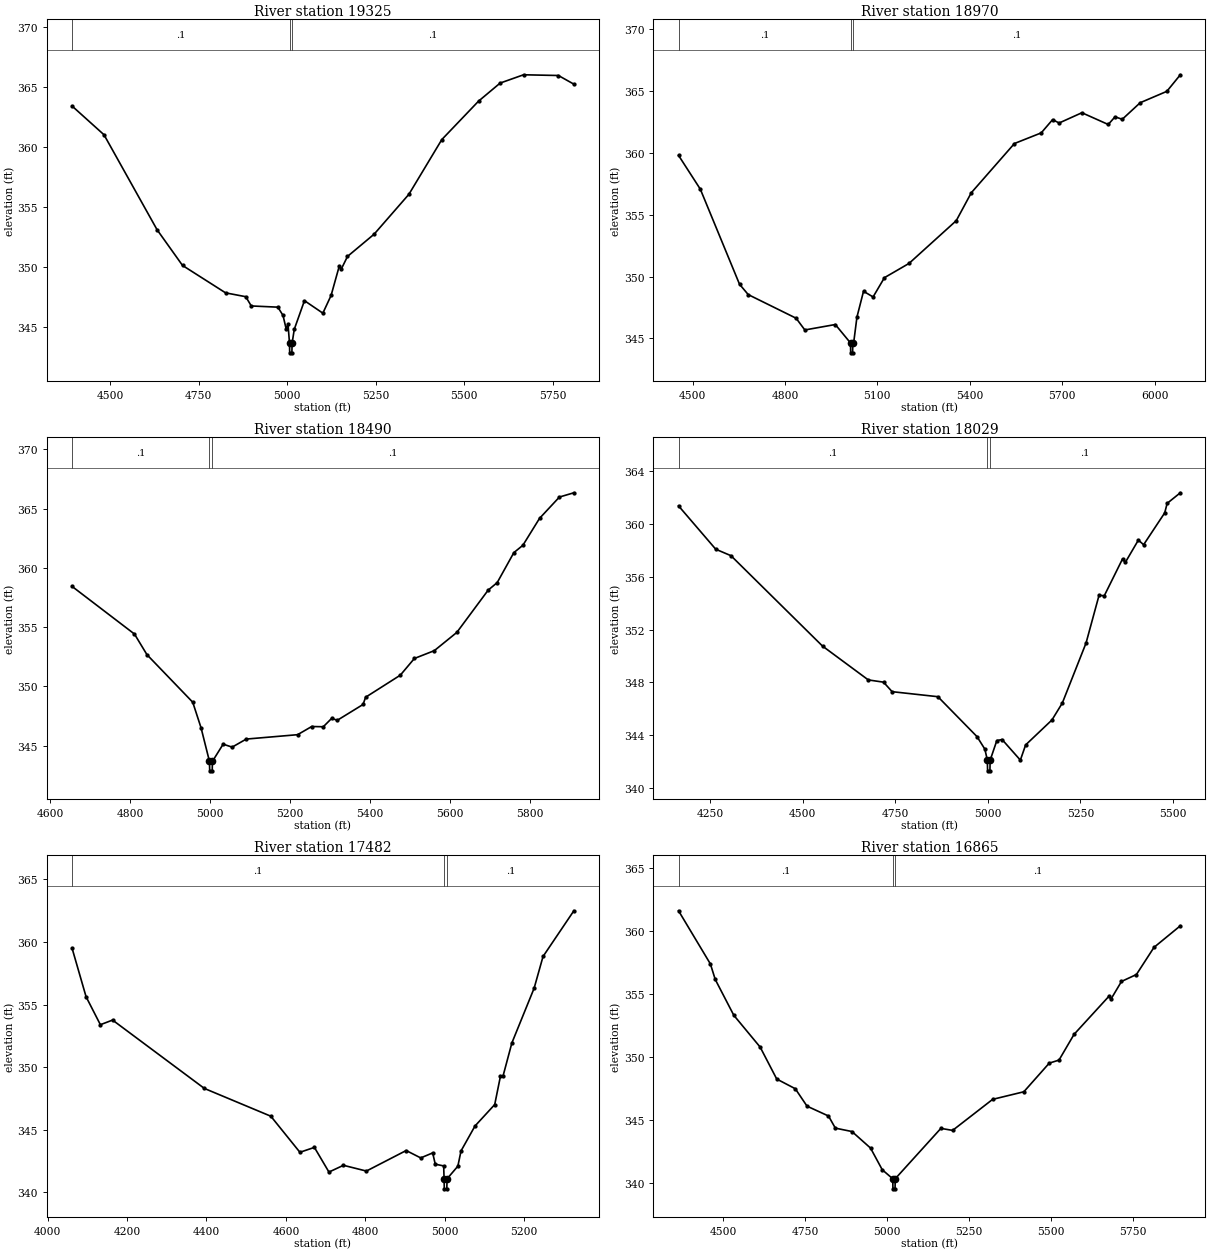
Type RM Length L Ch R = 1 ,19325   ,355,355,355
BEGIN DESCRIPTION:
Prairie Creek 29.0
END DESCRIPTION:
XS GIS Cut Line= 3
      2075519.47     13412118.65      2075632.33     13411641.19
      2076009.94     13410794.82
#Sta/Elev= 30
  4392.6   363.4  4482.8  361.01  4632.7  353.11  4704.6  350.14  4826.2  347.86
  4883.2  347.54  4898.8  346.77  4973.9  346.67  4988.5  345.98  4997.1  344.89
  5002.6  345.23  5006.8  343.67  5007.3  342.87  5013.5  342.87  5014.1  343.67
  5020.3  344.83    5049  347.21    5101  346.17  5124.2  347.64  5147.4  350.09
  5152.9  349.83  5170.6  350.89  5245.8  352.74  5344.1  356.06    5437  360.61
  5540.9  363.81  5601.8  365.31  5667.9     366  5766.3  365.94    5810  365.22
#Mann= 3 ,-1 , 0
  4392.6      .1       0  5006.8     .07       0  5014.1      .1       0
Bank Sta=5006.8,5014.1
XS Rating Curve= 0 ,0
Exp/Cntr=0.3,0.1

Type RM Length L Ch R = 1 ,18970   ,480,480,480
BEGIN DESCRIPTION:
Prairie Creek 28.0
END DESCRIPTION:
XS GIS Cut Line= 3
        2075575.       13412025.        2075975.       13411625.
      2076886.67     13411076.95
#Sta/Elev= 30
  4454.4  359.81  4525.1  357.08  4652.4  349.39  4680.7  348.55  4836.2  346.64
  4864.5  345.69  4963.5  346.13  5012.8  344.64  5013.4  343.84  5019.7  343.84
  5020.2  344.64    5023  344.64  5033.7  346.73  5055.1  348.82  5086.1  348.36
    5123  349.92  5202.7  351.07  5356.2  354.53  5405.1  356.79  5545.1  360.77
  5632.1  361.63    5669   362.7  5690.3  362.43  5764.2  363.26  5849.7  362.31
  5871.8  362.93  5895.2  362.73  5953.5  364.07    6040  364.99  6083.8  366.33
#Mann= 3 ,-1 , 0
  4454.4      .1       0  5012.8     .07       0  5020.2      .1       0
Bank Sta=5012.8,5020.2
XS Rating Curve= 0 ,0
Exp/Cntr=0.3,0.1

Type RM Length L Ch R = 1 ,18490   ,461,461,461
BEGIN DESCRIPTION:
Prairie Creek 27.0
END DESCRIPTION:
XS GIS Cut Line= 3
        2075675.       13412125.        2076025.       13412025.
      2076724.98     13411475.02
#Sta/Elev= 30
  4655.2  358.43  4811.2  354.41  4842.4  352.67  4956.8  348.66  4977.6   346.5
  4998.6  343.67  4999.2  342.87  5005.5  342.87    5006  343.67  5032.8  345.12
  5055.3  344.87  5090.6  345.55  5218.9  345.92  5254.2  346.61  5283.1  346.59
  5303.9  347.29  5318.4  347.14  5382.5  348.47  5388.9  349.08  5475.6  350.94
  5510.8  352.35  5560.6  353.01  5616.9  354.55  5695.3  358.12  5717.8  358.75
  5759.4  361.28    5782   361.9  5823.6  364.17  5873.3  365.97  5909.4  366.33
#Mann= 3 ,-1 , 0
  4655.2      .1       0  4998.6     .07       0    5006      .1       0
Bank Sta=4998.6,5006
XS Rating Curve= 0 ,0
Exp/Cntr=0.3,0.1

Type RM Length L Ch R = 1 ,18029   ,547,547,547
BEGIN DESCRIPTION:
Prairie Creek 26.0
END DESCRIPTION:
XS GIS Cut Line= 3
      2075575.03     13412424.99        2076375.       13412225.
        2076725.       13411825.
#Sta/Elev= 30
  4164.1  361.36  4264.6  358.08  4305.8  357.59  4553.2  350.75  4676.9  348.19
  4718.1  348.02  4741.3   347.3    4865  346.92  4970.7   343.9    4992  342.95
  4998.7  342.11  4999.3  341.31  5005.6  341.31  5006.2  342.11  5024.3   343.6
  5038.5  343.68  5087.9  342.12  5102.1  343.27  5173.3  345.16  5201.3  346.44
  5265.4  350.98  5300.5  354.59  5314.7  354.56  5364.1  357.35  5371.7  357.09
  5406.8  358.77    5421  358.42    5478  360.83  5484.6  361.55  5520.2  362.35
#Mann= 3 ,-1 , 0
  4164.1      .1       0  4998.7     .07       0  5006.2      .1       0
Bank Sta=4998.7,5006.2
XS Rating Curve= 0 ,0
Exp/Cntr=0.3,0.1

Type RM Length L Ch R = 1 ,17482   ,617,617,617
BEGIN DESCRIPTION:
Prairie Creek 25.0
END DESCRIPTION:
XS GIS Cut Line= 3
      2075825.04     13412924.98        2076625.       13412425.
      2076874.99     13412225.01
#Sta/Elev= 30
  4061.6  359.51  4096.9  355.63  4132.9   353.4  4163.6  353.77  4394.7  348.31
  4562.1  346.09  4635.3  343.21  4671.8   343.6  4708.4  341.63  4744.9  342.17
  4802.7  341.71  4902.9  343.35  4939.5  342.76  4969.6  343.16  4976.1  342.26
  4997.3  342.12  4998.3  341.09  4998.9  340.29  5005.2  340.29  5005.8  341.09
    5033   342.1    5041  343.32  5076.2  345.31  5125.8  347.02  5140.2  349.28
  5146.6  349.28    5169  351.94  5225.1  356.32  5247.5  358.85  5325.1   362.5
#Mann= 3 ,-1 , 0
  4061.6      .1       0  4998.3     .07       0  5005.8      .1       0
Bank Sta=4998.3,5005.8
XS Rating Curve= 0 ,0
Exp/Cntr=0.3,0.1

Type RM Length L Ch R = 1 ,16865   ,289,289,289
BEGIN DESCRIPTION:
Mapping XS 594c6fe8
END DESCRIPTION:
XS GIS Cut Line= 3
      2075988.21     13413234.08      2076943.09     13412570.01
       2077081.4     13412228.55
#Sta/Elev= 30
  4362.8  361.59    4460  357.38  4474.8  356.15  4531.5  353.31  4611.9  350.79
  4662.5  348.26  4719.2  347.49    4755  346.11  4820.5  345.33  4841.4  344.37
  4892.1   344.1  4948.8  342.79  4984.6  341.07  5016.5  340.36  5017.2  339.56
  5023.6  339.56  5024.2  340.36  5163.5  344.35  5199.3  344.19  5321.5  346.65
  5416.7  347.25  5494.3  349.52    5524  349.76    5570   351.8  5677.2  354.84
  5682.6  354.59  5714.7  355.99  5760.3  356.54  5813.9  358.69  5894.3   360.4
#Mann= 3 ,-1 , 0
  4362.8      .1       0  5016.5     .07       0  5024.2      .1       0
Bank Sta=5016.5,5024.2
XS Rating Curve= 0 ,0
Exp/Cntr=0.3,0.1

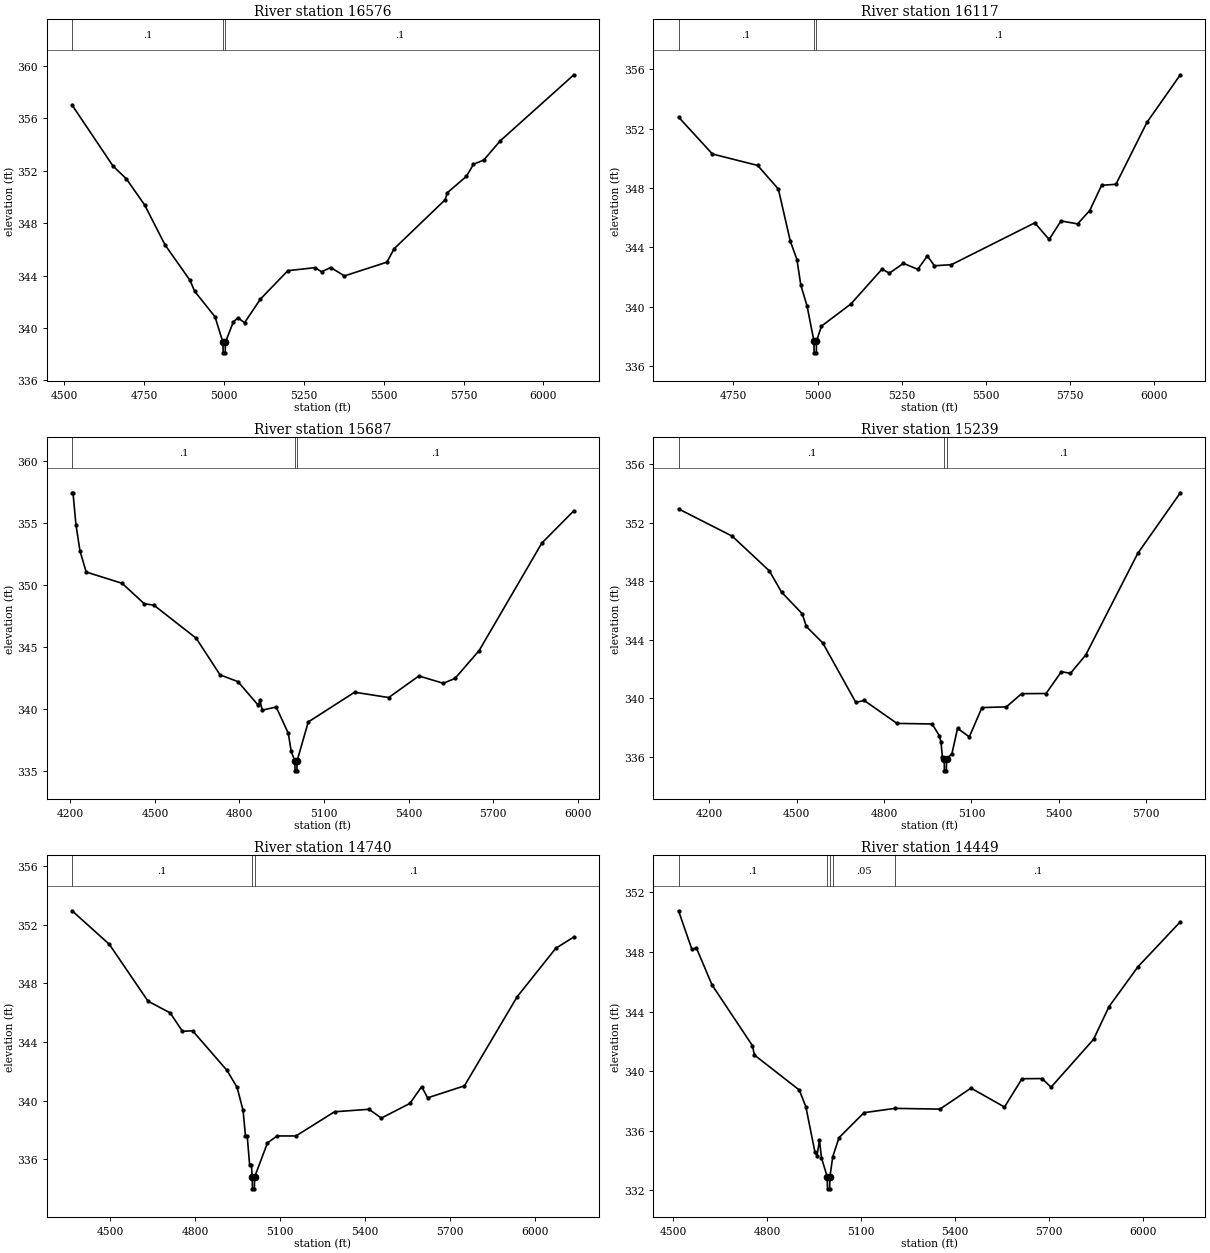
Type RM Length L Ch R = 1 ,16576   ,459,459,459
BEGIN DESCRIPTION:
Prairie Creek 24.0
END DESCRIPTION:
XS GIS Cut Line= 3
        2076275.       13413425.      2076960.45     13412856.46
      2077246.92     13412240.13
#Sta/Elev= 30
  4524.9  357.01  4653.2  352.35  4694.8  351.38  4752.1  349.38    4816  346.33
  4894.1  343.63  4908.4   342.8  4972.2  340.85    4997   338.9  4997.6   338.1
  5004.1   338.1  5004.7   338.9  5029.5  340.46  5043.9  340.77  5064.7   340.4
  5114.2   342.2  5200.1  344.37  5284.8   344.6  5305.6  344.29  5334.2  344.61
  5377.2  343.97    5510  345.02  5532.9  346.05  5692.7  349.79  5698.7  350.31
  5758.9  351.57    5781  352.49  5813.1  352.81  5864.4  354.27  6095.1  359.32
#Mann= 3 ,-1 , 0
  4524.9      .1       0    4997     .07       0  5004.7      .1       0
Bank Sta=4997,5004.7
XS Rating Curve= 0 ,0
Exp/Cntr=0.3,0.1

Type RM Length L Ch R = 1 ,16117   ,430,430,430
BEGIN DESCRIPTION:
Prairie Creek 23.0
END DESCRIPTION:
XS GIS Cut Line= 3
      2076524.99       13413575.        2076925.       13413425.
      2077724.98     13412725.02
#Sta/Elev= 30
  4587.3  352.79  4687.9   350.3  4822.3  349.53  4883.7  347.94  4919.3  344.42
  4938.9  343.19  4950.4  341.47  4969.1  340.05  4989.3   337.7  4989.9   336.9
  4996.4   336.9    4997   337.7  5011.8   338.7  5099.5   340.2  5191.5  342.54
  5213.4  342.27  5255.1  342.93  5297.8  342.53  5326.3  343.43  5347.2  342.77
  5397.5  342.84  5645.2  345.66  5687.9  344.54    5723  345.79  5772.4  345.59
  5808.5  346.49  5843.6  348.19  5886.3  348.26  5978.3  352.43  6077.5  355.64
#Mann= 3 ,-1 , 0
  4587.3      .1       0  4989.3     .07       0    4997      .1       0
Bank Sta=4989.3,4997
XS Rating Curve= 0 ,0
Exp/Cntr=0.3,0.1

Type RM Length L Ch R = 1 ,15687   ,448,448,448
BEGIN DESCRIPTION:
Prairie Creek 22.0
END DESCRIPTION:
XS GIS Cut Line= 3
        2076675.       13414125.        2077275.       13413625.
      2077874.99     13412825.02
#Sta/Elev= 30
  4205.9  357.47  4209.2  357.47  4219.6  354.91  4233.9  352.79    4256  351.08
  4383.6  350.17  4461.7  348.53  4496.8   348.4  4646.5  345.74  4731.1  342.79
  4794.9  342.24  4866.5  340.34    4873  340.73  4880.8  339.94  4930.3   340.2
  4973.3  338.08  4983.7  336.62  4996.5  335.85  4997.2  335.05  5003.8  335.05
  5004.5  335.85  5044.2  338.99  5208.8  341.39  5329.6  340.96  5436.9   342.7
  5523.4  342.11    5565   342.5  5650.5  344.74  5873.4  353.42  5986.9  356.02
#Mann= 3 ,-1 , 0
  4205.9      .1       0  4996.5     .07       0  5004.5      .1       0
Bank Sta=4996.5,5004.5
XS Rating Curve= 0 ,0
Exp/Cntr=0.3,0.1

Type RM Length L Ch R = 1 ,15239   ,499,499,499
BEGIN DESCRIPTION:
Prairie Creek 21.0
END DESCRIPTION:
XS GIS Cut Line= 3
      2077024.97     13414325.03        2077675.       13413725.
        2077925.     13412924.99
#Sta/Elev= 30
  4094.4  352.93  4278.5  351.07    4406   348.7  4448.3  347.24  4518.9  345.77
  4533.1   344.9  4589.8  343.77  4703.2  339.71  4731.5  339.85  4844.4  338.28
  4965.1  338.24  4989.5  337.45  4995.3  337.02  5000.5  335.96  5006.5  335.84
  5007.2  335.04  5013.8  335.04  5014.5  335.84    5033  336.21  5052.4  337.94
  5092.7  337.36  5136.2  339.36    5220  339.41  5272.4  340.31  5356.2  340.32
  5408.6  341.81    5440   341.7  5492.4  342.95    5671  349.89  5817.2  354.03
#Mann= 3 ,-1 , 0
  4094.4      .1       0  5006.5     .07       0  5014.5      .1       0
Bank Sta=5006.5,5014.5
XS Rating Curve= 0 ,0
Exp/Cntr=0.3,0.1

Type RM Length L Ch R = 1 ,14740   ,291,291,291
BEGIN DESCRIPTION:
Prairie Creek 20.0
END DESCRIPTION:
XS GIS Cut Line= 3
      2077081.98     13414505.77       2077676.6     13414084.76
      2078525.02     13413474.98
#Sta/Elev= 30
  4364.3  352.96    4496  350.67  4632.7  346.79  4711.1  345.99  4754.5  344.73
  4790.2  344.77    4912  342.06  4947.7   340.9  4968.6  339.33  4977.2  337.59
  4983.4  337.56    4992  335.59  4998.2  335.59  5000.9  334.78  5001.7  333.98
  5008.6  333.98  5009.3  334.78  5054.7  337.11  5088.8  337.59  5155.5  337.59
  5291.8  339.24  5413.4  339.41  5457.5  338.81  5558.2  339.81    5600  340.96
  5620.8  340.19  5750.9  341.01  5937.6   347.1  6073.8   350.4  6137.7  351.17
#Mann= 3 ,-1 , 0
  4364.3      .1       0  5000.9     .07       0  5009.3      .1       0
Bank Sta=5000.9,5009.3
XS Rating Curve= 0 ,0
Exp/Cntr=0.3,0.1

Type RM Length L Ch R = 1 ,14449   ,619,619,619
BEGIN DESCRIPTION:
Prairie Creek 19.0
END DESCRIPTION:
XS GIS Cut Line= 3
      2077425.01     13414724.98      2077737.36     13414319.14
        2078575.       13413625.
#Sta/Elev= 30
  4517.8  350.76  4560.4  348.17  4574.9  348.26  4624.7  345.78  4753.4  341.71
  4759.7  341.08  4902.9  338.73  4923.7  337.61  4952.7  334.57  4959.4  334.31
  4967.2  335.37  4973.5  334.19    4992   332.9  4992.8   332.1  4999.7   332.1
  5000.4   332.9  5009.7  334.27  5029.4  335.53  5109.1  337.21  5207.8   337.5
  5351.4  337.45  5450.3  338.86  5557.1  337.59  5613.1  339.49  5676.9   339.5
  5705.6  338.92    5841  342.13  5890.5  344.33    5983  347.01  6117.8  350.02
#Mann= 5 ,-1 , 0
  4517.8      .1       0    4992     .07       0  5000.4      .1       0
  5009.7     .05       0  5207.8      .1       0
Bank Sta=4992,5000.4
XS Rating Curve= 0 ,0
Exp/Cntr=0.3,0.1

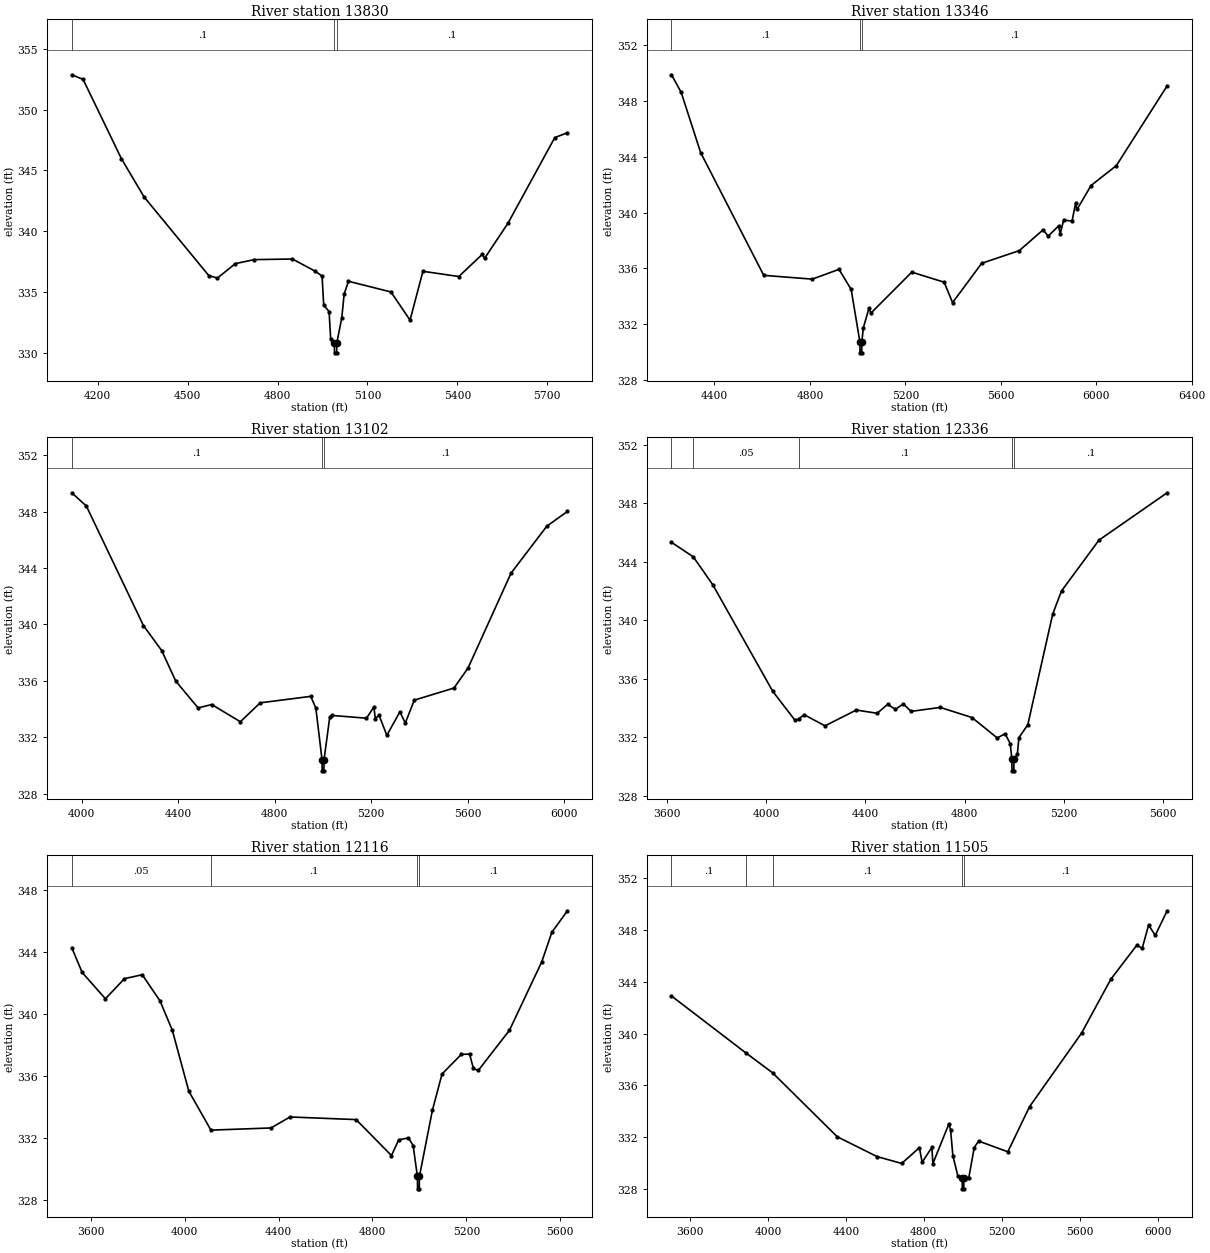
Type RM Length L Ch R = 1 ,13830   ,484,484,484
BEGIN DESCRIPTION:
Prairie Creek 18.0
END DESCRIPTION:
XS GIS Cut Line= 3
      2077375.03     13414824.99        2078175.       13414475.
        2078675.       13413875.
#Sta/Elev= 30
  4113.2  352.87    4151  352.49  4278.8  345.97  4354.5  342.82  4570.4  336.35
  4599.3  336.14  4658.9  337.33  4721.7  337.66  4849.6  337.71    4924  336.73
  4948.6  336.31    4954  333.93    4972  333.38  4977.4  331.09  4989.3  330.79
  4990.1  329.99    4997  329.99  4997.7  330.79  5014.4  332.88  5022.2  334.82
  5036.5  335.88  5178.4     335  5242.2  332.68  5285.1   336.7  5404.9  336.27
    5483  338.09  5490.8  337.76  5568.9  340.65  5725.1   347.7  5767.4   348.1
#Mann= 3 ,-1 , 0
  4113.2      .1       0  4989.3     .07       0  4997.7      .1       0
Bank Sta=4989.3,4997.7
XS Rating Curve= 0 ,0
Exp/Cntr=0.3,0.1

Type RM Length L Ch R = 1 ,13346   ,244,244,244
BEGIN DESCRIPTION:
Prairie Creek 17.0
END DESCRIPTION:
XS GIS Cut Line= 3
      2077525.03     13414974.99        2078325.       13414825.
      2079338.91     13414071.75
#Sta/Elev= 30
    4220  349.85  4260.7  348.59  4342.1  344.29  4606.6  335.51  4810.1  335.24
    4922  335.94  4972.9   334.5  5009.3  330.77  5010.1  329.97  5017.1  329.97
  5017.8  330.77  5023.7  331.74  5047.4  333.16  5055.8  332.81  5226.9  335.74
  5362.5  335.02  5397.9  333.56  5519.8  336.37  5677.5  337.28  5777.6  338.77
  5798.5  338.31  5842.3  339.05  5848.5  338.46  5863.2  339.45  5898.6   339.4
  5913.2  340.65  5919.4  340.22  5977.9  341.93  6084.3  343.36    6297  349.06
#Mann= 3 ,-1 , 0
    4220      .1       0  5009.3     .07       0  5017.8      .1       0
Bank Sta=5009.3,5017.8
XS Rating Curve= 0 ,0
Exp/Cntr=0.3,0.1

Type RM Length L Ch R = 1 ,13102   ,766,766,766
BEGIN DESCRIPTION:
Mapping XS 76cf9862
END DESCRIPTION:
XS GIS Cut Line= 4
      2077536.21     13415307.95      2078411.19     13415094.42
      2078624.73     13414753.27      2079288.79     13414401.71
#Sta/Elev= 30
  3958.8  349.33  4019.3  348.39  4256.1  339.91  4331.5  338.15  4389.9  335.98
  4482.5  334.08  4539.1  334.32  4657.5   333.1  4739.9  334.44  4949.4   334.9
  4970.6  334.06  4996.1  330.42  4996.8  329.62  5003.8  329.62  5004.6  330.42
  5028.3  333.45  5035.7  333.55  5180.4  333.35  5211.1  334.15    5217  333.33
  5232.3  333.56  5264.9  332.14  5318.8   333.8  5341.4  333.01  5378.4  334.63
  5543.1  335.49  5601.7  336.92  5779.5  343.63  5927.8  346.96  6013.3  348.01
#Mann= 3 ,-1 , 0
  3958.8      .1       0  4996.1     .07       0  5004.6      .1       0
Bank Sta=4996.1,5004.6
XS Rating Curve= 0 ,0
Exp/Cntr=0.3,0.1

Type RM Length L Ch R = 1 ,12336   ,220,220,220
BEGIN DESCRIPTION:
Prairie Creek 16.0
END DESCRIPTION:
XS GIS Cut Line= 3
      2077706.94     13415504.05        2079025.       13415075.
      2079382.33     13414579.55
#Sta/Elev= 30
  3618.6  345.34  3706.3  344.35  3784.8  342.44  4026.7  335.14  4116.2  333.16
  4130.4  333.25  4153.4  333.54    4237  332.78  4363.2  333.86  4447.4  333.64
  4489.4  334.25    4521  333.91  4552.5  334.28  4584.1  333.77  4701.4  334.04
  4829.1  333.35  4931.1  331.95  4962.7  332.24  4983.5  331.56  4989.9   330.5
  4990.7   329.7  4997.8   329.7  4998.5   330.5  5012.1  330.83  5018.3  331.97
  5054.1  332.85  5154.4  340.42    5190  342.01  5340.9  345.49  5615.6  348.73
#Mann= 5 ,-1 , 0
  3618.6      .1       0  3706.3     .05       0  4130.4      .1       0
  4989.9     .07       0  4998.5      .1       0
Bank Sta=4989.9,4998.5
XS Rating Curve= 0 ,0
Exp/Cntr=0.3,0.1

Type RM Length L Ch R = 1 ,12116   ,611,611,611
BEGIN DESCRIPTION:
Prairie Creek 15.0
END DESCRIPTION:
XS GIS Cut Line= 3
      2077733.03     13415799.17      2078770.35     13415347.78
      2079725.02       13415125.
#Sta/Elev= 30
  3518.9  344.31  3563.1  342.71  3662.3  341.01  3743.5  342.31  3819.3  342.56
    3895  340.87  3947.4  338.97  4017.7  335.04  4111.8  332.53  4367.6  332.67
  4448.8  333.38  4730.2  333.21  4880.9  330.89  4911.7   331.9  4953.2  332.03
  4973.3  331.53  4991.4  329.54  4992.1  328.74  4999.2  328.74    5000  329.54
  5055.4  333.82  5096.5  336.16  5178.7  337.42  5213.5  337.44    5230  336.51
  5250.5  336.38  5383.7  338.98  5521.6  343.41  5564.1   345.3  5630.5  346.69
#Mann= 4 ,-1 , 0
  3518.9     .05       0  4111.8      .1       0  4991.4     .07       0
    5000      .1       0
Bank Sta=4991.4,5000
XS Rating Curve= 0 ,0
Exp/Cntr=0.3,0.1

Type RM Length L Ch R = 1 ,11505   ,287,287,287
BEGIN DESCRIPTION:
Prairie Creek 14.0
END DESCRIPTION:
XS GIS Cut Line= 3
      2077680.93     13416241.88        2079125.       13415775.
      2080039.77     13415309.88
#Sta/Elev= 30
  3505.3   342.9  3890.2  338.47  4024.1  336.97  4356.1  332.03  4560.5   330.5
  4686.8  329.97  4777.6  331.19  4791.8  330.06  4841.6  331.21  4846.9  329.96
  4928.4     333  4937.7  332.58  4949.4  330.57  4974.9  329.02  4997.4  328.81
  4998.2  328.01  5005.3  328.01    5006  328.81  5031.3  328.88  5059.2   331.2
  5081.4   331.7  5231.5  330.87  5342.8  334.35  5609.8  340.03  5759.9  344.19
  5893.4  346.82  5921.3  346.59  5954.1  348.38  5988.1  347.58  6049.2  349.48
#Mann= 5 ,-1 , 0
  3505.3      .1       0  3890.2     .05       0  4024.1      .1       0
  4997.4     .07       0    5006      .1       0
Bank Sta=4997.4,5006
XS Rating Curve= 0 ,0
Exp/Cntr=0.3,0.1