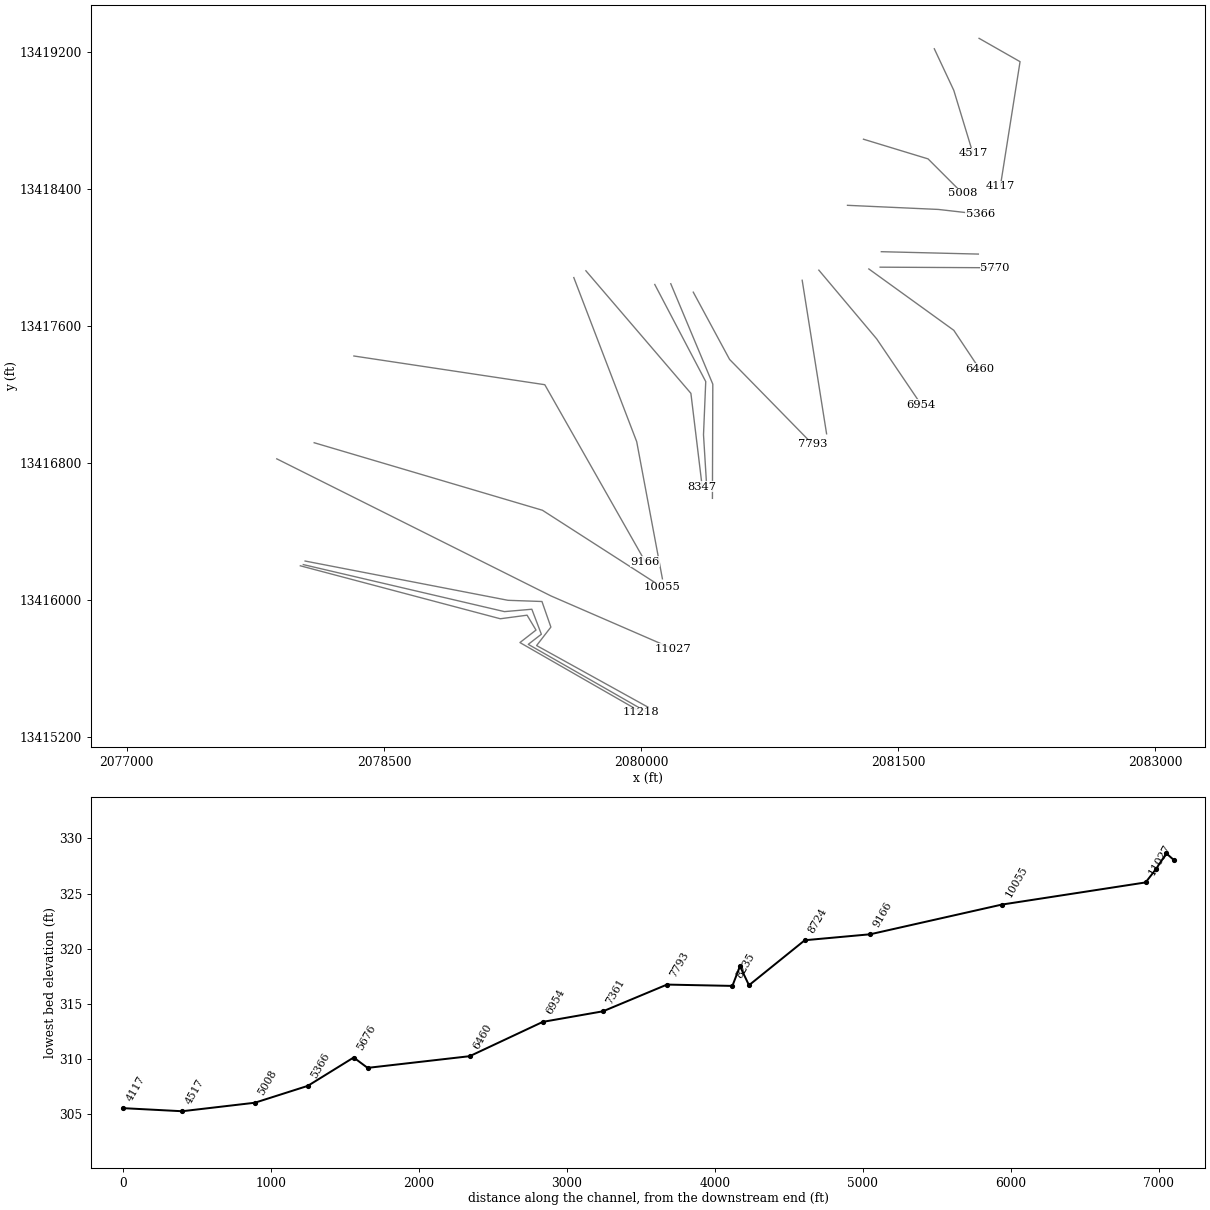
HEC-RAS study Prairie Creek.prj: Prairie Creek Base Level Engineering

--- Prairie Creek.g01 (geometry) --- (continued)

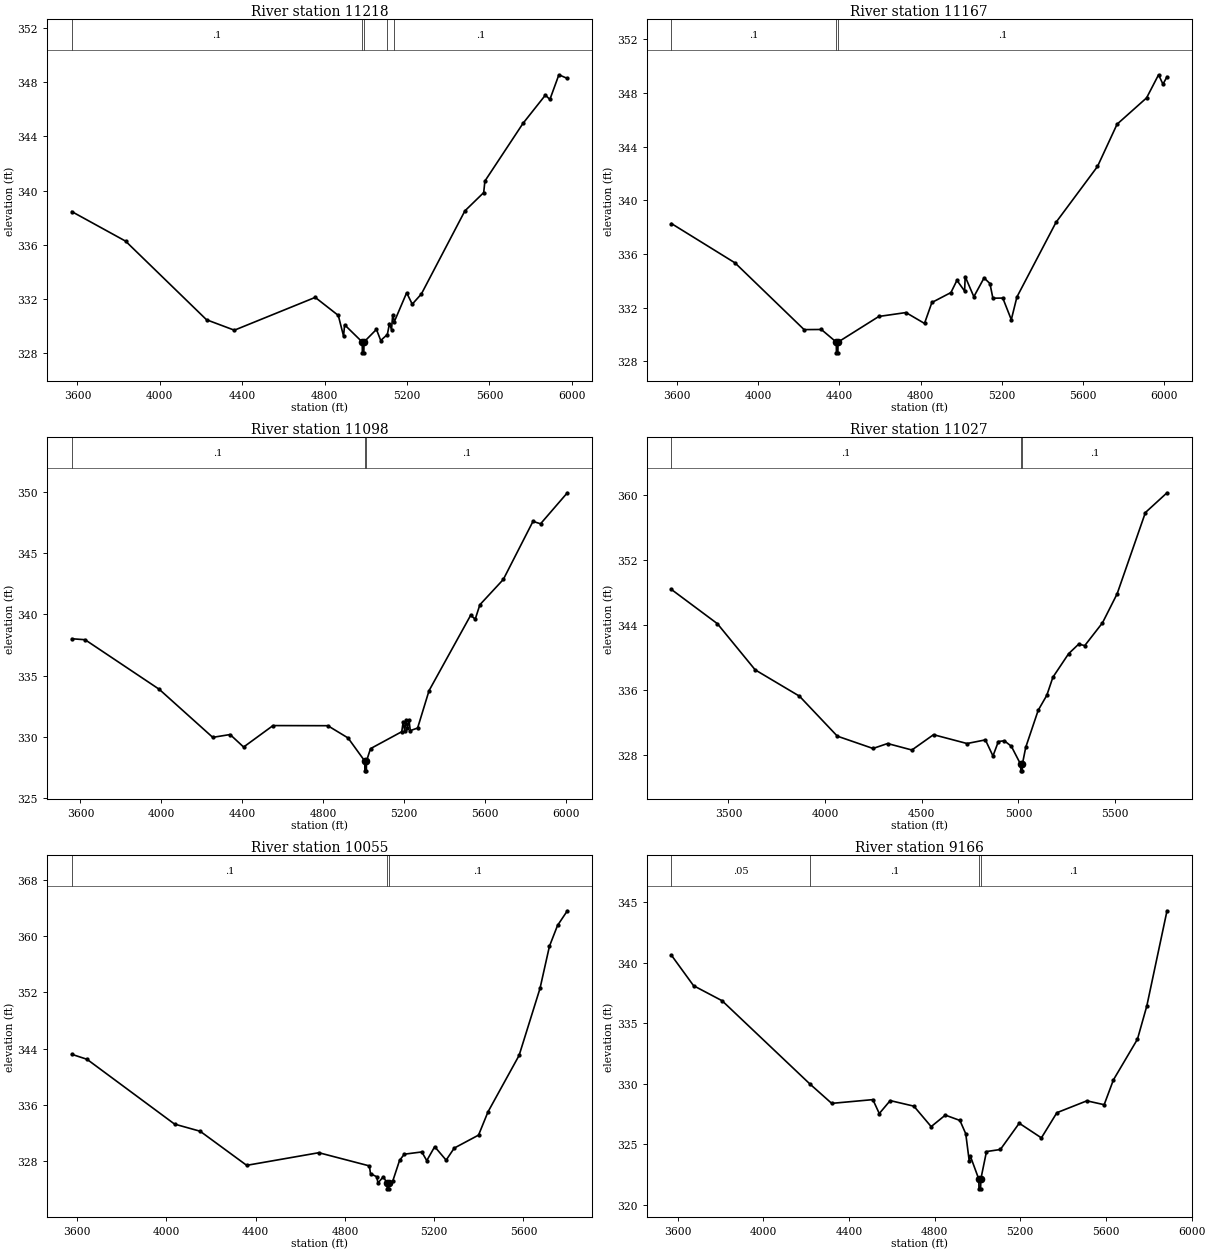
Type RM Length L Ch R = 1 ,11218   ,51,51,51
BEGIN DESCRIPTION:
Mapping XS b5cebf7c
END DESCRIPTION:
XS GIS Cut Line= 6
      2078012.48     13416200.96      2079179.12     13415891.93
      2079335.37     13415912.77      2079387.46     13415825.96
      2079293.71     13415753.04        2080001.     13415347.36
#Sta/Elev= 30
  3572.6  338.46  3833.8  336.28  4226.9  330.48    4362  329.71  4754.5  332.13
  4866.5   330.8  4892.1  329.27  4897.1  330.11  4982.6  328.84  4983.3  328.04
  4990.5  328.04  4991.3  328.84  5051.7  329.77  5072.5  328.95  5104.6  329.39
    5115   330.2  5124.8  329.75  5130.6  330.84  5138.8  330.35  5198.4  332.47
  5225.5  331.63  5269.8  332.38  5481.1  338.51  5572.4  339.86  5578.2  340.71
  5762.9  344.96  5871.9  347.05  5893.7  346.73  5937.4  348.55  5978.5  348.28
#Mann= 5 ,-1 , 0
  3572.6      .1       0  4982.6     .07       0  4991.3      .1       0
  5104.6     .05       0  5138.8      .1       0
Bank Sta=4982.6,4991.3
XS Rating Curve= 0 ,0
Exp/Cntr=0.3,0.1

Type RM Length L Ch R = 1 ,11167   ,69,69,69
BEGIN DESCRIPTION:
Mapping XS 9435d684
END DESCRIPTION:
XS GIS Cut Line= 6
      2078029.79     13416207.91      2079203.43      13415933.6
      2079363.15     13415947.49      2079418.71     13415801.65
      2079342.32     13415742.63      2080047.09      13415339.9
#Sta/Elev= 30
  3572.5  338.27  3885.9  335.34  4226.2  330.37  4311.2  330.38  4384.8  329.44
  4385.5  328.64  4392.7  328.64  4393.5  329.44  4594.5  331.35    4728  331.64
  4819.5  330.83  4855.8  332.39  4949.7  333.13  4979.3  334.04  5017.1  333.24
  5019.8  334.32  5062.6  332.82  5112.9  334.22  5141.9   333.8  5156.4  332.71
  5205.2  332.72  5247.1  331.11  5274.8   332.8  5467.4  338.36  5671.8  342.52
  5768.3  345.67  5913.7  347.63  5972.7  349.35  5994.3  348.65  6014.3   349.2
#Mann= 3 ,-1 , 0
  3572.5      .1       0  4384.8     .07       0  4393.5      .1       0
Bank Sta=4384.8,4393.5
XS Rating Curve= 0 ,0
Exp/Cntr=0.3,0.1

Type RM Length L Ch R = 1 ,11098   ,71,71,71
BEGIN DESCRIPTION:
Mapping XS dab2810d
END DESCRIPTION:
XS GIS Cut Line= 6
      2078040.26     13416228.73      2079224.26     13415999.57
      2079422.18     13415992.63      2079474.26     13415843.32
      2079390.93     13415735.68      2080043.71     13415374.57
#Sta/Elev= 30
    3557  338.01  3622.9  337.93  3989.6  333.89  4254.4  329.97  4340.4   330.2
  4407.2  329.18  4552.6  330.93  4823.7  330.92  4923.9  329.92  5006.4  328.04
  5007.2  327.24  5014.4  327.24  5015.1  328.04    5035  329.05  5189.5  330.43
  5196.8  331.26  5203.7  330.51  5210.9  331.35  5217.8  330.75  5225.1  331.38
    5232  330.52    5268  330.73  5324.6  333.78  5530.3  339.92  5553.1  339.61
    5576  340.78  5691.8  342.84  5838.8  347.58  5876.2  347.38  6008.8  349.91
#Mann= 3 ,-1 , 0
    3557      .1       0  5006.4     .07       0  5015.1      .1       0
Bank Sta=5006.4,5015.1
XS Rating Curve= 0 ,0
Exp/Cntr=0.3,0.1

Type RM Length L Ch R = 1 ,11027   ,972,972,972
BEGIN DESCRIPTION:
Prairie Creek 13.0
END DESCRIPTION:
XS GIS Cut Line= 3
        2077875.       13416825.        2079475.       13416025.
      2080185.32     13415716.69
#Sta/Elev= 30
  3204.9  348.39  3442.5  344.17  3638.1  338.47  3867.3  335.22    4063  330.29
  4247.5  328.77  4322.9  329.38  4448.7  328.58  4560.5  330.47  4733.8  329.38
  4828.8  329.83    4868  327.84  4895.9  329.63  4926.7  329.72    4963  329.04
  5011.2  326.81    5012  326.01  5019.2  326.01  5019.9  326.81  5037.4  328.91
    5102  333.49  5146.4  335.33  5177.9  337.56  5259.1  340.46  5311.5  341.65
  5342.6  341.46  5434.3  344.27  5510.1  347.85  5656.3  357.88  5768.1  360.32
#Mann= 3 ,-1 , 0
  3204.9      .1       0  5011.2     .07       0  5019.9      .1       0
Bank Sta=5011.2,5019.9
XS Rating Curve= 0 ,0
Exp/Cntr=0.3,0.1

Type RM Length L Ch R = 1 ,10055   ,889,889,889
BEGIN DESCRIPTION:
Prairie Creek 12.0
END DESCRIPTION:
XS GIS Cut Line= 3
      2078093.26     13416918.96        2079425.       13416525.
      2080125.04     13416074.98
#Sta/Elev= 30
  3575.9  343.18  3644.1  342.47  4036.6  333.23  4151.3  332.21  4359.8  327.35
  4683.1  329.15  4909.6  327.27  4914.8  326.16  4942.8  325.72  4948.1  324.83
  4972.3  325.73    4989   324.8  4989.8     324    4997     324  4997.8   324.8
  5014.6  325.12  5044.9  328.05  5066.1  328.94  5144.7  329.26  5166.8  328.02
  5202.4  330.01  5253.6  328.09    5290  329.81  5398.9  331.66  5441.2  334.97
  5580.6  343.02  5674.3  352.57  5716.6  358.58  5752.9  361.55  5796.9  363.64
#Mann= 3 ,-1 , 0
  3575.9      .1       0    4989     .07       0  4997.8      .1       0
Bank Sta=4989,4997.8
XS Rating Curve= 0 ,0
Exp/Cntr=0.3,0.1

Type RM Length L Ch R = 1 ,9166    ,442,442,442
BEGIN DESCRIPTION:
Prairie Creek 11.0
END DESCRIPTION:
XS GIS Cut Line= 3
      2078324.98       13417425.      2079438.75     13417257.51
      2080024.98     13416225.03
#Sta/Elev= 30
  3571.3  340.61  3674.8  338.09  3807.8  336.85  4218.5  329.96  4319.6  328.37
  4511.8  328.68  4541.7  327.53  4592.7   328.6  4703.2  328.14  4783.9  326.45
    4850   327.4  4918.1  326.96  4945.4  325.86  4961.3  323.65  4967.1     324
  5006.3  322.11  5007.2  321.31  5014.8  321.31  5015.7  322.11  5042.1  324.39
    5107  324.56    5195  326.73  5298.5  325.52  5370.8   327.6  5510.7  328.58
  5591.5  328.26  5634.7  330.31  5746.9  333.67  5790.5  336.41  5884.9  344.28
#Mann= 4 ,-1 , 0
  3571.3     .05       0  4218.5      .1       0  5006.3     .07       0
  5015.7      .1       0
Bank Sta=5006.3,5015.7
XS Rating Curve= 0 ,0
Exp/Cntr=0.3,0.1

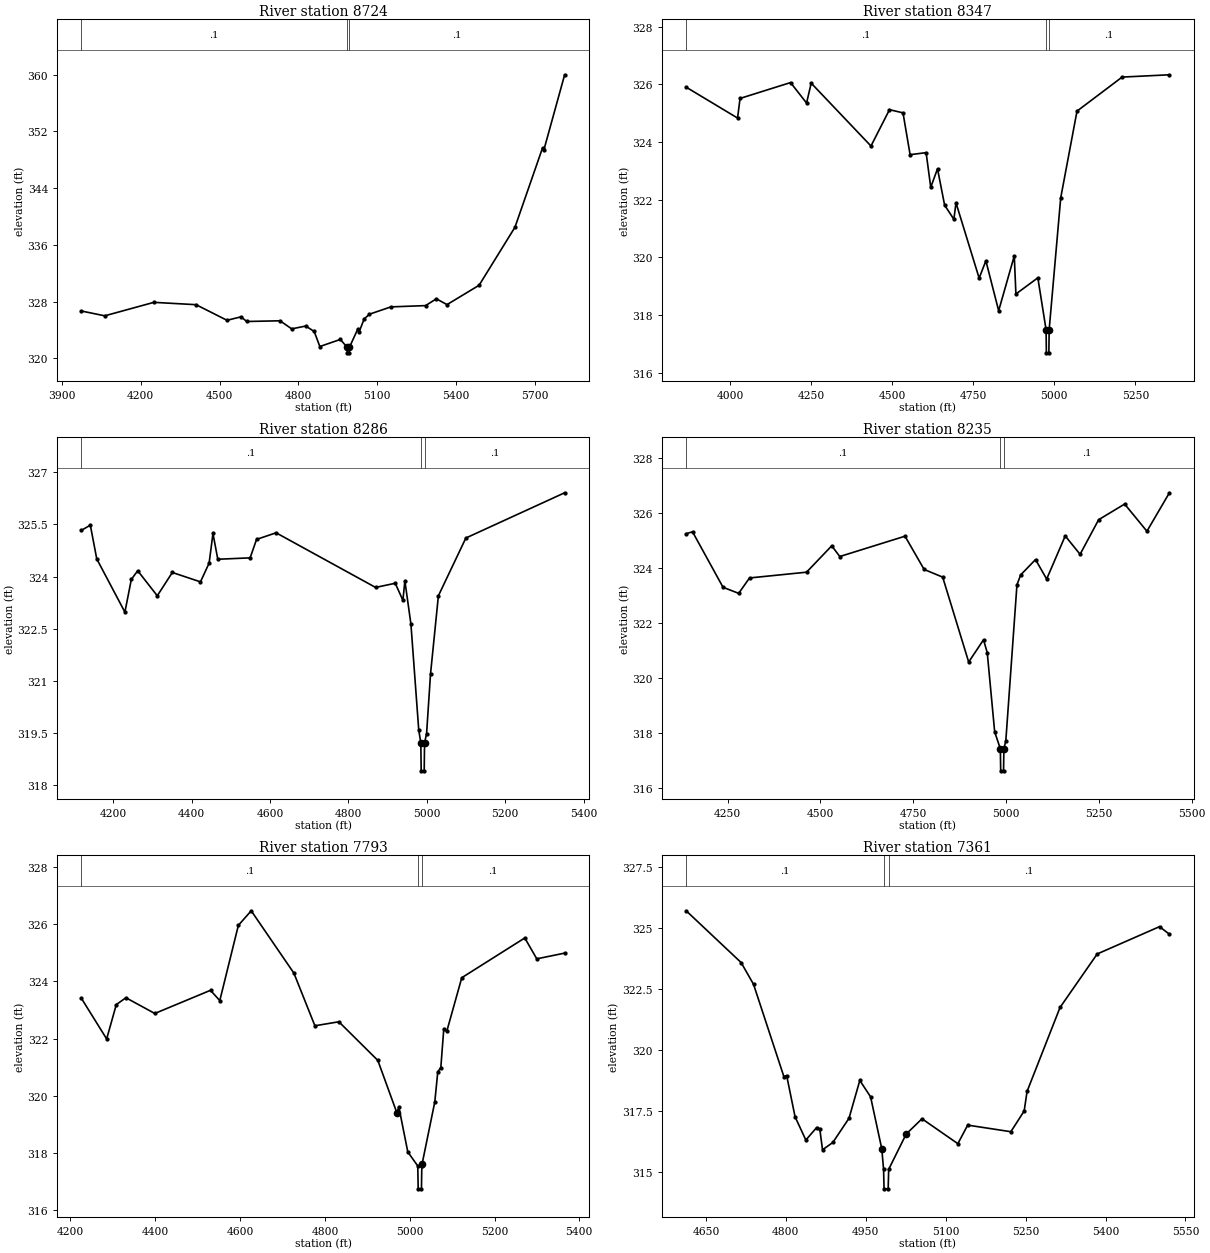
Type RM Length L Ch R = 1 ,8724    ,377,377,377
BEGIN DESCRIPTION:
Prairie Creek 10.0
END DESCRIPTION:
XS GIS Cut Line= 3
      2079608.02     13417882.51        2079975.       13416925.
      2080125.01     13416124.97
#Sta/Elev= 30
  3974.1  326.67    4063  325.99  4249.9  327.89  4410.5  327.56  4528.3  325.36
  4581.9  325.85  4603.3  325.19  4730.3  325.29  4774.6  324.15  4828.2  324.55
  4860.3  323.78  4881.7  321.66  4959.8  322.66  4985.2  321.57  4986.1  320.77
  4993.7  320.77  4994.6  321.57  5025.8   324.1  5030.9  323.69  5050.4  325.55
  5070.7  326.22  5152.1  327.25  5284.4  327.43  5325.1  328.39  5365.8  327.57
  5487.9   330.3  5624.4  338.48  5729.5  349.68  5734.6   349.4  5813.5  359.98
#Mann= 3 ,-1 , 0
  3974.1      .1       0  4985.2     .07       0  4994.6      .1       0
Bank Sta=4985.2,4994.6
XS Rating Curve= 0 ,0
Exp/Cntr=0.3,0.1

Type RM Length L Ch R = 1 ,8347    ,61,61,61
BEGIN DESCRIPTION:
Prairie Creek 9.0
END DESCRIPTION:
XS GIS Cut Line= 3
      2079678.47     13417922.23      2080291.18     13417207.16
      2080357.16     13416662.01
#Sta/Elev= 30
  3864.3   325.9  4022.8  324.83  4030.5  325.51  4186.3  326.06  4235.7  325.35
    4250  326.04  4434.4  323.86  4491.5  325.12  4533.2  325.01  4555.1  323.56
  4604.5  323.63  4618.8  322.43  4639.7  323.07  4661.6  321.81  4690.1  321.32
  4696.7  321.89  4768.1  319.28  4788.9  319.88  4828.3  318.15  4876.5  320.05
  4881.5  318.73  4949.2  319.29  4974.6  317.49  4975.5  316.69  4983.2  316.69
  4984.1  317.49  5019.7  322.06    5070  325.07  5209.2  326.25  5355.1  326.33
#Mann= 3 ,-1 , 0
  3864.3      .1       0  4974.6     .07       0  4984.1      .1       0
Bank Sta=4974.6,4984.1
XS Rating Curve= 0 ,0
Exp/Cntr=0.3,0.1

Type RM Length L Ch R = 1 ,8286    ,51,51,51
BEGIN DESCRIPTION:
Mapping XS 96a97ee7
END DESCRIPTION:
XS GIS Cut Line= 4
      2080080.46     13417842.24      2080377.77     13417275.84
      2080364.75     13416965.51       2080382.1     13416683.43
#Sta/Elev= 30
  4118.8  325.33  4141.6  325.48    4158  324.51  4229.8  322.98  4246.2  323.92
  4262.5  324.17  4312.4  323.45  4350.8  324.12  4422.6  323.85  4444.7  324.39
  4454.5  325.24  4466.8   324.5  4549.3  324.54  4565.7  325.07  4615.5  325.26
  4869.4  323.69  4919.5  323.81  4939.1  323.32  4944.1  323.88  4959.5  322.64
  4979.5  319.59  4984.8  319.22  4985.7  318.42  4993.4  318.42  4994.3  319.22
  4999.5  319.49  5009.5   321.2  5029.6  323.45  5099.7  325.11  5351.7  326.41
#Mann= 3 ,-1 , 0
  4118.8      .1       0  4984.8     .07       0  4994.3      .1       0
Bank Sta=4984.8,4994.3
XS Rating Curve= 0 ,0
Exp/Cntr=0.3,0.1

Type RM Length L Ch R = 1 ,8235    ,442,442,442
BEGIN DESCRIPTION:
Mapping XS 92fadee9
END DESCRIPTION:
XS GIS Cut Line= 3
      2080173.77     13417846.59        2080419.     13417260.65
      2080416.83     13416594.44
#Sta/Elev= 30
  4138.7  325.26  4155.8  325.33    4238  323.31  4280.1  323.09  4309.3  323.65
  4462.9  323.86  4530.7  324.82  4552.4  324.43    4728  325.17  4779.5  323.96
  4829.5  323.68  4899.5  320.59  4939.5   321.4  4949.5  320.93  4969.5  318.05
  4984.8  317.43  4985.7  316.63  4993.4  316.63  4994.3  317.43  4999.5  317.72
  5029.5   323.4  5039.5  323.76  5079.5  324.32  5109.5  323.61  5159.5  325.18
  5199.5  324.51  5249.5  325.77  5319.5  326.34  5379.5  325.35  5440.1  326.75
#Mann= 3 ,-1 , 0
  4138.7      .1       0  4984.8     .07       0  4994.3      .1       0
Bank Sta=4984.8,4994.3
XS Rating Curve= 0 ,0
Exp/Cntr=0.3,0.1

Type RM Length L Ch R = 1 ,7793    ,432,432,432
BEGIN DESCRIPTION:
Mapping XS c1ca326b
END DESCRIPTION:
XS GIS Cut Line= 3
      2080305.08     13417797.42      2080516.88     13417405.07
      2081002.27     13416909.28
#Sta/Elev= 30
  4225.7  323.41  4285.3  321.99    4308  323.19  4330.7  323.43  4398.8  322.88
  4530.2  323.69  4552.1  323.33  4595.9  325.96  4626.2  326.47  4726.9  324.29
  4776.4  322.45  4832.9  322.59  4924.8  321.24 4969.79319.4051  4974.4  319.61
  4995.5  318.04    5019  317.55    5020  316.75  5027.7  316.75  5028.6  317.55
 5029.17317.6141  5059.2  319.79  5066.2  320.84  5073.4  320.99  5080.4  322.35
  5087.5  322.26  5122.8  324.13  5271.4  325.52  5299.7  324.79  5365.4  324.99
#Mann= 3 ,-1 , 0
  4225.7      .1       0    5019     .07       0  5028.6      .1       0
Bank Sta=4969.79,5029.17
XS Rating Curve= 0 ,0
Exp/Cntr=0.3,0.1

Type RM Length L Ch R = 1 ,7361    ,407,407,407
BEGIN DESCRIPTION:
Mapping XS 1843b75a
END DESCRIPTION:
XS GIS Cut Line= 2
      2080940.49     13417866.84      2081082.84     13416971.08
#Sta/Elev= 30
  4612.9  325.72    4716   323.6  4739.3  322.71  4796.4  318.92  4801.5  318.97
  4817.3  317.28  4837.5  316.33  4857.8  316.84  4863.7  316.78  4868.8  315.93
  4888.2  316.23  4918.5  317.22  4938.8  318.77    4959   318.1 4980.08 315.964
  4983.4  315.13  4984.3  314.33    4992  314.33    4993  315.13 5025.79 316.572
  5055.5   317.2  5122.8  316.18  5141.3  316.94  5222.3  316.67  5247.3  317.52
  5252.7  318.32  5314.6  321.76  5384.3  323.95  5501.3  325.07  5519.9  324.76
#Mann= 3 ,-1 , 0
  4612.9      .1       0  4983.4     .07       0    4993      .1       0
Bank Sta=4980.08,5025.79
XS Rating Curve= 0 ,0
Exp/Cntr=0.3,0.1

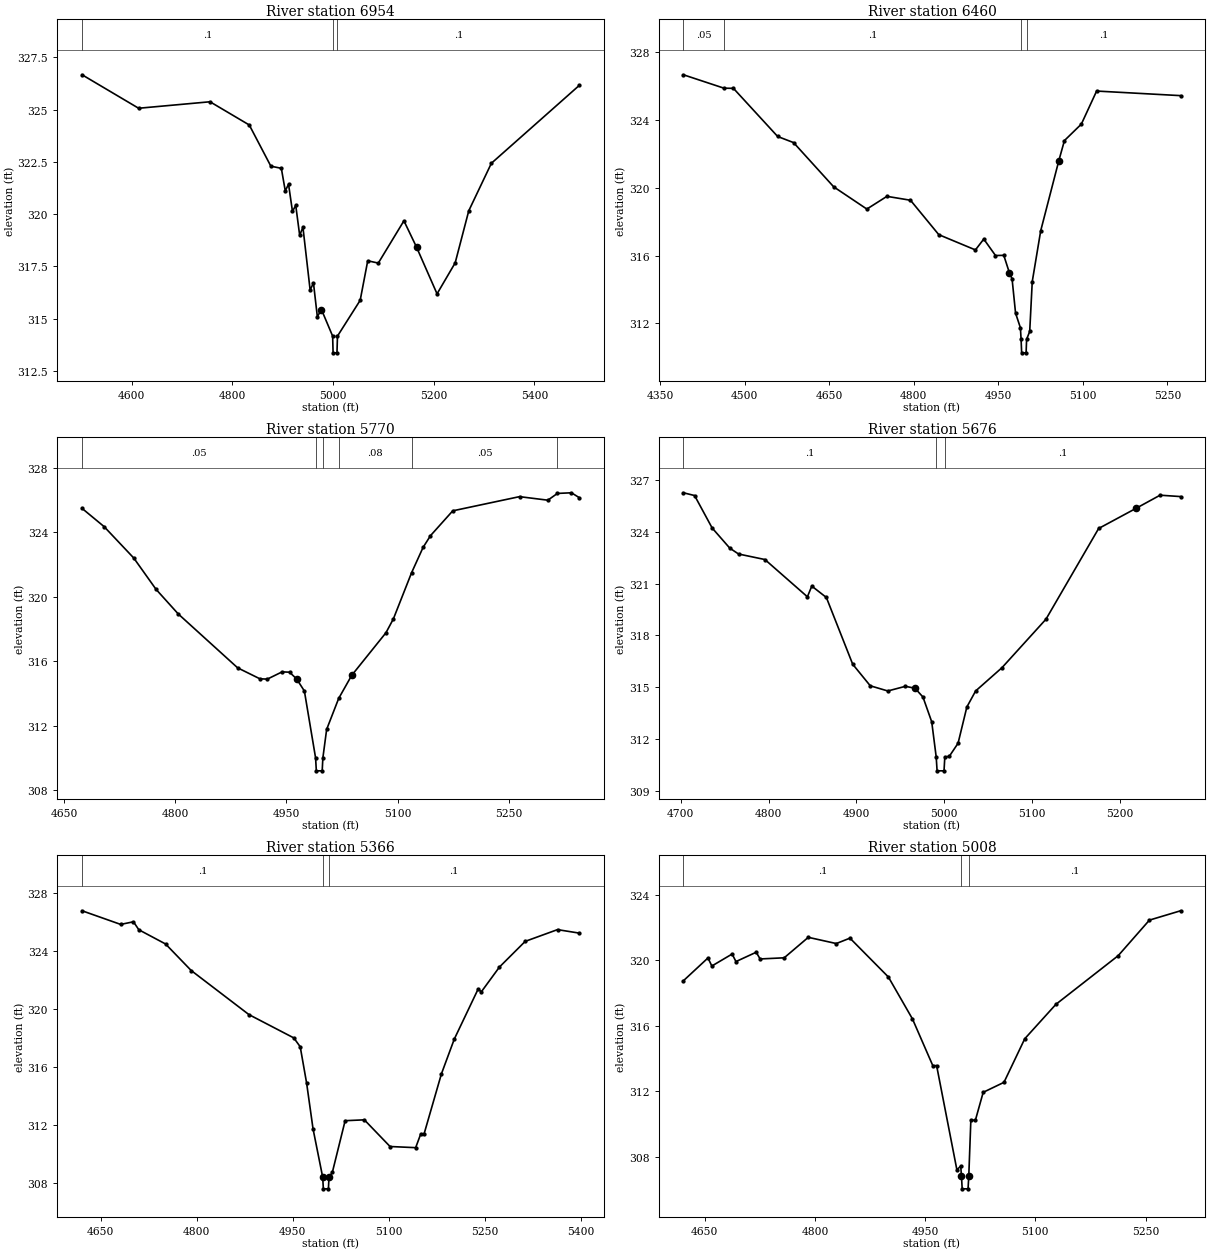
Type RM Length L Ch R = 1 ,6954    ,494,494,494
BEGIN DESCRIPTION:
Prairie Creek 8.0
END DESCRIPTION:
XS GIS Cut Line= 3
       2081037.7     13417925.92        2081375.       13417525.
      2081634.94     13417141.17
#Sta/Elev= 30
  4501.6  326.66  4613.9  325.06  4755.7  325.37  4833.7  324.26  4876.6  322.29
  4897.4  322.19  4905.2  321.11  4911.7  321.43  4919.5  320.13    4926  320.42
  4933.8  318.99  4940.3  319.37  4954.6  316.37  4961.2  316.71  4968.9   315.1
 4977.11 315.436  4999.3  314.17  5000.2  313.37  5007.9  313.37  5008.9  314.17
    5054  315.88    5069  317.77    5090  317.66  5140.9  319.68  5165.9318.4247
  5206.7  316.19  5242.7  317.67  5269.7  320.16  5314.6  322.43  5489.1  326.15
#Mann= 3 ,-1 , 0
  4501.6      .1       0  4999.3     .07       0  5008.9      .1       0
Bank Sta=4977.11,5165.9
XS Rating Curve= 0 ,0
Exp/Cntr=0.3,0.1

Type RM Length L Ch R = 1 ,6460    ,690,690,690
BEGIN DESCRIPTION:
Prairie Creek 7.0
END DESCRIPTION:
XS GIS Cut Line= 3
       2081329.4     13417932.83        2081825.       13417575.
      2081975.04     13417349.78
#Sta/Elev= 30
  4391.4  326.66  4463.3  325.87  4480.1  325.86  4558.6  323.02  4586.8  322.66
    4658  320.05  4716.8  318.74  4752.4  319.49  4794.2  319.26  4844.4  317.23
  4909.4  316.33  4924.2  316.97    4945     316  4959.7  316.01 4969.76314.9739
  4974.4  314.63  4980.6   312.6  4989.2  311.74  4990.4  311.06  4991.4  310.26
  4999.3  310.26  5000.2  311.06  5005.7  311.52  5010.2  314.46  5025.2  317.46
 5057.32321.5901  5067.3  322.78  5097.3  323.75  5124.4   325.7  5273.3  325.43
#Mann= 4 ,-1 , 0
  4391.4     .05       0  4463.3      .1       0  4990.4     .07       0
  5000.2      .1       0
Bank Sta=4969.76,5057.32
XS Rating Curve= 0 ,0
Exp/Cntr=0.3,0.1

Type RM Length L Ch R = 1 ,5770    ,94,94,94
BEGIN DESCRIPTION:
Mapping XS 6b48b6e1
END DESCRIPTION:
XS GIS Cut Line= 2
       2081395.3     13417943.27      2082065.49      13417939.8
#Sta/Elev= 30
  4674.5  325.48  4704.2  324.35  4744.2   322.4  4774.2  320.46  4804.2  318.93
  4884.2  315.59  4914.2  314.91  4924.2  314.89  4944.2  315.34  4954.2  315.32
 4963.77314.8989  4974.2  314.15  4989.3     310  4990.3   309.2  4998.2   309.2
  4999.1     310  5004.2  311.77  5020.4  313.69 5037.97315.1226  5084.2  317.77
  5094.2  318.63  5118.7  321.49  5134.2  323.06  5144.2  323.79  5174.2  325.33
  5264.2  326.21  5302.4  325.99  5315.3  326.41  5334.2  326.45  5344.7  326.15
#Mann= 6 ,-1 , 0
  4674.5     .05       0  4989.3     .04       0  4999.1     .05       0
  5020.4     .08       0  5118.7     .05       0  5315.3     .08       0
Bank Sta=4963.77,5037.97
XS Rating Curve= 0 ,0
Exp/Cntr=0.3,0.1

Type RM Length L Ch R = 1 ,5676    ,310,310,310
BEGIN DESCRIPTION:
Mapping XS a1dbe49a
END DESCRIPTION:
XS GIS Cut Line= 2
      2081402.26     13418033.55      2081968.29     13418019.66
#Sta/Elev= 30
  4703.1  326.26  4715.8   326.1  4735.8  324.22  4755.9  323.05  4765.9  322.71
  4795.9  322.39  4844.3  320.23  4849.3  320.85  4865.9  320.19  4895.9  316.32
  4915.9  315.07  4935.9  314.77  4955.9  315.04 4966.82314.9285  4975.9  314.42
  4985.9  312.98    4991  310.94    4992  310.14  4999.9  310.14  5000.8  310.94
  5005.9  310.98  5015.9  311.74  5025.9  313.84  5035.9  314.77  5065.9  316.12
    5116  318.93    5176  324.19 5218.64325.3592    5246  326.12  5269.3  326.04
#Mann= 3 ,-1 , 0
  4703.1      .1       0    4991     .07       0  5000.8      .1       0
Bank Sta=4966.82,5218.64
XS Rating Curve= 0 ,0
Exp/Cntr=0.3,0.1

Type RM Length L Ch R = 1 ,5366    ,358,358,358
BEGIN DESCRIPTION:
Prairie Creek 6.0
END DESCRIPTION:
XS GIS Cut Line= 3
      2081204.84     13418304.17      2081735.63     13418280.07
      2081978.71     13418252.29
#Sta/Elev= 30
  4621.2  326.75  4681.4  325.81  4701.4  325.99  4709.8  325.44  4751.5  324.46
  4791.5  322.63  4881.6  319.59  4951.7  317.98  4961.7  317.37  4971.7  314.86
  4981.7  311.71  4996.8  308.37  4997.8  307.57  5005.7  307.57  5006.6  308.37
  5011.8   308.7  5031.8  312.27  5061.8  312.33  5101.9  310.49  5141.9  310.41
  5149.7  311.34  5155.1  311.37  5182.1   315.5  5202.2   317.9  5239.4  321.35
  5244.4  321.16  5272.7  322.87  5312.9  324.64  5363.3  325.45  5397.2  325.21
#Mann= 3 ,-1 , 0
  4621.2      .1       0  4996.8     .07       0  5006.6      .1       0
Bank Sta=4996.8,5006.6
XS Rating Curve= 0 ,0
Exp/Cntr=0.3,0.1

Type RM Length L Ch R = 1 ,5008    ,491,491,491
BEGIN DESCRIPTION:
Prairie Creek 5.0
END DESCRIPTION:
XS GIS Cut Line= 3
      2081298.15     13418689.79        2081675.       13418575.
      2081875.01     13418374.99
#Sta/Elev= 30
  4620.9  318.74  4654.3  320.13  4659.6  319.64  4687.2  320.37  4692.4  319.91
    4720  320.48  4725.3  320.07  4758.1  320.14  4790.9  321.39    4829  321.01
  4847.6  321.34  4899.9  318.97  4932.7  316.41  4960.4  313.56  4965.6  313.56
  4993.2   307.2  4998.4  307.43  4999.4  306.84  5000.4  306.04  5008.4  306.04
  5009.4  306.84  5012.2  310.23  5018.4  310.23    5029  311.93  5057.3  312.54
  5085.6   315.2    5128   317.3  5212.8  320.27  5255.3  322.44  5297.7  323.01
#Mann= 3 ,-1 , 0
  4620.9      .1       0  4999.4     .07       0  5009.4      .1       0
Bank Sta=4999.4,5009.4
XS Rating Curve= 0 ,0
Exp/Cntr=0.3,0.1

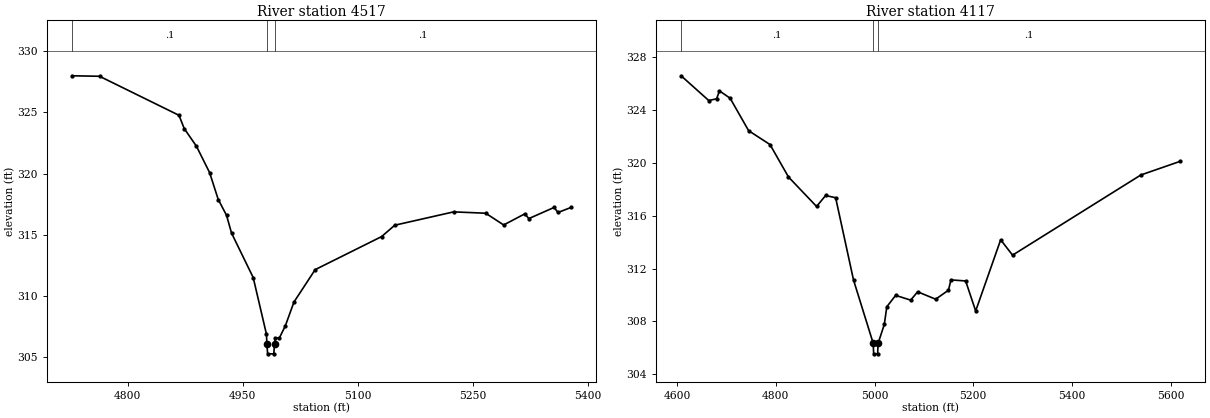
Type RM Length L Ch R = 1 ,4517    ,400,400,400
BEGIN DESCRIPTION:
Prairie Creek 4.0
END DESCRIPTION:
XS GIS Cut Line= 3
      2081711.32     13419217.57        2081825.       13418975.
      2081936.47     13418608.25
#Sta/Elev= 30
  4727.1  327.99  4763.1  327.95  4866.7  324.76  4873.5  323.68  4889.5  322.23
  4906.6  320.08  4917.9  317.88  4928.7  316.59  4935.2  315.14  4963.5   311.5
  4980.8  306.86  4981.3  306.07  4982.3  305.27  4990.3  305.27  4991.3  306.07
  4992.2  306.57  4997.6  306.57  5005.4  307.56  5016.6   309.5  5044.3  312.15
  5130.9  314.85  5148.1  315.78  5224.9  316.87  5266.7  316.76  5290.1   315.8
  5317.7  316.71  5322.9  316.32  5355.8  317.23    5361  316.82  5378.3  317.24
#Mann= 3 ,-1 , 0
  4727.1      .1       0  4981.3     .07       0  4991.3      .1       0
Bank Sta=4981.3,4991.3
XS Rating Curve= 0 ,0
Exp/Cntr=0.3,0.1

Type RM Length L Ch R = 1 ,4117    ,0,0,0
BEGIN DESCRIPTION:
Mapping XS 6829a708
END DESCRIPTION:
XS GIS Cut Line= 3
       2081972.5     13419278.41      2082211.65     13419142.22
      2082096.73     13418415.46
#Sta/Elev= 30
  4608.4  326.57  4664.4   324.7  4680.3  324.83  4686.1  325.43  4707.7  324.87
  4745.1  322.42  4788.4  321.37  4825.8  318.92  4882.7  316.69    4901  317.52
  4921.3  317.35  4957.5  311.13  4997.3  306.35  4998.3  305.55  5006.3  305.55
  5007.3  306.35  5019.8  307.77  5024.9  309.11  5042.8  309.97  5073.2  309.61
  5087.3  310.24  5123.8  309.68  5149.7  310.36  5154.7  311.14  5184.5  311.06
  5204.8  308.79  5255.4  314.17  5279.5  313.01  5539.2  319.07  5619.4  320.11
#Mann= 3 ,-1 , 0
  4608.4      .1       0  4997.3     .07       0  5007.3      .1       0
Bank Sta=4997.3,5007.3
XS Rating Curve= 0 ,0
Exp/Cntr=0.3,0.1
LCMann Table=0

Chan Stop Cuts=-1
Use User Specified Reach Order=0
Composite Channel Slope=5