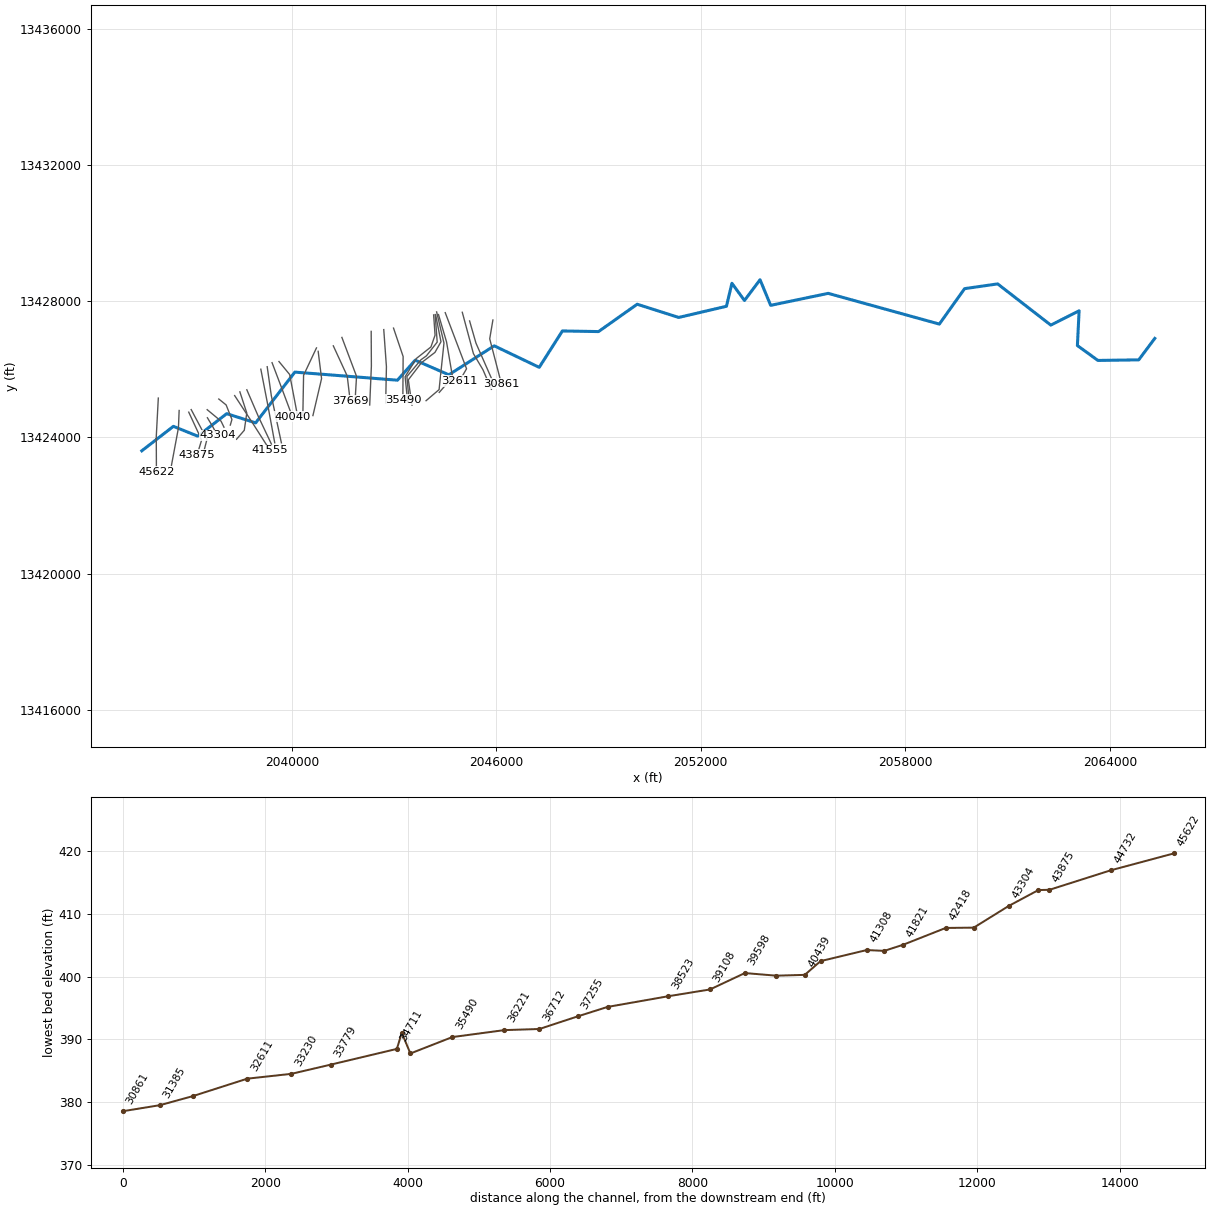
--- Raccoon Creek.prj (project) ---

Proj Title=Raccoon Creek Base Level Engineering
Current Plan=p01
Default Exp/Contr=0.3,0.1
English Units
Geom File=g01
Flow File=f01
Plan File=p01
Y Axis Title=Elevation
X Axis Title(PF)=Main Channel Distance
X Axis Title(XS)=Station
BEGIN DESCRIPTION:
Raccoon Creek
END DESCRIPTION:
DSS Export Rating Curves= 0
DSS Export Rating Curve Sorted= 0
DSS Export Volume Flow Curves= 0
DXF OffsetX= 0
DXF OffsetY= 0
DXF ScaleX= 1
DXF ScaleY= 10

--- Raccoon Creek.p01 (plan) ---

Plan Title=Multiple Run
Short Identifier=Multiple
Geom File=g01
Flow File=f01
Subcritical Flow
K Sum by GR= 0
Std Step Tol= 0.01
Critical Tol= 0.01
Num of Std Step Trials= 20
Max Error Tol= 0.3
Flow Tol Ratio= 0.001
Split Flow NTrial= 30
Split Flow Tol= 0.02
Split Flow Ratio= 0.02
Log Output Level= 0
Friction Slope Method= 1
Unsteady Friction Slope Method= 2
Unsteady Bridges Friction Slope Method= 1
Parabolic Critical Depth
Global Vel Dist=  1 , 1 , 1
Global Log Level= 0
CheckData=True
Encroach Param= -1, 0, 0, 0
BEGIN DESCRIPTION:
Multiple Run
END DESCRIPTION:

--- Raccoon Creek.f01 (steady flow) ---

Flow Title=Multiple
Program Version=5.05
Number of Profiles= 7
Profile Names=10-year,25-year,50-year,1pct_min,100-year,1pct_plu,500-year
River Rch & RM=Raccoon Creek,Reach-1         ,45622
     224     309     378     231     462     921     698
River Rch & RM=Raccoon Creek,Reach-1         ,41555
     346     488     606     375     749    1495    1162
River Rch & RM=Raccoon Creek,Reach-1         ,37669
     362     510     634     392     783    1562    1214
River Rch & RM=Raccoon Creek,Reach-1         ,34901
     384     542     674     417     833    1661    1291
River Rch & RM=Raccoon Creek,Reach-1         ,31845
     496     706     885     551    1099    2194    1725
River Rch & RM=Raccoon Creek,Reach-1         ,27965
     536     766     960     599    1194    2383    1878
River Rch & RM=Raccoon Creek,Reach-1         ,24760
     541     768     959     595    1187    2369    1849
River Rch & RM=Raccoon Creek,Reach-1         ,14529
     560     794     990     614    1225    2444    1904
River Rch & RM=Raccoon Creek,Reach-1         ,9260
     679     969    1215     756    1508    3009    2363
River Rch & RM=Raccoon Creek,Reach-1         ,2207
     963    1393    1763    1106    2207    4403    3515
Boundary for River Rch & Prof#=Raccoon Creek,Reach-1         , 1
Up Type= 0
Dn Type= 3
Dn Slope=0.00364
Boundary for River Rch & Prof#=Raccoon Creek,Reach-1         , 2
Up Type= 0
Dn Type= 3
Dn Slope=0.00364
Boundary for River Rch & Prof#=Raccoon Creek,Reach-1         , 3
Up Type= 0
Dn Type= 3
Dn Slope=0.00364
Boundary for River Rch & Prof#=Raccoon Creek,Reach-1         , 4
Up Type= 0
Dn Type= 3
Dn Slope=0.00364
Boundary for River Rch & Prof#=Raccoon Creek,Reach-1         , 5
Up Type= 0
Dn Type= 3
Dn Slope=0.00364
Boundary for River Rch & Prof#=Raccoon Creek,Reach-1         , 6
Up Type= 0
Dn Type= 3
Dn Slope=0.00364
Boundary for River Rch & Prof#=Raccoon Creek,Reach-1         , 7
Up Type= 0
Dn Type= 3
Dn Slope=0.00364
DSS Import GetInterval= 0
DSS Import GetPeak= 0
DSS Import FillOption= 0

--- Raccoon Creek.g01 (geometry) ---

Geom Title=Existing Conditions

River Reach=Raccoon Creek,Reach-1
Reach XY= 30
      2035600.80     13423604.54      2036527.29     13424322.83
      2037240.80     13424034.54      2038090.80     13424694.54
      2038940.80     13424424.54      2040090.80     13425914.54
      2043101.56     13425677.40      2043622.40     13426264.64
      2044609.38     13425836.25      2045940.13     13426686.51
      2047260.80     13426054.54      2047940.42     13427123.00
      2049000.80     13427104.54      2050134.43     13427907.50
      2051354.04     13427519.05      2052753.78     13427847.82
      2052914.37     13428522.74      2053282.21     13428017.10
      2053740.11     13428626.90      2054050.80     13427874.54
      2055739.89     13428226.51      2059000.80     13427324.54
      2059740.80     13428364.54      2060710.80     13428504.54
      2062270.80     13427294.54      2063100.80     13427714.54
      2063050.80     13426694.54      2063652.90     13426257.13
      2064850.80     13426274.54      2065320.80     13426904.54

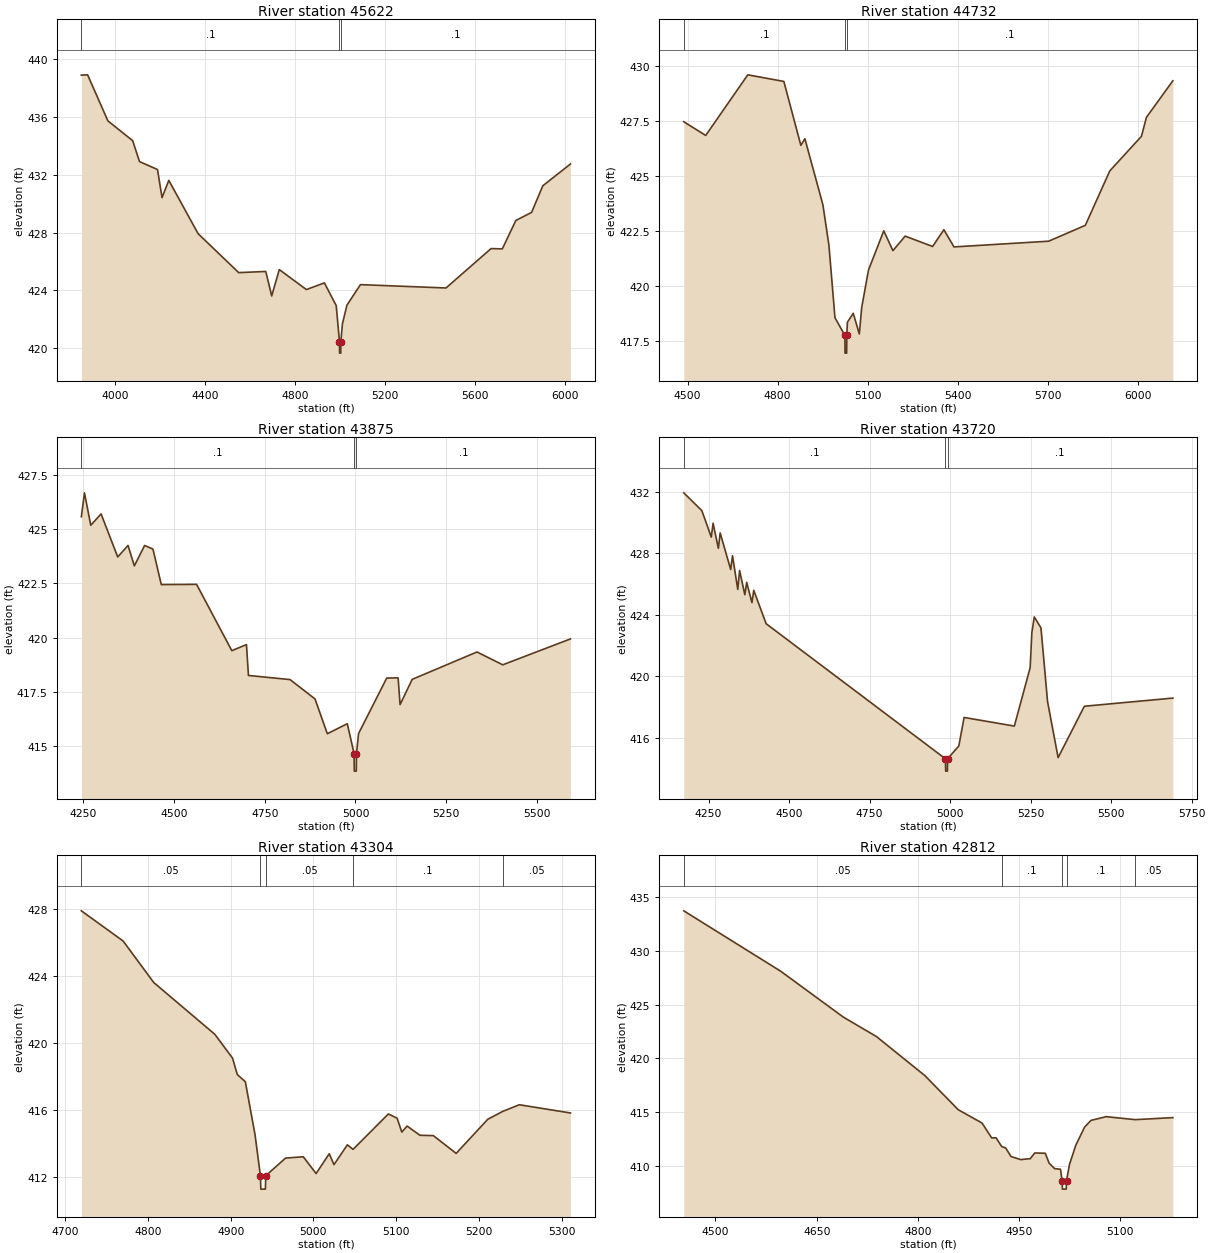
Type RM Length L Ch R = 1,45622,890,890,890
BEGIN DESCRIPTION:
Raccoon Creek 59.0
END DESCRIPTION:
XS GIS Cut Line= 3
      2036084.91     13425152.65      2036025.00     13424025.00
      2036029.36     13422982.55
#Sta/Elev= 30
  3850.3  438.87  3878.0  438.89  3968.1  435.71  4078.3  434.34  4108.3  432.90
  4188.4  432.35  4208.5  430.41  4238.5  431.60  4368.7  427.92  4548.9  425.23
  4669.1  425.31  4695.5  423.62  4729.2  425.44  4849.4  424.06  4929.5  424.52
  4982.0  422.95  4996.4  420.47  4996.9  419.67  5002.1  419.67  5002.6  420.47
  5009.5  421.69  5029.5  422.98  5089.5  424.40  5469.5  424.17  5669.5  426.89
  5719.5  426.87  5779.5  428.83  5849.5  429.39  5899.5  431.23  6022.0  432.73
#Mann=3,-1,0
  3850.3     0.1       0  4996.4    0.07       0  5002.6     0.1       0
Bank Sta=4996.4,5002.6
Exp/Cntr=0.3,0.1

Type RM Length L Ch R = 1,44732,857,857,857
BEGIN DESCRIPTION:
Raccoon Creek 58.0
END DESCRIPTION:
XS GIS Cut Line= 3
      2036696.02     13424788.05      2036675.00     13424275.00
      2036470.61     13423178.46
#Sta/Elev= 30
  4487.6  427.46  4560.7  426.84  4700.8  429.59  4820.9  429.29  4877.5  426.39
  4891.0  426.69  4951.0  423.69  4971.1  421.85  4991.1  418.57  5024.2  417.76
  5024.7  416.96  5030.1  416.96  5030.6  417.76  5032.5  418.36  5051.9  418.77
  5072.3  417.83  5080.2  419.03  5102.8  420.73  5153.7  422.51  5184.2  421.61
  5224.9  422.27  5316.4  421.80  5353.9  422.56  5387.6  421.78  5703.0  422.04
  5825.0  422.76  5906.5  425.23  6011.9  426.80  6028.5  427.66  6116.5  429.32
#Mann=3,-1,0
  4487.6     0.1       0  5024.2    0.07       0  5030.6     0.1       0
Bank Sta=5024.2,5030.6
Exp/Cntr=0.3,0.1

Type RM Length L Ch R = 1,43875,155,155,155
BEGIN DESCRIPTION:
Raccoon Creek 57.0
END DESCRIPTION:
XS GIS Cut Line= 4
      2036977.27     13424739.46      2037310.61     13424020.71
      2037352.05     13423908.41      2037225.74     13423492.14
#Sta/Elev= 30
  4245.0  425.56  4253.5  426.66  4270.9  425.17  4299.3  425.69  4345.1  423.71
  4373.5  424.24  4390.9  423.30  4419.3  424.24  4442.2  424.07  4465.1  422.44
  4562.3  422.45  4659.4  419.40  4699.7  419.68  4705.2  418.26  4819.8  418.07
  4888.5  417.18  4922.4  415.58  4977.4  416.04  4996.2  414.66  4996.7  413.86
  5002.2  413.86  5002.7  414.66  5008.5  415.59  5086.0  418.14  5117.4  418.15
  5122.8  416.92  5156.1  418.08  5334.6  419.34  5405.6  418.75  5592.0  419.94
#Mann=3,-1,0
  4245.0     0.1       0  4996.2    0.07       0  5002.7     0.1       0
Bank Sta=4996.2,5002.7
Exp/Cntr=0.3,0.1

Type RM Length L Ch R = 1,43720,416,416,416
BEGIN DESCRIPTION:
Raccoon Creek 56.0
END DESCRIPTION:
XS GIS Cut Line= 3
      2037049.56     13424814.67      2037512.64     13423943.13
      2037380.69     13423428.30
#Sta/Elev= 30
  4173.2  431.92  4229.4  430.76  4258.6  429.04  4264.2  429.94  4280.6  428.31
  4286.2  429.31  4318.9  426.93  4324.5  427.83  4340.8  425.64  4346.5  426.87
  4362.8  425.29  4368.5  426.10  4384.8  424.78  4390.5  425.58  4428.8  423.41
  4985.7  414.62  4986.2  413.82  4991.7  413.82  4992.2  414.62  5027.2  415.46
  5043.5  417.31  5199.5  416.75  5248.6  420.55  5253.8  422.81  5261.4  423.85
  5282.1  423.14  5302.7  418.33  5335.4  414.70  5416.9  418.04  5691.6  418.57
#Mann=3,-1,0
  4173.2     0.1       0  4985.7    0.07       0  4992.2     0.1       0
Bank Sta=4985.7,4992.2
Exp/Cntr=0.3,0.1

Type RM Length L Ch R = 1,43304,492,492,492
BEGIN DESCRIPTION:
Raccoon Creek 55.0
END DESCRIPTION:
XS GIS Cut Line= 3
      2037525.01     13424574.98      2037675.00     13424325.00
      2037816.93     13424061.18
#Sta/Elev= 30
  4719.6  427.88  4770.1  426.08  4807.0  423.61  4880.9  420.52  4902.3  419.10
  4908.1  418.12  4917.8  417.69  4929.5  414.53  4936.0  412.09  4936.5  411.29
  4942.0  411.29  4942.5  412.09  4966.4  413.14  4987.8  413.22  5003.3  412.22
  5019.2  413.40  5024.9  412.75  5041.1  413.93  5048.0  413.66  5090.6  415.77
  5101.2  415.52  5106.9  414.69  5113.3  415.05  5128.8  414.50  5145.0  414.48
  5172.6  413.42  5210.7  415.45  5228.7  415.92  5248.9  416.32  5310.7  415.83
#Mann=5,-1,0
  4719.6    0.05       0  4936.0    0.03       0  4942.5    0.05       0
  5048.0     0.1       0  5228.7    0.05       0
Bank Sta=4936,4942.5
Exp/Cntr=0.3,0.1

Type RM Length L Ch R = 1,42812,394,394,394
BEGIN DESCRIPTION:
Raccoon Creek 54.0
END DESCRIPTION:
XS GIS Cut Line= 3
      2037518.96     13424811.50      2037925.00     13424475.00
      2038011.36     13424297.33
#Sta/Elev= 30
  4453.0  433.74  4596.8  428.11  4689.3  423.85  4738.8  422.02  4810.4  418.39
  4859.9  415.21  4895.0  413.98  4909.4  412.59  4915.9  412.60  4924.2  411.79
  4930.2  411.65  4938.0  410.86  4952.4  410.57  4966.7  410.66  4973.2  411.19
  4988.9  411.16  4994.4  410.25  5002.6  409.73  5011.4  409.67  5013.7  408.62
  5014.2  407.82  5019.8  407.82  5020.3  408.62  5024.8  410.14  5034.0  411.90
  5047.1  413.60  5056.5  414.22  5079.1  414.57  5122.1  414.29  5177.9  414.48
#Mann=5,-1,0
  4453.0    0.05       0  4924.2     0.1       0  5013.7    0.07       0
  5020.3     0.1       0  5122.1    0.05       0
Bank Sta=5013.7,5020.3
Exp/Cntr=0.3,0.1

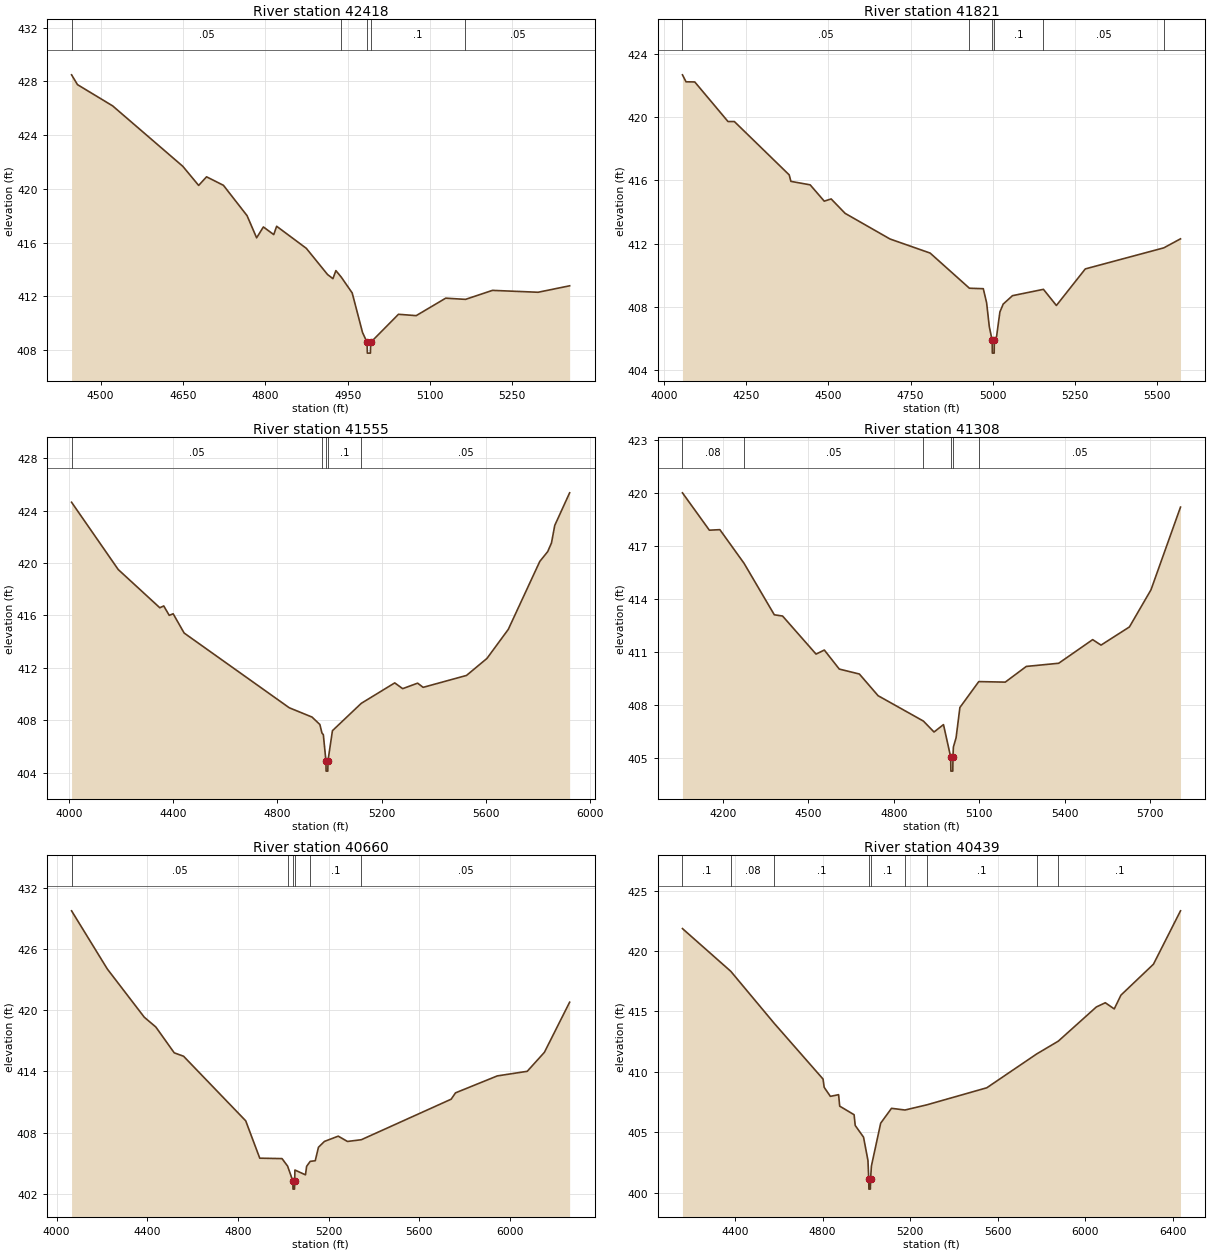
Type RM Length L Ch R = 1,42418,597,597,597
BEGIN DESCRIPTION:
Mapping XS f6022f1c
END DESCRIPTION:
XS GIS Cut Line= 4
      2037859.23     13425124.87      2038074.50     13424951.27
      2038244.64     13424524.18      2038197.16     13424359.88
#Sta/Elev= 30
  4447.1  428.48  4457.9  427.75  4521.9  426.17  4649.8  421.67  4678.6  420.25
  4693.0  420.89  4723.7  420.26  4766.8  418.00  4784.2  416.35  4796.5  417.16
  4815.4  416.59  4820.7  417.21  4874.7  415.57  4913.4  413.62  4923.2  413.31
  4928.6  413.91  4938.5  413.42  4958.3  412.25  4977.1  409.31  4985.4  408.57
  4985.9  407.77  4991.5  407.77  4992.0  408.57  5042.6  410.66  5074.9  410.56
  5128.7  411.86  5164.7  411.77  5213.8  412.44  5297.0  412.30  5354.4  412.78
#Mann=5,-1,0
  4447.1    0.05       0  4938.5     0.1       0  4985.4    0.07       0
  4992.0     0.1       0  5164.7    0.05       0
Bank Sta=4985.4,4992
Exp/Cntr=0.3,0.1

Type RM Length L Ch R = 1,41821,266,266,266
BEGIN DESCRIPTION:
Raccoon Creek 53.0
END DESCRIPTION:
XS GIS Cut Line= 4
      2038478.13     13425334.97      2038680.40     13424715.15
      2038607.48     13424207.34      2038379.18     13423942.72
#Sta/Elev= 30
  4056.3  422.67  4067.2  422.23  4093.8  422.22  4194.8  419.72  4214.1  419.72
  4380.9  416.35  4386.1  415.94  4444.7  415.72  4487.5  414.69  4508.5  414.83
  4550.9  413.92  4687.4  412.30  4809.5  411.41  4928.9  409.19  4971.1  409.16
  4981.2  408.27  4989.4  406.76  4998.1  405.89  4998.6  405.09  5004.2  405.09
  5004.7  405.89  5011.5  406.14  5021.6  407.69  5031.7  408.19  5059.9  408.72
  5154.0  409.12  5193.4  408.10  5281.3  410.41  5520.0  411.74  5570.8  412.31
#Mann=6,-1,0
  4056.3    0.05       0  4928.9     0.1       0  4998.1    0.07       0
  5004.7     0.1       0  5154.0    0.05       0  5520.0     0.1       0
Bank Sta=4998.1,5004.7
Exp/Cntr=0.3,0.1

Type RM Length L Ch R = 1,41555,247,247,247
BEGIN DESCRIPTION:
Raccoon Creek 52.0
END DESCRIPTION:
XS GIS Cut Line= 3
      2038325.02     13425224.97      2038851.41     13424419.15
      2039363.56     13423616.19
#Sta/Elev= 30
  4008.3  424.65  4187.7  419.51  4347.6  416.59  4362.7  416.73  4383.8  416.01
  4398.9  416.13  4441.1  414.66  4845.3  408.95  4932.8  408.24  4963.0  407.67
  4970.9  407.02  4976.2  406.90  4986.2  404.91  4986.9  404.11  4993.5  404.11
  4994.2  404.91  5011.3  407.20  5122.2  409.29  5250.8  410.85  5281.3  410.41
  5338.8  410.83  5360.0  410.51  5526.7  411.42  5605.4  412.72  5687.4  414.94
  5808.5  420.13  5838.9  420.88  5853.4  421.54  5866.0  422.88  5923.2  425.37
#Mann=5,-1,0
  4008.3    0.05       0  4970.9     0.1       0  4986.2    0.07       0
  4994.2     0.1       0  5122.2    0.05       0
Bank Sta=4986.2,4994.2
Exp/Cntr=0.3,0.1

Type RM Length L Ch R = 1,41308,648,648,648
BEGIN DESCRIPTION:
Raccoon Creek 51.0
END DESCRIPTION:
XS GIS Cut Line= 3
      2038682.14     13425395.69      2039020.68     13424610.12
      2039402.62     13423802.82
#Sta/Elev= 30
  4057.7  420.03  4152.2  417.91  4189.1  417.94  4274.0  416.03  4380.2  413.11
  4409.2  413.04  4526.7  410.88  4555.8  411.11  4608.3  410.03  4678.8  409.75
  4744.5  408.52  4903.6  407.08  4940.9  406.46  4974.1  406.88  4999.4  405.04
  5000.1  404.24  5006.8  404.24  5007.4  405.04  5008.9  405.61  5018.3  406.13
  5031.7  407.85  5098.0  409.32  5191.0  409.29  5264.8  410.18  5378.5  410.36
  5497.8  411.70  5527.2  411.39  5626.8  412.42  5702.6  414.53  5806.2  419.22
#Mann=6,-1,0
  4057.7    0.08       0  4274.0    0.05       0  4903.6     0.1       0
  4999.4    0.07       0  5007.4     0.1       0  5098.0    0.05       0
Bank Sta=4999.4,5007.4
Exp/Cntr=0.3,0.1

Type RM Length L Ch R = 1,40660,221,221,221
BEGIN DESCRIPTION:
Raccoon Creek 50.0
END DESCRIPTION:
XS GIS Cut Line= 3
      2039092.73     13425999.86      2039296.72     13424949.53
      2039500.22     13423841.11
#Sta/Elev= 30
  4066.0  429.73  4223.8  424.03  4386.7  419.31  4437.7  418.35  4518.9  415.82
  4559.9  415.49  4834.2  409.16  4896.1  405.50  4994.3  405.46  5018.8  404.73
  5042.0  403.27  5042.7  402.47  5049.4  402.47  5050.1  403.27  5051.1  404.34
  5097.7  403.87  5102.8  404.70  5118.7  405.19  5140.8  405.25  5155.0  406.57
  5181.2  407.14  5242.2  407.66  5282.9  407.14  5344.2  407.31  5740.4  411.28
  5759.5  411.90  5943.8  413.56  6075.9  414.01  6151.6  415.87  6262.9  420.78
#Mann=6,-1,0
  4066.0    0.05       0  5018.8    0.12       0  5042.0    0.04       0
  5050.1    0.12       0  5118.7     0.1       0  5344.2    0.05       0
Bank Sta=5042,5050.1
Exp/Cntr=0.3,0.1

Type RM Length L Ch R = 1,40439,399,399,399
BEGIN DESCRIPTION:
Raccoon Creek 49.0
END DESCRIPTION:
XS GIS Cut Line= 3
      2039279.36     13426073.65      2039400.89     13425218.63
      2039695.85     13423839.23
#Sta/Elev= 30
  4159.8  421.85  4380.7  418.31  4579.1  414.00  4801.9  409.39  4806.9  408.71
  4835.2  407.96  4872.8  408.10  4877.8  407.15  4943.6  406.44  4948.7  405.55
  4986.7  404.58  5006.9  402.65  5010.5  401.08  5011.1  400.28  5017.9  400.28
  5018.6  401.08  5022.7  402.20  5065.0  405.74  5114.4  406.97  5175.9  406.83
  5276.1  407.26  5549.5  408.67  5777.2  411.47  5875.9  412.53  6049.7  415.36
  6090.6  415.71  6131.5  415.20  6162.0  416.34  6310.4  418.90  6434.0  423.32
#Mann=9,-1,0
  4159.8     0.1       0  4380.7    0.08       0  4579.1     0.1       0
  5010.5    0.07       0  5018.6     0.1       0  5175.9    0.08       0
  5276.1     0.1       0  5777.2    0.08       0  5875.9     0.1       0
Bank Sta=5010.5,5018.6
Exp/Cntr=0.3,0.1

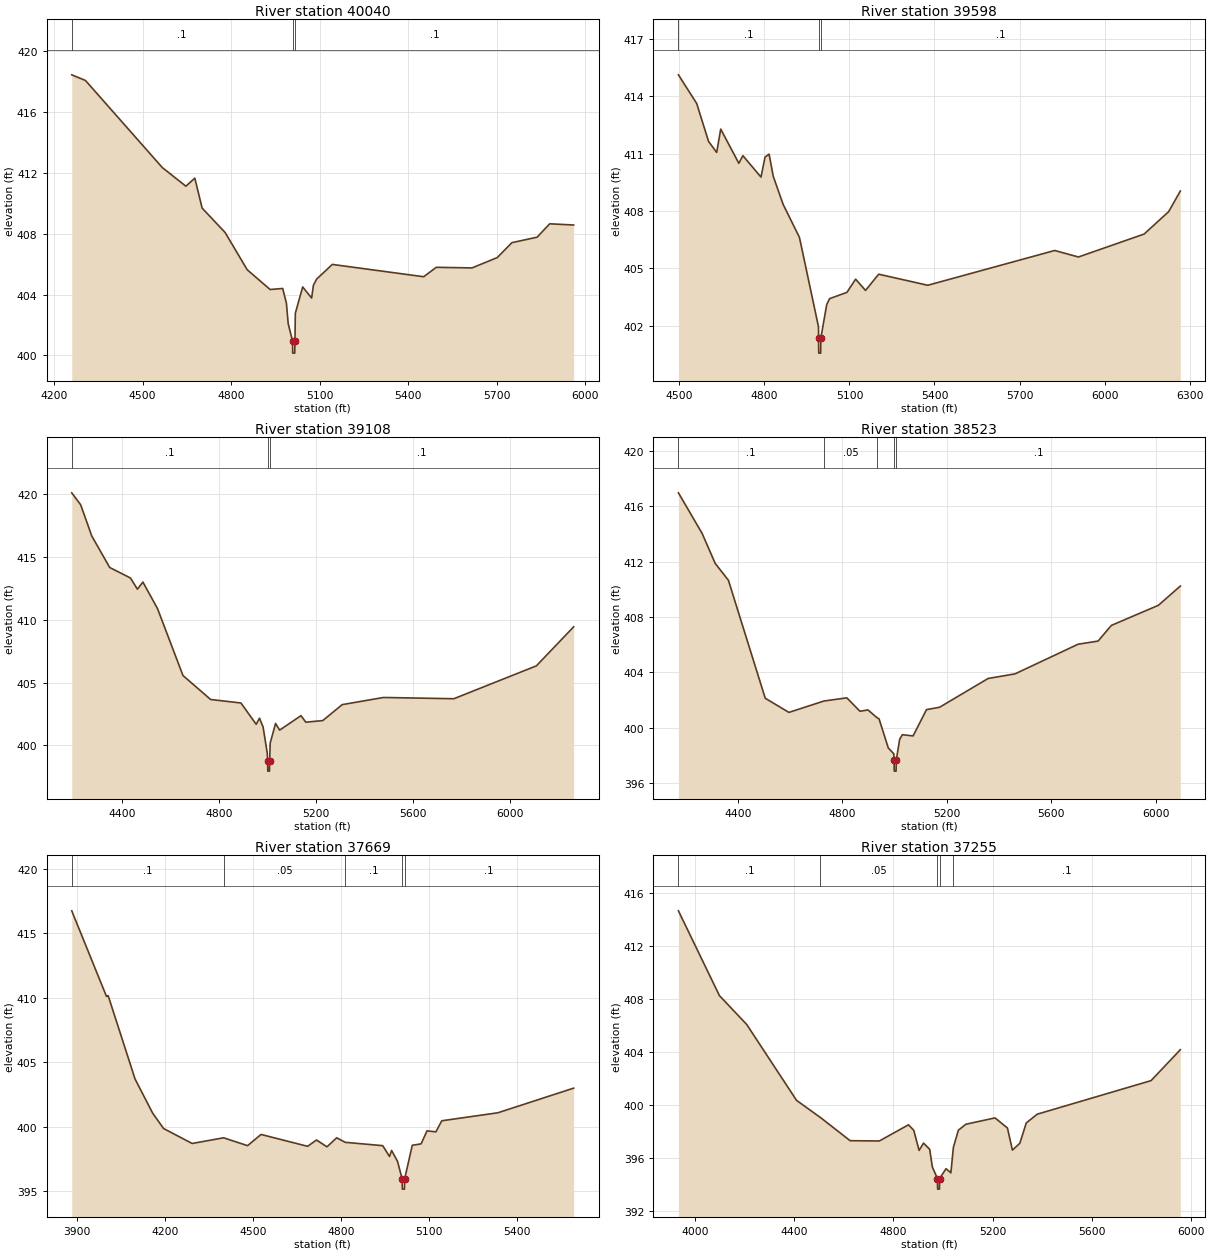
Type RM Length L Ch R = 1,40040,442,442,442
BEGIN DESCRIPTION:
Raccoon Creek 48.0
END DESCRIPTION:
XS GIS Cut Line= 3
      2039422.57     13426190.88      2039675.00     13425525.00
      2040021.16     13424599.01
#Sta/Elev= 30
  4259.7  418.44  4306.1  418.07  4566.8  412.34  4646.5  411.12  4676.7  411.65
  4701.5  409.68  4779.3  408.08  4854.2  405.63  4931.9  404.33  4974.5  404.40
  4987.0  403.44  4993.2  402.08  5007.8  400.95  5008.5  400.15  5015.3  400.15
  5016.0  400.95  5017.3  402.77  5042.2  404.50  5072.5  403.77  5078.6  404.61
  5089.3  405.01  5142.6  405.98  5452.2  405.17  5494.9  405.79  5616.1  405.75
  5701.6  406.43  5751.2  407.41  5836.6  407.77  5879.3  408.65  5960.4  408.57
#Mann=3,-1,0
  4259.7     0.1       0  5007.8    0.07       0  5016.0     0.1       0
Bank Sta=5007.8,5016
Exp/Cntr=0.3,0.1

Type RM Length L Ch R = 1,39598,490,490,490
BEGIN DESCRIPTION:
Raccoon Creek 47.0
END DESCRIPTION:
XS GIS Cut Line= 3
      2039625.00     13426225.00      2039939.08     13425843.63
      2040177.72     13424589.69
#Sta/Elev= 30
  4496.7  415.13  4561.2  413.63  4602.9  411.65  4631.6  411.07  4645.9  412.29
  4709.8  410.50  4724.1  410.90  4787.9  409.78  4802.3  410.83  4816.6  410.98
  4831.0  409.83  4866.1  408.35  4923.5  406.63  4990.8  401.95  4991.0  401.37
  4991.7  400.57  4998.5  400.57  4999.2  401.37  5019.9  403.12  5030.1  403.42
  5091.2  403.75  5121.7  404.44  5156.7  403.85  5203.1  404.70  5376.2  404.12
  5824.1  405.94  5907.8  405.60  6139.6  406.80  6226.0  407.97  6267.2  409.05
#Mann=3,-1,0
  4496.7     0.1       0  4991.0    0.07       0  4999.2     0.1       0
Bank Sta=4991,4999.2
Exp/Cntr=0.3,0.1

Type RM Length L Ch R = 1,39108,585,585,585
BEGIN DESCRIPTION:
Raccoon Creek 46.0
END DESCRIPTION:
XS GIS Cut Line= 3
      2040725.00     13426624.99      2040347.07     13425821.93
      2040325.36     13424641.38
#Sta/Elev= 30
  4192.7  420.13  4229.6  419.17  4275.2  416.69  4349.1  414.18  4434.8  413.34
  4463.1  412.45  4485.9  413.02  4546.4  410.89  4651.0  405.57  4765.0  403.66
  4890.0  403.38  4952.8  401.68  4966.3  402.17  4981.2  401.47  4998.4  399.38
  4999.8  398.75  5000.5  397.95  5007.4  397.95  5008.2  398.75  5010.5  400.19
  5032.6  401.75  5049.5  401.22  5137.2  402.37  5157.2  401.85  5227.2  401.98
  5307.2  403.25  5477.2  403.82  5767.3  403.72  6107.4  406.34  6261.0  409.45
#Mann=3,-1,0
  4192.7     0.1       0  4999.8    0.07       0  5008.2     0.1       0
Bank Sta=4999.8,5008.2
Exp/Cntr=0.3,0.1

Type RM Length L Ch R = 1,38523,854,854,854
BEGIN DESCRIPTION:
Raccoon Creek 45.0
END DESCRIPTION:
XS GIS Cut Line= 3
      2040775.01     13426524.96      2040875.00     13425725.00
      2040620.85     13424638.51
#Sta/Elev= 30
  4172.8  416.96  4263.5  414.03  4313.8  411.86  4364.2  410.65  4505.3  402.13
  4596.0  401.11  4729.8  401.93  4817.7  402.16  4868.1  401.19  4898.4  401.29
  4932.5  400.74  4941.2  400.64  4976.5  398.54  4997.7  398.12  4998.5  397.67
  4999.3  396.87  5006.3  396.87  5007.0  397.67  5020.1  399.17  5030.3  399.50
  5071.4  399.41  5122.8  401.31  5172.8  401.48  5359.0  403.56  5461.7  403.89
  5703.2  406.03  5780.0  406.26  5830.7  407.39  6010.9  408.84  6094.8  410.23
#Mann=5,-1,0
  4172.8     0.1       0  4729.8    0.05       0  4932.5     0.1       0
  4998.5    0.07       0  5007.0     0.1       0
Bank Sta=4998.5,5007
Exp/Cntr=0.3,0.1

Type RM Length L Ch R = 1,37669,414,414,414
BEGIN DESCRIPTION:
Raccoon Creek 44.0
END DESCRIPTION:
XS GIS Cut Line= 3
      2041219.46     13426685.65      2041627.45     13425800.22
      2041714.06     13425068.33
#Sta/Elev= 30
  3881.9  416.74  4000.4  410.10  4006.0  410.17  4097.8  403.70  4157.9  401.05
  4195.1  399.86  4292.5  398.70  4399.8  399.14  4481.6  398.53  4527.5  399.40
  4686.4  398.48  4716.7  398.97  4752.4  398.44  4785.5  399.14  4814.7  398.79
  4942.6  398.53  4965.7  397.69  4972.8  398.16  4993.0  397.32  5008.7  395.96
  5009.5  395.16  5016.7  395.16  5017.5  395.96  5043.3  398.56  5073.5  398.67
  5093.7  399.68  5123.9  399.60  5144.0  400.46  5335.3  401.08  5593.8  402.99
#Mann=5,-1,0
  3881.9     0.1       0  4399.8    0.05       0  4814.7     0.1       0
  5008.7    0.07       0  5017.5     0.1       0
Bank Sta=5008.7,5017.5
Exp/Cntr=0.3,0.1

Type RM Length L Ch R = 1,37255,543,543,543
BEGIN DESCRIPTION:
Raccoon Creek 43.0
END DESCRIPTION:
XS GIS Cut Line= 3
      2041471.20     13426933.04      2041900.89     13425791.54
      2041853.18     13424989.25
#Sta/Elev= 30
  3933.1  414.65  4098.3  408.26  4208.5  406.08  4409.4  400.36  4505.5  399.07
  4625.5  397.32  4743.1  397.30  4860.6  398.52  4882.0  398.10  4903.3  396.59
  4921.3  397.14  4946.1  396.67  4956.8  395.34  4977.3  394.47  4978.1  393.67
  4985.3  393.67  4986.1  394.47  5011.9  395.21  5031.5  394.90  5041.6  396.82
  5061.7  398.11  5091.9  398.56  5209.4  399.04  5259.5  398.28  5279.6  396.61
  5309.6  397.13  5335.4  398.66  5379.7  399.32  5838.6  401.85  5956.5  404.18
#Mann=5,-1,0
  3933.1     0.1       0  4505.5    0.05       0  4977.3    0.03       0
  4986.1    0.05       0  5041.6     0.1       0
Bank Sta=4977.3,4986.1
Exp/Cntr=0.3,0.1

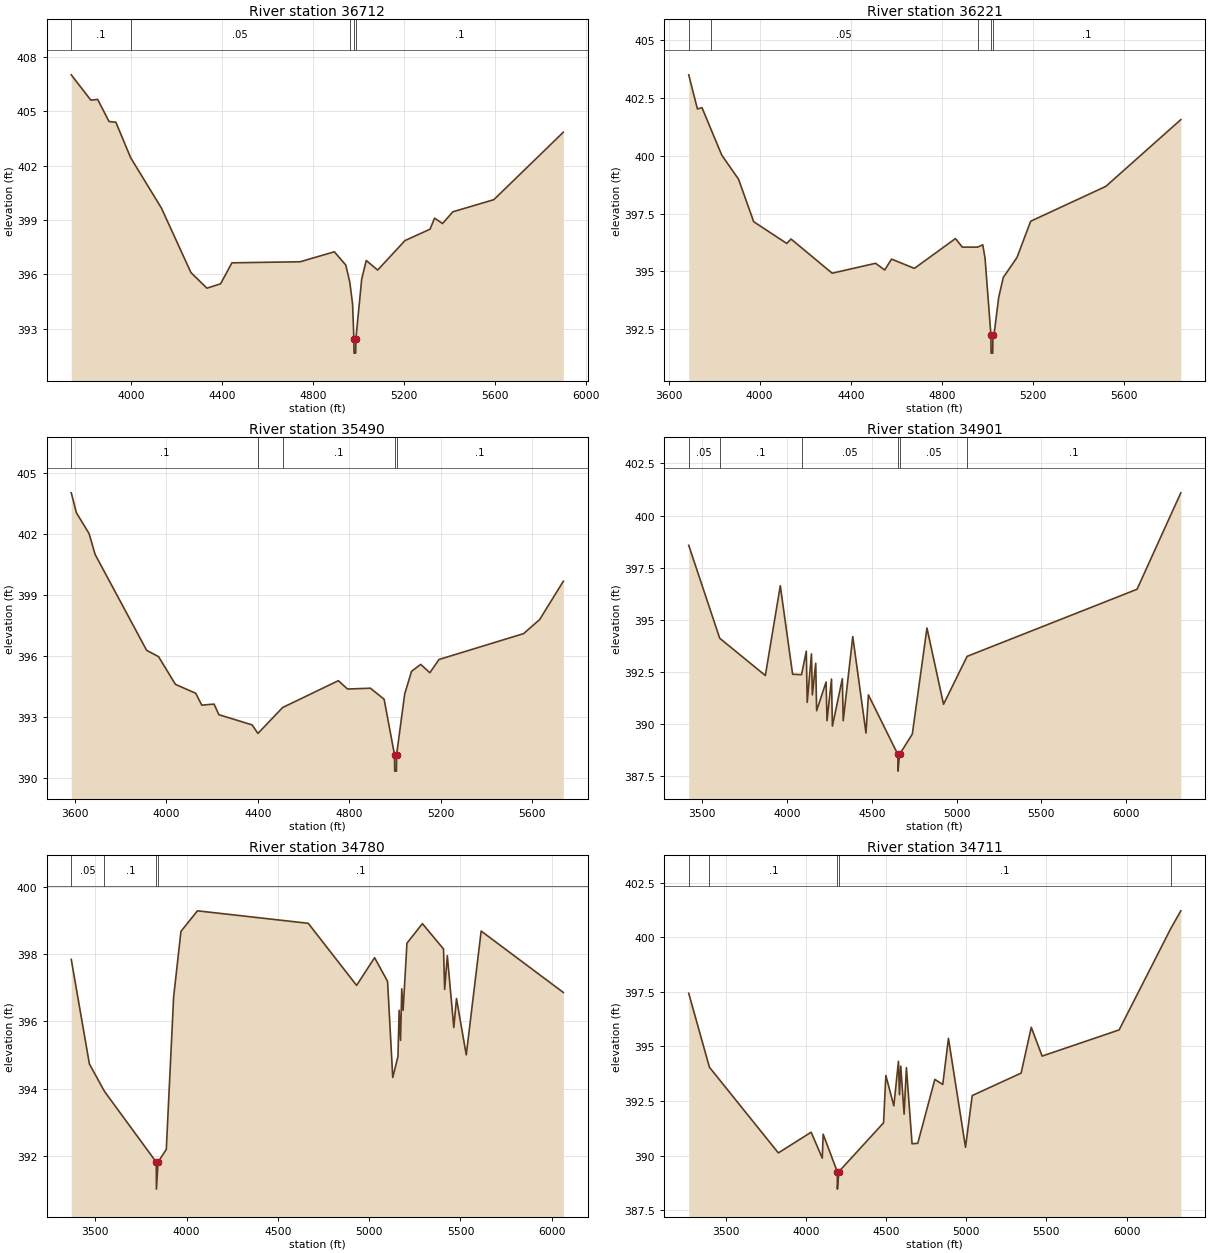
Type RM Length L Ch R = 1,36712,491,491,491
BEGIN DESCRIPTION:
Raccoon Creek 42.0
END DESCRIPTION:
XS GIS Cut Line= 3
      2042330.57     13427110.98      2042336.30     13426091.89
      2042287.18     13424949.75
#Sta/Elev= 30
  3738.4  407.02  3824.4  405.62  3854.4  405.66  3904.4  404.44  3934.4  404.40
  3999.4  402.44  4134.4  399.66  4264.4  396.09  4334.4  395.23  4394.4  395.47
  4444.4  396.63  4744.4  396.69  4894.5  397.24  4944.6  396.51  4962.1  395.58
  4974.6  394.35  4980.2  392.44  4981.0  391.64  4988.2  391.64  4989.1  392.44
  5014.6  395.73  5034.7  396.76  5084.7  396.23  5204.8  397.86  5314.9  398.49
  5334.9  399.10  5369.8  398.80  5415.0  399.45  5595.2  400.12  5900.7  403.85
#Mann=5,-1,0
  3738.4     0.1       0  3999.4    0.05       0  4962.1     0.1       0
  4980.2    0.07       0  4989.1     0.1       0
Bank Sta=4980.2,4989.1
Exp/Cntr=0.3,0.1

Type RM Length L Ch R = 1,36221,731,731,731
BEGIN DESCRIPTION:
Raccoon Creek 41.0
END DESCRIPTION:
XS GIS Cut Line= 3
      2042699.50     13427163.09      2042777.62     13426073.66
      2042755.92     13425005.91
#Sta/Elev= 30
  3688.6  403.51  3726.8  402.03  3746.8  402.09  3785.1  401.18  3833.8  400.03
  3907.3  398.99  3973.8  397.15  4118.9  396.21  4137.8  396.40  4318.3  394.92
  4508.8  395.35  4548.9  395.06  4579.0  395.53  4679.3  395.13  4859.5  396.42
  4889.5  396.05  4956.4  396.05  4979.5  396.15  4989.5  395.56  5015.1  392.26
  5015.9  391.46  5023.2  391.46  5024.0  392.26  5029.5  392.32  5049.5  393.88
  5069.6  394.74  5129.6  395.60  5189.6  397.17  5519.6  398.68  5848.8  401.57
#Mann=5,-1,0
  3688.6     0.1       0  3785.1    0.05       0  4956.4     0.1       0
  5015.1    0.07       0  5024.0     0.1       0
Bank Sta=5015.1,5024
Exp/Cntr=0.3,0.1

Type RM Length L Ch R = 1,35490,589,589,589
BEGIN DESCRIPTION:
Raccoon Creek 40.0
END DESCRIPTION:
XS GIS Cut Line= 3
      2042985.96     13427206.45      2043267.92     13426372.32
      2043259.39     13425101.45
#Sta/Elev= 30
  3584.4  404.01  3607.0  403.03  3662.3  402.01  3688.5  400.99  3913.9  396.28
  3965.9  395.97  4039.8  394.61  4128.7  394.17  4154.9  393.59  4208.7  393.64
  4229.8  393.12  4375.0  392.62  4400.5  392.20  4508.2  393.47  4752.2  394.79
  4792.2  394.38  4892.2  394.42  4952.2  393.88  4997.7  391.15  4998.5  390.35
  5005.9  390.35  5006.7  391.15  5042.2  394.14  5072.2  395.25  5112.2  395.59
  5152.2  395.18  5192.2  395.83  5562.2  397.10  5632.2  397.79  5735.8  399.67
#Mann=5,-1,0
  3584.4     0.1       0  4400.5    0.05       0  4508.2     0.1       0
  4997.7    0.07       0  5006.7     0.1       0
Bank Sta=4997.7,5006.7
Exp/Cntr=0.3,0.1

Type RM Length L Ch R = 1,34901,121,121,121
BEGIN DESCRIPTION:
Mapping XS d679082f
END DESCRIPTION:
XS GIS Cut Line= 6
      2044163.04     13427593.59      2044204.71     13426999.88
      2044083.18     13426652.65      2043652.62     13426312.38
      2043326.23     13425777.65      2043402.47     13425028.88
#Sta/Elev= 30
  3420.6  398.57  3603.3  394.11  3872.4  392.32  3960.5  396.63  4033.2  392.38
  4085.7  392.36  4113.9  393.49  4119.2  391.03  4144.3  393.36  4149.6  391.39
  4169.4  392.91  4174.8  390.63  4230.6  392.01  4235.9  390.15  4262.5  392.15
  4267.8  389.89  4326.4  392.17  4331.6  390.15  4387.9  394.19  4465.9  389.56
  4480.1  391.39  4653.9  388.53  4654.9  387.73  4663.5  388.53  4739.1  389.51
  4825.4  394.60  4923.1  390.94  5062.2  393.24  6064.2  396.46  6322.3  401.09
#Mann=6,-1,0
  3420.6    0.05       0  3603.3     0.1       0  4085.7    0.05       0
  4653.9   0.033       0  4663.5    0.05       0  5062.2     0.1       0
Bank Sta=4653.9,4663.5
Exp/Cntr=0.3,0.1

Type RM Length L Ch R = 1,34780,69,69,69
BEGIN DESCRIPTION:
Mapping XS 1792ea47
END DESCRIPTION:
XS GIS Cut Line= 6
      2044208.18     13427604.03      2044267.21     13426795.02
      2043951.23     13426392.24      2043791.51     13426277.65
      2043378.32     13425784.60      2043426.62     13425258.42
#Sta/Elev= 30
  3368.8  397.84  3468.1  394.74  3550.4  393.93  3834.3  391.83  3835.2  391.03
  3843.9  391.83  3889.2  392.21  3929.3  396.72  3969.4  398.67  4059.7  399.28
  4666.5  398.91  4931.3  397.07  5029.9  397.89  5100.9  397.19  5129.3  394.34
  5157.7  394.96  5164.4  396.33  5171.9  395.44  5178.6  396.97  5186.0  396.33
  5207.0  398.32  5291.6  398.90  5407.3  398.15  5413.5  396.95  5428.1  397.95
  5463.7  395.82  5478.3  396.68  5531.8  395.01  5613.5  398.68  6063.5  396.86
#Mann=4,-1,0
  3368.8    0.05       0  3550.4     0.1       0  3834.3    0.07       0
  3843.9     0.1       0
Bank Sta=3834.3,3843.9
Exp/Cntr=0.3,0.1

Type RM Length L Ch R = 1,34711,932,932,932
BEGIN DESCRIPTION:
Mapping XS bcb44cd4
END DESCRIPTION:
XS GIS Cut Line= 6
      2044222.06     13427593.67      2044378.32     13426805.43
      2044201.23     13426492.93      2043805.40     13426190.85
      2043419.98     13425687.38      2043527.62     13424944.33
#Sta/Elev= 30
  3269.6  397.44  3398.6  394.05  3828.4  390.12  4033.0  391.07  4102.5  389.88
  4107.8  390.98  4195.9  389.26  4196.8  388.46  4205.5  389.26  4484.5  391.50
  4498.9  393.67  4548.6  392.28  4577.4  394.32  4583.8  392.79  4591.8  394.10
  4612.6  391.90  4627.0  394.03  4662.3  390.54  4697.8  390.56  4804.3  393.49
  4853.8  393.26  4889.2  395.37  4995.6  390.38  5037.4  392.75  5342.4  393.78
  5405.6  395.88  5473.4  394.56  5953.6  395.76  6276.5  400.42  6338.2  401.22
#Mann=5,-1,0
  3269.6    0.05       0  3398.6     0.1       0  4195.9    0.07       0
  4205.5     0.1       0  6276.5    0.05       0
Bank Sta=4195.9,4205.5
Exp/Cntr=0.3,0.1

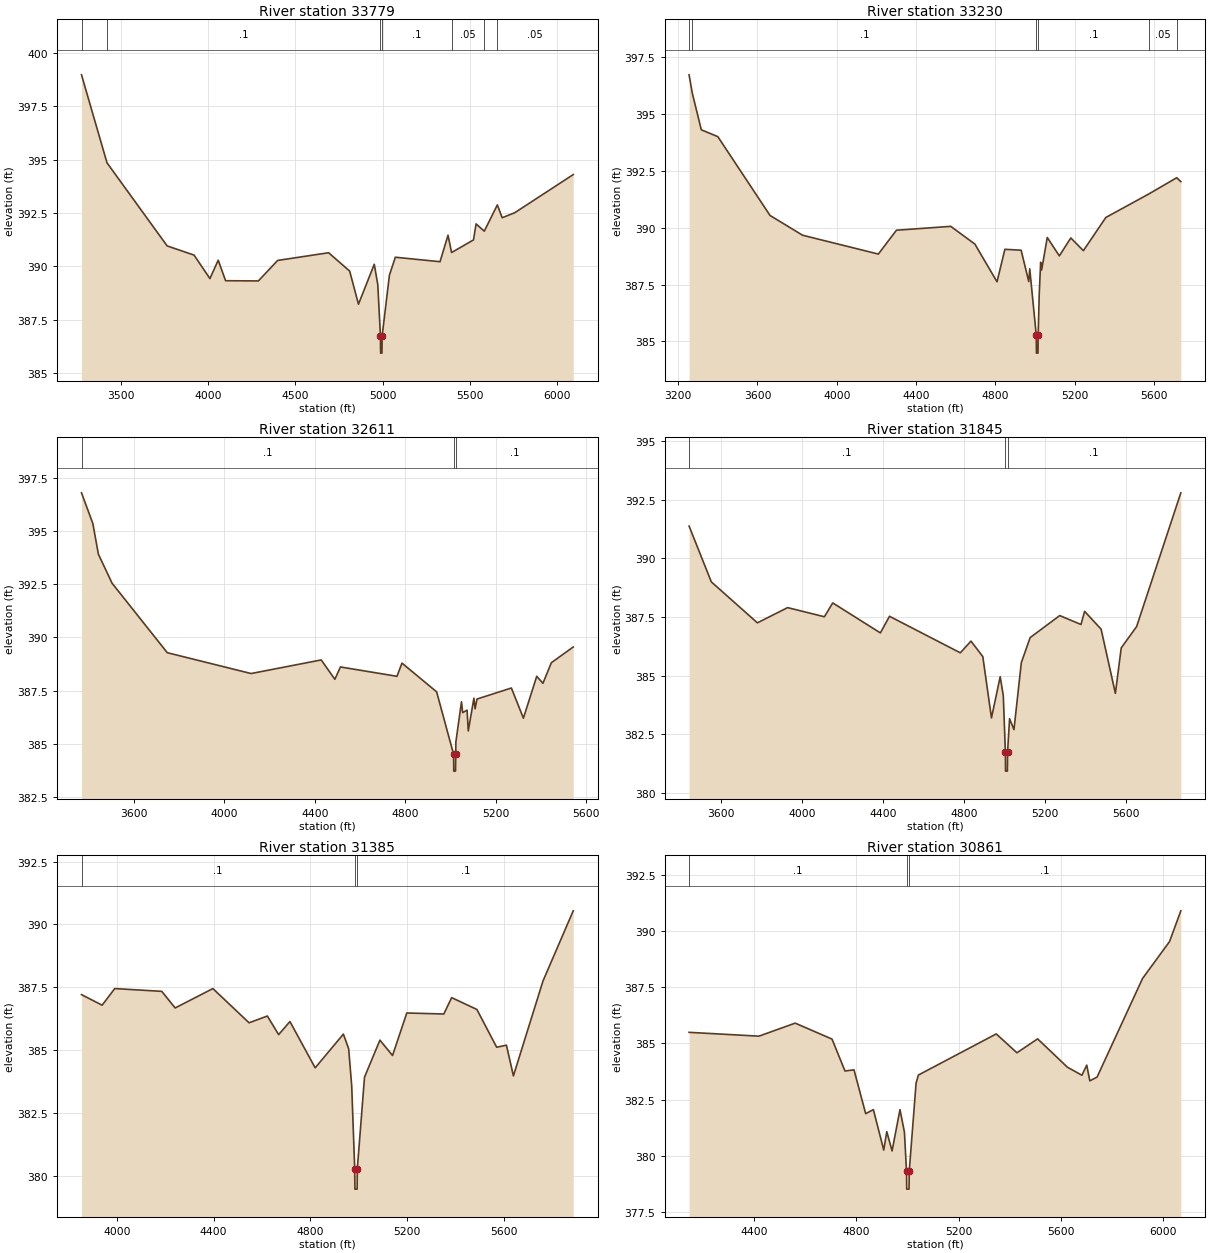
Type RM Length L Ch R = 1,33779,549,549,549
BEGIN DESCRIPTION:
Mapping XS 2a2a9d09
END DESCRIPTION:
XS GIS Cut Line= 4
      2044250.52     13427682.29      2044465.99     13426768.11
      2044322.76     13425400.92      2043940.85     13425075.43
#Sta/Elev= 30
  3275.5  398.97  3421.5  394.85  3765.9  390.96  3920.0  390.53  4010.8  389.43
  4058.3  390.29  4100.6  389.33  4288.2  389.32  4398.8  390.28  4690.4  390.64
  4811.1  389.78  4861.4  388.23  4951.9  390.10  4972.0  389.15  4987.3  386.74
  4988.2  385.94  4995.9  385.94  4996.9  386.74  5038.7  389.59  5072.5  390.43
  5328.4  390.22  5374.2  391.46  5394.7  390.65  5519.9  391.24  5535.0  391.99
  5581.8  391.65  5656.7  392.88  5684.2  392.28  5755.6  392.51  6091.2  394.30
#Mann=7,-1,0
  3275.5    0.05       0  3421.5     0.1       0  4987.3    0.07       0
  4996.9     0.1       0  5394.7    0.05       0  5581.8     0.1       0
  5656.7    0.05       0
Bank Sta=4987.3,4996.9
Exp/Cntr=0.3,0.1

Type RM Length L Ch R = 1,33230,619,619,619
BEGIN DESCRIPTION:
Mapping XS 934fe5a1
END DESCRIPTION:
XS GIS Cut Line= 4
      2044305.40     13427604.05      2044541.51     13426801.96
      2044718.59     13425767.24      2044327.61     13425318.84
#Sta/Elev= 30
  3255.2  396.73  3271.2  395.93  3316.8  394.31  3400.1  394.01  3663.5  390.54
  3827.5  389.67  4210.0  388.84  4301.3  389.89  4575.2  390.06  4697.0  389.28
  4808.6  387.62  4848.5  389.05  4930.3  389.01  4968.7  387.63  4973.8  388.19
  5006.6  385.28  5007.6  384.48  5015.4  384.48  5016.3  385.28  5021.6  387.06
  5028.8  388.48  5033.8  388.14  5062.2  389.57  5123.1  388.76  5180.9  389.55
  5244.5  388.99  5357.5  390.45  5575.4  391.49  5715.2  392.20  5736.0  392.03
#Mann=6,-1,0
  3255.2    0.05       0  3271.2     0.1       0  5006.6    0.07       0
  5016.3     0.1       0  5575.4    0.05       0  5715.2     0.1       0
Bank Sta=5006.6,5016.3
Exp/Cntr=0.3,0.1

Type RM Length L Ch R = 1,32611,766,766,766
BEGIN DESCRIPTION:
Raccoon Creek 36.0
END DESCRIPTION:
XS GIS Cut Line= 3
      2044503.31     13427659.61      2045128.32     13426013.77
      2044922.44     13425655.18
#Sta/Elev= 30
  3368.3  396.80  3418.3  395.36  3443.1  393.91  3503.4  392.55  3747.6  389.28
  4118.1  388.30  4428.1  388.94  4488.4  388.03  4513.1  388.61  4762.9  388.17
  4785.2  388.79  4938.3  387.44  5013.2  384.51  5014.1  383.71  5021.9  383.71
  5022.9  384.51  5023.4  385.08  5048.2  386.97  5053.5  386.46  5072.9  386.58
  5078.3  385.60  5103.1  387.14  5108.4  386.64  5116.8  387.10  5268.8  387.62
  5322.0  386.20  5380.9  388.17  5408.3  387.84  5445.6  388.81  5542.3  389.55
#Mann=3,-1,0
  3368.3     0.1       0  5013.2    0.07       0  5022.9     0.1       0
Bank Sta=5013.2,5022.9
Exp/Cntr=0.3,0.1

Type RM Length L Ch R = 1,31845,460,460,460
BEGIN DESCRIPTION:
Mapping XS 76b7d6a2
END DESCRIPTION:
XS GIS Cut Line= 4
      2045003.51     13427671.03      2045330.38     13426456.58
      2045610.23     13425983.00      2045856.77     13425410.05
#Sta/Elev= 30
  3440.3  391.38  3550.1  389.00  3778.1  387.25  3927.5  387.90  4109.3  387.51
  4150.7  388.10  4386.2  386.82  4431.3  387.53  4781.4  385.97  4834.1  386.47
  4892.6  385.81  4935.5  383.19  4978.6  384.95  4994.0  384.14  5004.3  381.72
  5005.1  380.92  5014.2  380.92  5015.0  381.72  5025.0  383.16  5046.7  382.69
  5083.1  385.55  5126.7  386.62  5272.9  387.56  5378.0  387.18  5396.1  387.74
  5477.6  386.98  5548.2  384.24  5577.1  386.18  5653.2  387.09  5871.8  392.80
#Mann=3,-1,0
  3440.3     0.1       0  5004.3    0.07       0  5015.0     0.1       0
Bank Sta=5004.3,5015
Exp/Cntr=0.3,0.1

Type RM Length L Ch R = 1,31385,524,524,524
BEGIN DESCRIPTION:
Mapping XS e78bdce3
END DESCRIPTION:
XS GIS Cut Line= 3
      2045217.87     13427417.02      2045405.37     13426764.25
      2045950.26     13425525.24
#Sta/Elev= 30
  3854.1  387.21  3939.4  386.79  3991.5  387.45  4185.9  387.34  4241.2  386.68
  4397.2  387.45  4546.8  386.09  4622.3  386.36  4669.0  385.62  4715.7  386.14
  4820.0  384.30  4936.6  385.64  4958.5  385.06  4971.0  383.59  4983.5  380.28
  4984.3  379.48  4993.4  379.48  4994.2  380.28  5024.0  383.93  5087.7  385.40
  5139.8  384.79  5198.8  386.48  5351.8  386.44  5384.2  387.09  5488.5  386.62
  5570.3  385.12  5610.7  385.20  5639.5  383.98  5761.7  387.75  5886.8  390.54
#Mann=3,-1,0
  3854.1     0.1       0  4983.5    0.07       0  4994.2     0.1       0
Bank Sta=4983.5,4994.2
Exp/Cntr=0.3,0.1

Type RM Length L Ch R = 1,30861,599,599,599
BEGIN DESCRIPTION:
Mapping XS 7950858f
END DESCRIPTION:
XS GIS Cut Line= 3
      2045901.90     13427444.80      2045808.15     13426892.73
      2046151.87     13425569.93
#Sta/Elev= 30
  4144.1  385.49  4417.8  385.32  4559.8  385.90  4704.1  385.19  4754.9  383.77
  4790.3  383.82  4836.0  381.87  4866.2  382.05  4906.7  380.25  4918.7  381.07
  4939.4  380.21  4970.4  382.05  4987.8  381.05  4996.0  379.31  4996.8  378.51
  5005.9  378.51  5006.7  379.31  5033.5  383.23  5042.7  383.59  5347.6  385.42
  5428.7  384.58  5509.7  385.20  5626.2  383.94  5683.3  383.58  5702.1  384.03
  5714.3  383.33  5742.7  383.50  5920.9  387.89  6026.5  389.53  6070.8  390.90
#Mann=3,-1,0
  4144.1     0.1       0  4996.0    0.07       0  5006.7     0.1       0
Bank Sta=4996,5006.7
Exp/Cntr=0.3,0.1