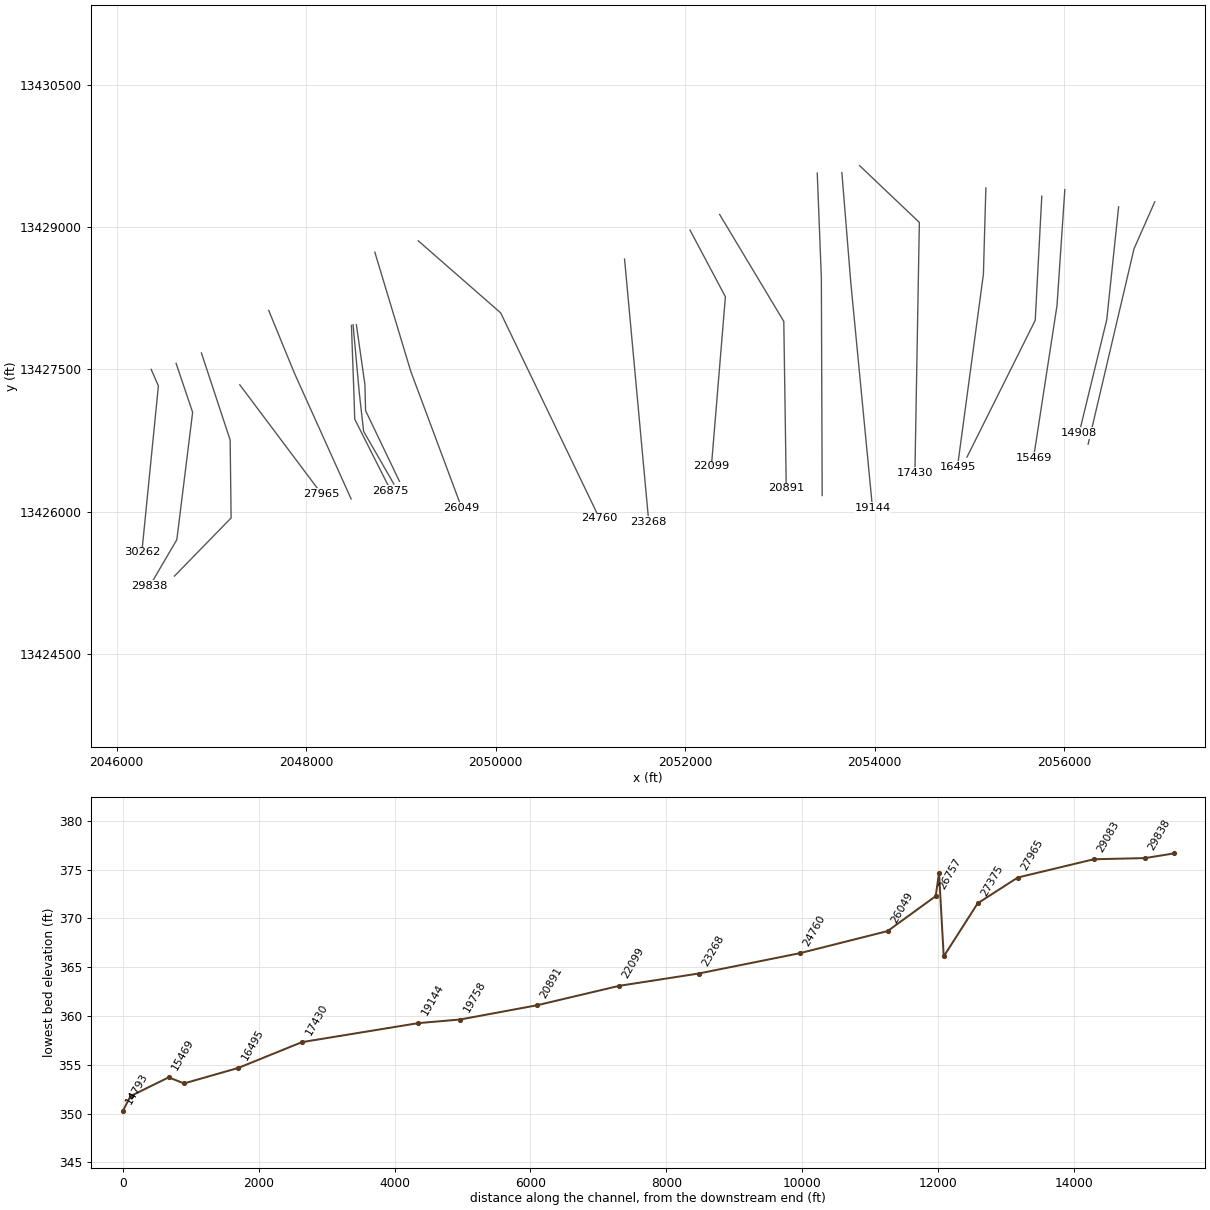
HEC-RAS study Raccoon Creek.prj: Raccoon Creek Base Level Engineering

--- Raccoon Creek.g01 (geometry) --- (continued)

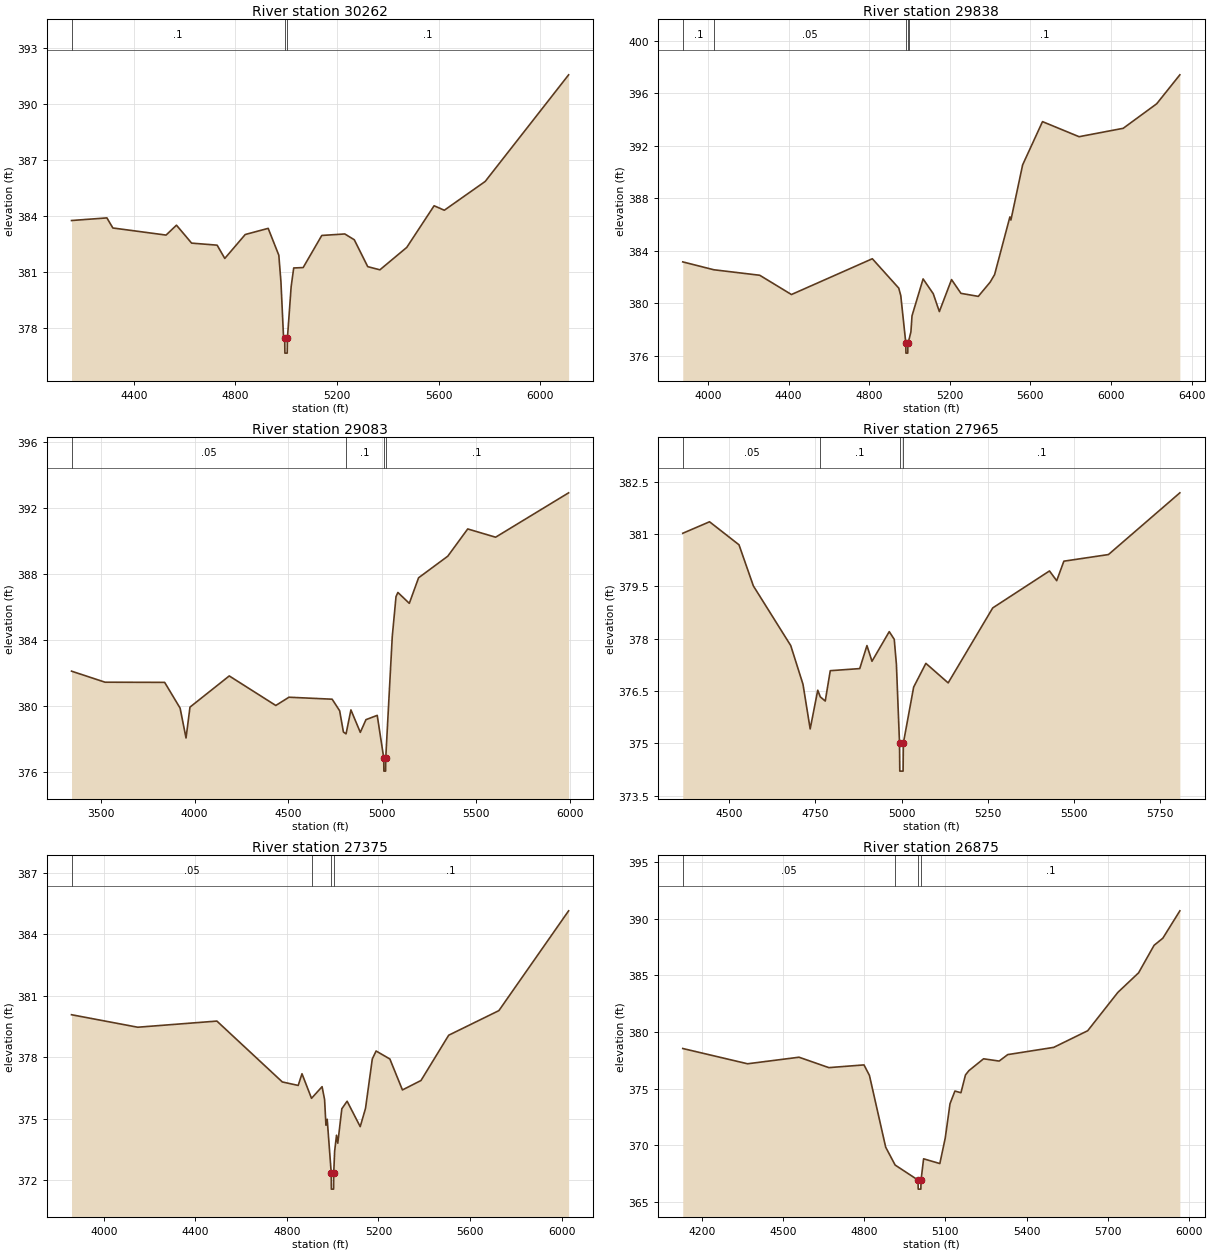
Type RM Length L Ch R = 1,30262,424,424,424
BEGIN DESCRIPTION:
Raccoon Creek 32.0
END DESCRIPTION:
XS GIS Cut Line= 3
      2046365.43     13427500.39      2046441.67     13427326.04
      2046266.66     13425568.12
#Sta/Elev= 30
  4155.2  383.77  4294.5  383.91  4317.9  383.37  4527.4  382.99  4568.4  383.52
  4627.9  382.56  4728.4  382.45  4758.6  381.74  4839.0  383.02  4929.4  383.35
  4971.3  381.91  4979.6  380.49  4989.7  377.57  4994.4  377.47  4995.2  376.67
  5004.3  376.67  5005.1  377.47  5019.8  380.23  5029.9  381.23  5067.0  381.25
  5140.4  382.97  5230.9  383.05  5268.4  382.74  5321.3  381.30  5369.2  381.13
  5474.9  382.33  5582.6  384.56  5622.8  384.32  5783.6  385.86  6112.1  391.57
#Mann=3,-1,0
  4155.2     0.1       0  4994.4    0.07       0  5005.1     0.1       0
Bank Sta=4994.4,5005.1
Exp/Cntr=0.3,0.1

Type RM Length L Ch R = 1,29838,755,755,755
BEGIN DESCRIPTION:
Mapping XS cbd43979
END DESCRIPTION:
XS GIS Cut Line= 4
      2046628.58     13427563.96      2046802.94     13427047.24
      2046636.27     13425703.49      2046349.93     13425214.10
#Sta/Elev= 30
  3875.2  383.15  4029.2  382.55  4257.1  382.13  4414.5  380.66  4815.8  383.39
  4946.8  381.15  4956.9  380.58  4981.7  376.99  4982.5  376.19  4991.6  376.19
  4992.4  376.99  4998.8  377.29  5007.2  377.81  5012.7  379.04  5067.7  381.85
  5118.1  380.72  5148.3  379.36  5208.8  381.80  5255.5  380.75  5341.5  380.52
  5400.2  381.60  5422.4  382.18  5498.3  386.58  5503.3  386.34  5561.5  390.55
  5660.1  393.85  5841.5  392.70  6060.5  393.34  6226.6  395.21  6341.6  397.42
#Mann=5,-1,0
  3875.2     0.1       0  4029.2    0.05       0  4981.7    0.07       0
  4992.4    0.05       0  4998.8     0.1       0
Bank Sta=4981.7,4992.4
Exp/Cntr=0.3,0.1

Type RM Length L Ch R = 1,29083,1118,1118,1118
BEGIN DESCRIPTION:
Mapping XS f709540d
END DESCRIPTION:
XS GIS Cut Line= 4
      2046895.49     13427674.02      2047198.77     13426755.57
      2047209.19     13425932.66      2046611.20     13425319.07
#Sta/Elev= 30
  3345.0  382.13  3523.6  381.46  3841.0  381.45  3923.2  379.89  3954.8  378.08
  3975.8  379.95  4184.9  381.84  4432.8  380.05  4502.8  380.55  4732.8  380.43
  4772.8  379.73  4792.8  378.44  4806.9  378.33  4832.8  379.78  4882.8  378.42
  4912.9  379.19  4972.9  379.45  5007.5  376.87  5008.3  376.07  5017.5  376.07
  5018.3  376.87  5052.9  384.22  5072.9  386.65  5082.9  386.90  5143.7  386.24
  5193.1  387.79  5348.7  389.10  5454.7  390.75  5603.3  390.25  5992.0  392.94
#Mann=4,-1,0
  3345.0    0.05       0  4806.9     0.1       0  5007.5    0.07       0
  5018.3     0.1       0
Bank Sta=5007.5,5018.3
Exp/Cntr=0.3,0.1

Type RM Length L Ch R = 1,27965,590,590,590
BEGIN DESCRIPTION:
Mapping XS c332f041
END DESCRIPTION:
XS GIS Cut Line= 2
      2047300.36     13427338.00      2048164.90     13426185.28
#Sta/Elev= 30
  4365.5  381.02  4443.1  381.35  4528.5  380.69  4570.2  379.51  4678.5  377.80
  4714.0  376.69  4734.8  375.41  4756.8  376.52  4764.1  376.33  4778.5  376.21
  4793.1  377.08  4878.5  377.14  4899.4  377.80  4914.0  377.35  4964.0  378.20
  4978.5  377.98  4984.8  377.26  4993.8  375.00  4994.6  374.20  5004.2  374.20
  5004.9  375.00  5034.8  376.61  5070.2  377.29  5134.8  376.73  5264.0  378.88
  5428.5  379.94  5449.4  379.66  5470.2  380.22  5599.4  380.41  5806.4  382.18
#Mann=4,-1,0
  4365.5    0.05       0  4764.1     0.1       0  4993.8    0.07       0
  5004.9     0.1       0
Bank Sta=4993.8,5004.9
Exp/Cntr=0.3,0.1

Type RM Length L Ch R = 1,27375,500,500,500
BEGIN DESCRIPTION:
Mapping XS 9c3fffc0
END DESCRIPTION:
XS GIS Cut Line= 3
      2047605.90     13428122.74      2047876.72     13427461.30
      2048475.70     13426133.15
#Sta/Elev= 30
  3859.4  380.07  4148.7  379.46  4494.5  379.76  4780.3  376.79  4849.7  376.62
  4866.3  377.19  4907.9  375.99  4954.0  376.56  4965.0  375.93  4970.9  374.68
  4976.4  374.97  4993.9  372.36  4994.6  371.56  5004.3  371.56  5005.0  372.36
  5008.9  373.41  5017.1  374.19  5022.6  373.80  5040.3  375.48  5063.4  375.85
  5120.6  374.61  5143.8  375.50  5173.4  377.91  5190.0  378.30  5250.2  377.91
  5305.1  376.40  5386.1  376.86  5507.2  379.07  5726.4  380.27  6031.1  385.14
#Mann=4,-1,0
  3859.4    0.05       0  4907.9     0.1       0  4993.9    0.07       0
  5005.0     0.1       0
Bank Sta=4993.9,5005
Exp/Cntr=0.3,0.1

Type RM Length L Ch R = 1,26875,69,69,69
BEGIN DESCRIPTION:
Mapping XS f6f6f52e
END DESCRIPTION:
XS GIS Cut Line= 4
      2048478.82     13427964.30      2048506.60     13427200.43
      2048513.54     13426974.74      2048894.94     13426218.88
#Sta/Elev= 30
  4129.6  378.54  4369.1  377.19  4559.2  377.77  4669.3  376.85  4799.3  377.09
  4819.4  376.16  4879.4  369.82  4914.3  368.24  4998.9  366.91  4999.6  366.11
  5009.4  366.11  5010.1  366.91  5019.5  368.79  5079.5  368.37  5099.5  370.63
  5117.1  373.66  5135.2  374.78  5157.5  374.63  5174.2  376.20  5186.7  376.58
  5241.1  377.63  5298.7  377.43  5330.3  378.00  5500.3  378.64  5625.8  380.11
  5737.3  383.50  5813.9  385.23  5871.1  387.66  5903.5  388.29  5966.4  390.71
#Mann=4,-1,0
  4129.6    0.05       0  4914.3     0.1       0  4998.9    0.07       0
  5010.1     0.1       0
Bank Sta=4998.9,5010.1
Exp/Cntr=0.3,0.1

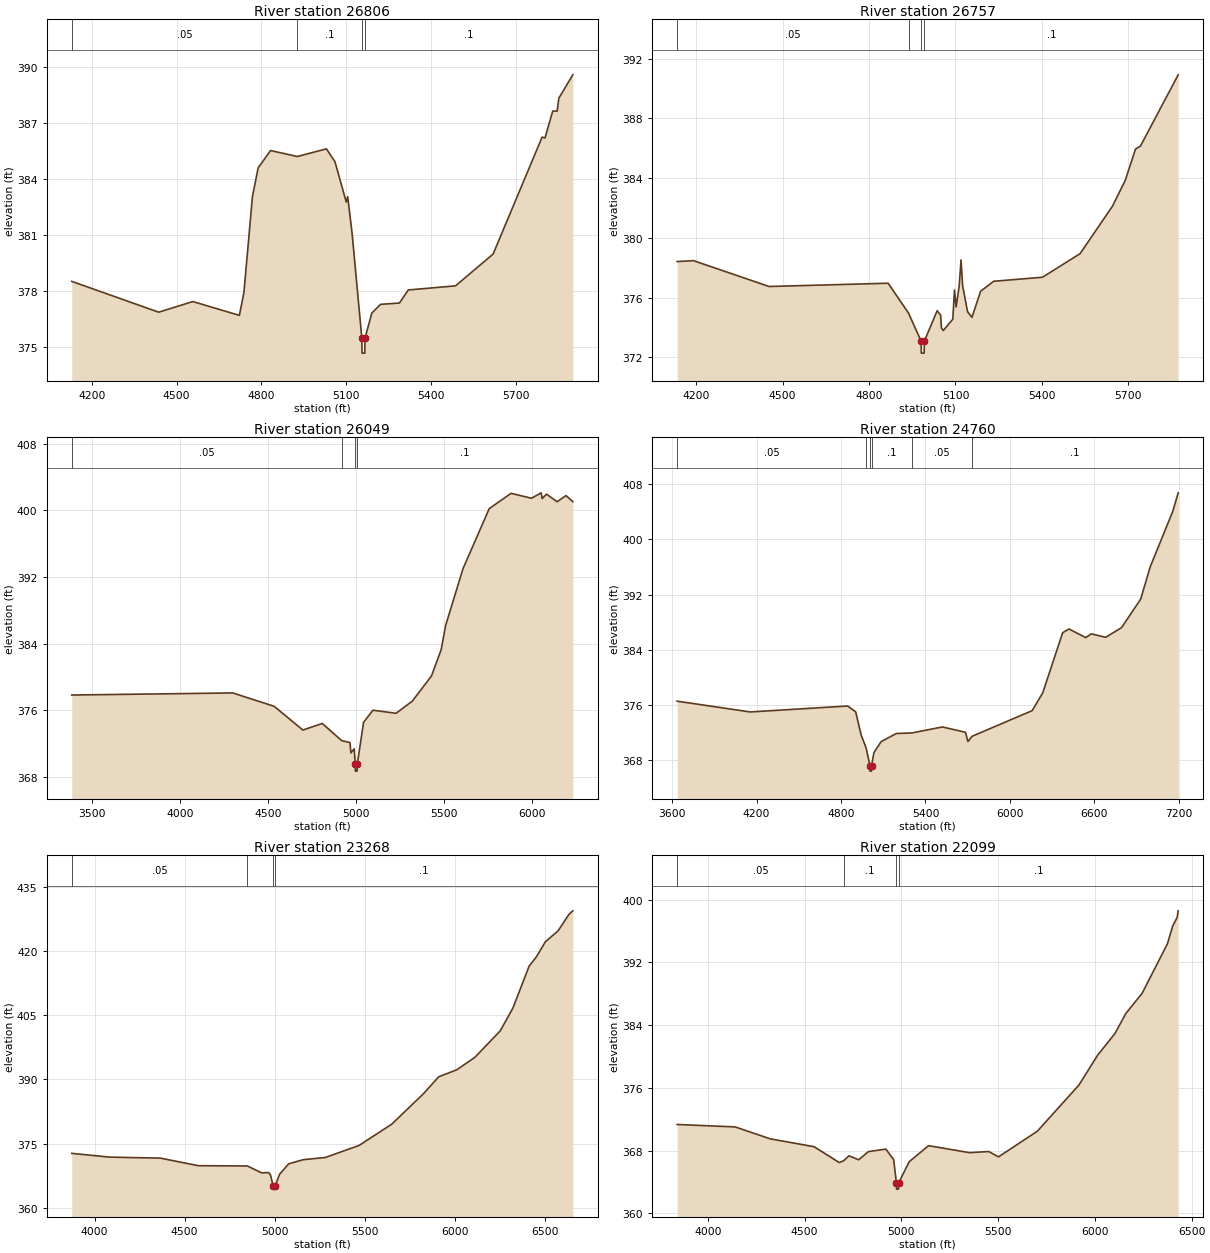
Type RM Length L Ch R = 1,26806,49,49,49
BEGIN DESCRIPTION:
Mapping XS 6eab8520
END DESCRIPTION:
XS GIS Cut Line= 4
      2048496.18     13427971.30      2048562.15     13427249.04
      2048607.29     13426846.27      2048926.73     13426290.72
#Sta/Elev= 30
  4129.2  378.53  4436.8  376.88  4557.3  377.45  4721.9  376.71  4738.0  377.94
  4768.1  383.07  4788.2  384.60  4832.1  385.53  4926.9  385.21  5029.6  385.62
  5059.8  384.93  5099.7  382.77  5104.8  383.06  5120.2  381.12  5154.8  375.49
  5155.5  374.69  5165.3  374.69  5166.0  375.49  5189.9  376.83  5220.8  377.30
  5287.7  377.37  5318.9  378.07  5486.0  378.29  5618.8  379.99  5792.2  386.25
  5802.2  386.20  5829.6  387.64  5845.4  387.64  5851.1  388.33  5900.6  389.58
#Mann=4,-1,0
  4129.2    0.05       0  4926.9     0.1       0  5154.8    0.07       0
  5166.0     0.1       0
Bank Sta=5154.8,5166
Exp/Cntr=0.3,0.1

Type RM Length L Ch R = 1,26757,708,708,708
BEGIN DESCRIPTION:
Mapping XS f3897df9
END DESCRIPTION:
XS GIS Cut Line= 4
      2048530.90     13427971.28      2048621.18     13427339.32
      2048628.13     13427065.02      2048985.40     13426319.25
#Sta/Elev= 30
  4133.7  378.42  4190.6  378.48  4453.2  376.75  4866.4  376.97  4937.1  374.97
  4980.9  373.09  4981.6  372.29  4991.4  372.29  4992.1  373.09  5036.5  375.13
  5048.6  374.83  5051.4  373.98  5057.6  373.80  5090.8  374.56  5096.7  376.52
  5102.3  375.38  5113.0  376.78  5119.4  378.53  5124.9  376.81  5142.1  375.06
  5157.4  374.69  5187.4  376.43  5232.7  377.10  5402.4  377.37  5532.8  378.95
  5645.3  382.13  5689.6  383.86  5725.2  385.95  5742.3  386.15  5873.4  390.92
#Mann=4,-1,0
  4133.7    0.05       0  4937.1     0.1       0  4980.9    0.07       0
  4992.1     0.1       0
Bank Sta=4980.9,4992.1
Exp/Cntr=0.3,0.1

Type RM Length L Ch R = 1,26049,1289,1289,1289
BEGIN DESCRIPTION:
Mapping XS acc38ff9
END DESCRIPTION:
XS GIS Cut Line= 3
      2048725.67     13428737.39      2049105.89     13427476.93
      2049642.25     13426039.70
#Sta/Elev= 30
  3382.4  377.84  4298.3  378.09  4533.8  376.49  4697.4  373.64  4807.8  374.43
  4918.0  372.37  4965.3  372.14  4970.7  370.90  4989.2  371.39  4995.4  369.51
  4996.1  368.71  5005.9  368.71  5006.6  369.51  5042.6  374.56  5095.9  376.02
  5227.4  375.65  5320.1  377.11  5429.0  380.13  5484.2  383.28  5509.2  386.17
  5608.3  393.00  5757.7  400.21  5881.9  402.04  5997.8  401.45  6053.1  402.10
  6058.4  401.41  6083.4  401.94  6144.0  401.03  6194.0  401.77  6233.0  401.05
#Mann=4,-1,0
  3382.4    0.05       0  4918.0     0.1       0  4995.4    0.07       0
  5006.6     0.1       0
Bank Sta=4995.4,5006.6
Exp/Cntr=0.3,0.1

Type RM Length L Ch R = 1,24760,1492,1492,1492
BEGIN DESCRIPTION:
Mapping XS a6153fca
END DESCRIPTION:
XS GIS Cut Line= 3
      2049184.00     13428857.15      2050053.81     13428096.72
      2051095.47     13425930.06
#Sta/Elev= 30
  3635.8  376.57  4155.2  375.01  4847.3  375.87  4904.0  375.04  4943.4  371.66
  4978.5  369.79  5005.6  367.25  5006.3  366.45  5016.2  366.45  5016.9  367.25
  5033.9  369.13  5084.7  370.71  5192.4  371.89  5304.8  371.98  5520.4  372.84
  5684.3  372.07  5701.4  370.73  5731.0  371.49  6157.8  375.20  6233.1  377.78
  6374.5  386.48  6419.8  387.01  6538.5  385.77  6578.2  386.31  6679.9  385.81
  6793.0  387.21  6928.8  391.34  6996.7  396.02  7155.2  403.95  7195.2  406.71
#Mann=6,-1,0
  3635.8    0.05       0  4978.5     0.1       0  5005.6    0.07       0
  5016.9     0.1       0  5304.8    0.05       0  5731.0     0.1       0
Bank Sta=5005.6,5016.9
Exp/Cntr=0.3,0.1

Type RM Length L Ch R = 1,23268,1169,1169,1169
BEGIN DESCRIPTION:
Mapping XS bf236455
END DESCRIPTION:
XS GIS Cut Line= 2
      2051361.10     13428664.44      2051616.31     13425893.57
#Sta/Elev= 30
  3873.5  372.72  4084.2  371.84  4365.0  371.61  4575.9  369.84  4849.5  369.77
  4927.4  368.17  4967.6  368.23  4977.6  367.62  4992.0  365.16  4992.6  364.36
  5002.7  364.36  5003.4  365.16  5027.8  367.83  5078.0  370.27  5158.4  371.24
  5281.4  371.75  5469.7  374.58  5650.4  379.54  5825.1  386.59  5911.5  390.62
  6012.0  392.26  6112.4  395.17  6253.0  401.35  6323.3  406.67  6413.6  416.49
  6453.8  418.66  6504.0  422.19  6574.3  424.73  6634.6  428.58  6656.1  429.41
#Mann=4,-1,0
  3873.5    0.05       0  4849.5     0.1       0  4992.0    0.07       0
  5003.4     0.1       0
Bank Sta=4992,5003.4
Exp/Cntr=0.3,0.1

Type RM Length L Ch R = 1,22099,1208,1208,1208
BEGIN DESCRIPTION:
Mapping XS 36729c1c
END DESCRIPTION:
XS GIS Cut Line= 3
      2052052.08     13428969.96      2052425.34     13428266.86
      2052277.82     13426479.37
#Sta/Elev= 30
  3841.0  371.34  4141.0  371.03  4321.8  369.51  4548.6  368.51  4679.0  366.49
  4701.3  366.71  4729.2  367.35  4779.4  366.84  4829.5  367.88  4919.9  368.20
  4960.0  366.86  4974.4  363.90  4975.0  363.10  4985.1  363.10  4985.8  363.90
  5040.3  366.59  5140.6  368.64  5351.3  367.75  5451.7  367.89  5501.8  367.21
  5702.5  370.48  5918.0  376.38  6013.6  380.15  6103.9  382.94  6160.0  385.49
  6244.3  388.07  6374.8  394.36  6402.0  396.63  6425.0  397.71  6430.6  398.57
#Mann=4,-1,0
  3841.0    0.05       0  4701.3     0.1       0  4974.4    0.07       0
  4985.8     0.1       0
Bank Sta=4974.4,4985.8
Exp/Cntr=0.3,0.1

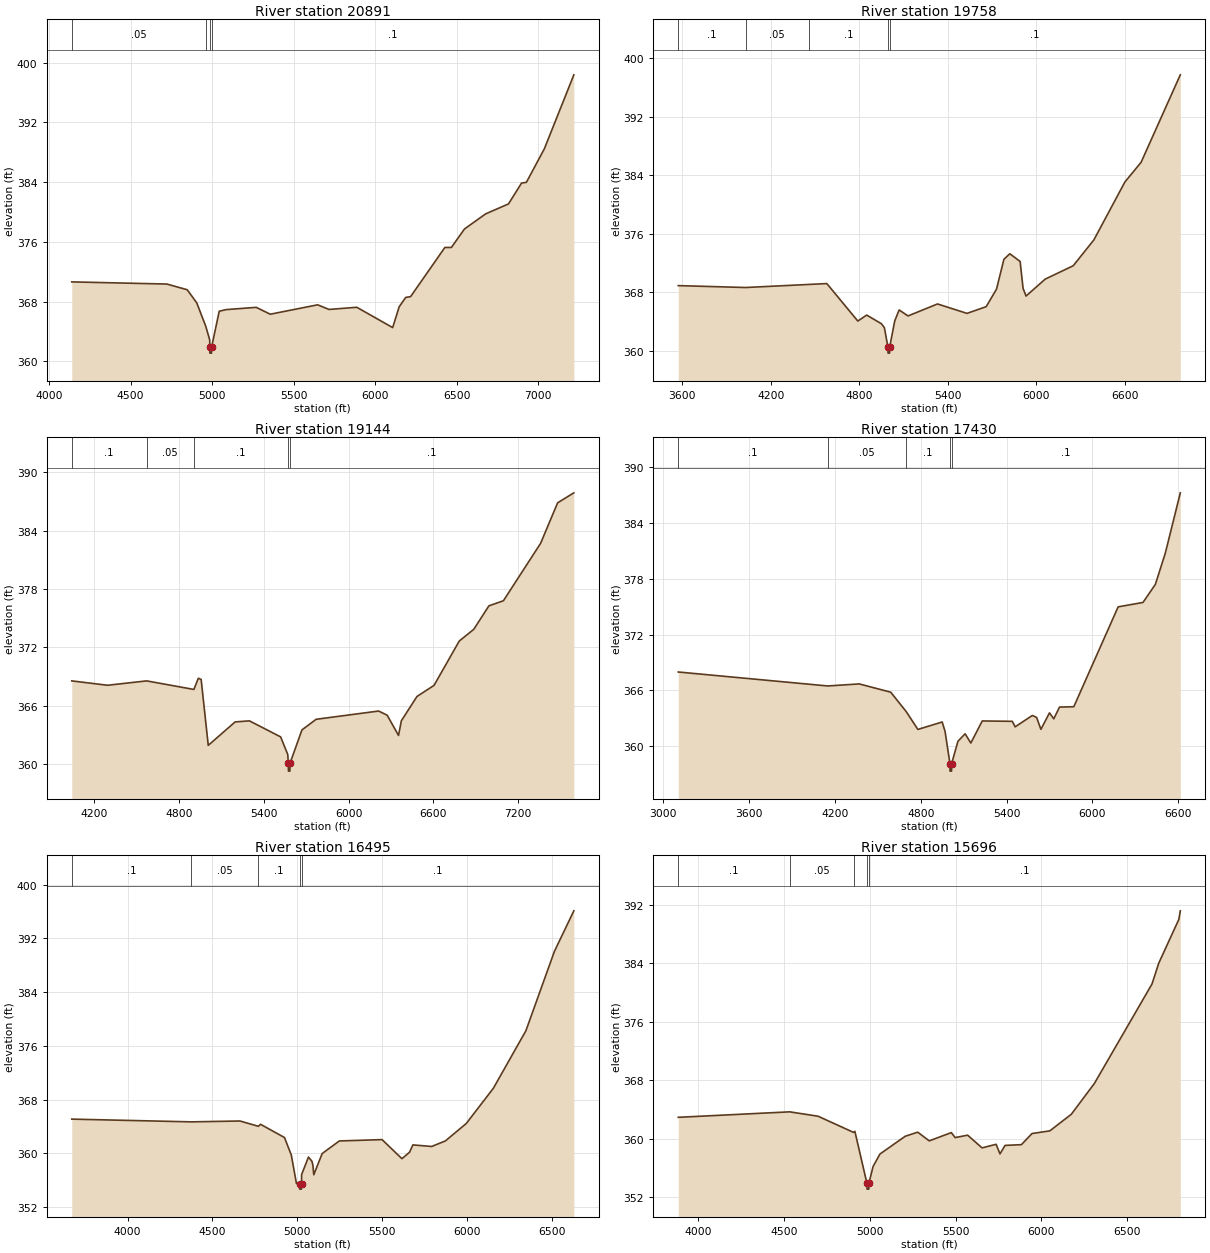
Type RM Length L Ch R = 1,20891,1133,1133,1133
BEGIN DESCRIPTION:
Mapping XS 77e2becc
END DESCRIPTION:
XS GIS Cut Line= 3
      2052364.59     13429134.88      2053041.66     13428006.44
      2053067.70     13426244.30
#Sta/Elev= 30
  4139.7  370.65  4722.7  370.36  4847.5  369.60  4905.8  367.85  4960.9  364.73
  4985.5  362.88  4985.6  361.91  4986.3  361.11  4996.4  361.11  4997.0  361.91
  5043.8  366.72  5086.6  366.94  5270.8  367.24  5356.7  366.32  5647.1  367.58
  5717.1  366.96  5887.2  367.25  6107.2  364.53  6147.2  367.32  6187.2  368.57
  6217.2  368.68  6427.2  375.26  6467.2  375.26  6547.2  377.73  6677.2  379.76
  6817.3  381.09  6897.3  383.88  6927.3  383.99  7037.3  388.48  7218.0  398.38
#Mann=4,-1,0
  4139.7    0.05       0  4960.9     0.1       0  4985.6    0.07       0
  4997.0     0.1       0
Bank Sta=4985.6,4997
Exp/Cntr=0.3,0.1

Type RM Length L Ch R = 1,19758,614,614,614
BEGIN DESCRIPTION:
Raccoon Creek 20.0
END DESCRIPTION:
XS GIS Cut Line= 3
      2053394.61     13429571.43      2053438.01     13428469.03
      2053446.69     13426169.30
#Sta/Elev= 30
  3573.6  368.89  4029.8  368.63  4459.1  369.05  4580.8  369.17  4790.9  364.04
  4850.9  364.86  4950.9  363.67  4970.9  363.13  4995.2  360.45  4995.8  359.65
  5006.0  359.65  5006.6  360.45  5040.9  364.05  5070.9  365.56  5130.9  364.74
  5330.9  366.38  5530.9  365.09  5660.9  366.01  5730.9  368.41  5780.9  372.49
  5820.9  373.25  5890.9  372.20  5910.9  368.51  5930.9  367.46  6060.9  369.78
  6250.9  371.61  6390.9  375.15  6600.9  383.07  6710.9  385.77  6976.6  397.74
#Mann=5,-1,0
  3573.6     0.1       0  4029.8    0.05       0  4459.1     0.1       0
  4995.2    0.07       0  5006.6     0.1       0
Bank Sta=4995.2,5006.6
Exp/Cntr=0.3,0.1

Type RM Length L Ch R = 1,19144,1714,1714,1714
BEGIN DESCRIPTION:
Mapping XS d14d50c6
END DESCRIPTION:
XS GIS Cut Line= 3
      2053654.50     13429577.23      2053748.25     13428420.94
      2053977.42     13426040.73
#Sta/Elev= 30
  4042.6  368.56  4295.7  368.11  4572.2  368.56  4906.4  367.68  4937.8  368.83
  4957.8  368.71  5008.0  361.93  5198.1  364.34  5299.1  364.45  5520.1  362.80
  5570.3  361.00  5574.6  360.08  5575.3  359.28  5585.5  359.28  5586.1  360.08
  5670.8  363.52  5771.2  364.61  6213.3  365.46  6273.6  365.03  6353.9  362.95
  6374.0  364.46  6484.5  366.96  6605.1  368.10  6783.5  372.66  6885.9  373.86
  6993.3  376.28  7095.7  376.80  7358.6  382.70  7479.1  386.87  7593.9  387.90
#Mann=5,-1,0
  4042.6     0.1       0  4572.2    0.05       0  4906.4     0.1       0
  5574.6    0.07       0  5586.1     0.1       0
Bank Sta=5574.6,5586.1
Exp/Cntr=0.3,0.1

Type RM Length L Ch R = 1,17430,935,935,935
BEGIN DESCRIPTION:
Mapping XS a3e9657e
END DESCRIPTION:
XS GIS Cut Line= 3
      2053842.00     13429650.10      2054472.21     13429051.15
      2054425.34     13426410.49
#Sta/Elev= 30
  3103.8  367.98  4149.0  366.48  4369.4  366.70  4589.5  365.81  4697.1  363.74
  4779.5  361.81  4949.5  362.61  4969.5  361.59  5003.8  358.13  5004.4  357.33
  5014.6  357.33  5015.3  358.13  5059.5  360.54  5109.6  361.34  5149.6  360.35
  5229.6  362.72  5439.6  362.68  5459.6  362.09  5579.6  363.31  5609.6  363.10
  5639.6  361.82  5699.6  363.59  5729.7  362.95  5769.7  364.21  5869.7  364.25
  6179.7  374.98  6353.1  375.45  6439.8  377.39  6509.8  380.77  6614.3  387.23
#Mann=5,-1,0
  3103.8     0.1       0  4149.0    0.05       0  4697.1     0.1       0
  5003.8    0.07       0  5015.3     0.1       0
Bank Sta=5003.8,5015.3
Exp/Cntr=0.3,0.1

Type RM Length L Ch R = 1,16495,799,799,799
BEGIN DESCRIPTION:
Raccoon Creek 19.0
END DESCRIPTION:
XS GIS Cut Line= 3
      2055174.12     13429415.19      2055148.08     13428503.75
      2054874.99     13426474.96
#Sta/Elev= 30
  3671.1  365.11  4376.2  364.70  4662.4  364.83  4771.0  364.04  4783.5  364.34
  4924.7  362.37  4965.1  359.75  4995.3  355.51  5013.7  355.49  5014.3  354.69
  5024.5  354.69  5025.2  355.49  5025.6  356.85  5066.0  359.46  5086.2  358.85
  5092.2  358.27  5097.3  356.83  5146.7  359.98  5247.9  361.86  5499.9  362.06
  5616.9  359.22  5661.3  360.17  5681.5  361.27  5792.5  361.04  5873.2  361.87
  5996.1  364.46  6155.7  369.70  6347.4  378.26  6515.7  390.09  6630.0  396.11
#Mann=5,-1,0
  3671.1     0.1       0  4376.2    0.05       0  4771.0     0.1       0
  5013.7    0.07       0  5025.2     0.1       0
Bank Sta=5013.7,5025.2
Exp/Cntr=0.3,0.1

Type RM Length L Ch R = 1,15696,227,227,227
BEGIN DESCRIPTION:
Raccoon Creek 18.0
END DESCRIPTION:
XS GIS Cut Line= 3
      2055764.40     13429328.42      2055694.95     13428017.64
      2054975.01     13426575.02
#Sta/Elev= 30
  3883.8  362.92  4533.0  363.67  4698.4  363.07  4905.2  360.86  4912.8  361.01
  4983.0  353.90  4983.7  353.10  4993.9  353.10  4994.5  353.90  5018.8  356.19
  5058.9  357.90  5206.2  360.33  5278.9  360.89  5346.1  359.70  5474.7  360.83
  5497.1  360.15  5569.8  360.48  5653.7  358.74  5735.8  359.23  5758.2  357.92
  5787.9  359.08  5883.0  359.18  5944.6  360.70  6048.7  361.07  6173.9  363.34
  6308.1  367.55  6643.7  381.15  6682.9  383.99  6800.3  390.00  6808.7  391.16
#Mann=5,-1,0
  3883.8     0.1       0  4533.0    0.05       0  4905.2     0.1       0
  4983.0    0.07       0  4994.5     0.1       0
Bank Sta=4983,4994.5
Exp/Cntr=0.3,0.1

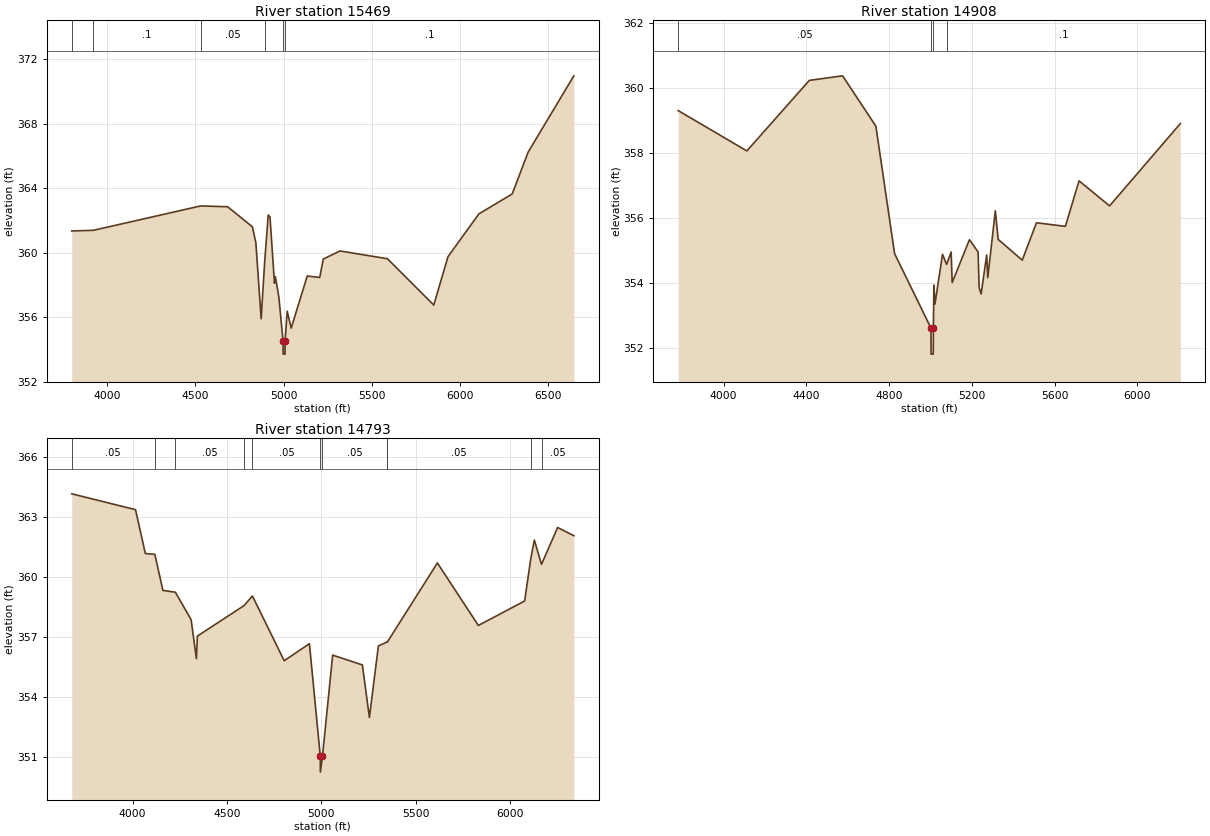
Type RM Length L Ch R = 1,15469,561,561,561
BEGIN DESCRIPTION:
Raccoon Creek 17.0
END DESCRIPTION:
XS GIS Cut Line= 3
      2056007.46     13429397.87      2055925.00     13428175.00
      2055677.74     13426568.96
#Sta/Elev= 30
  3797.7  361.35  3920.8  361.39  4529.2  362.90  4682.6  362.85  4822.9  361.61
  4842.9  360.62  4873.0  355.91  4893.0  359.45  4913.1  362.34  4923.1  362.22
  4948.6  358.11  4953.6  358.52  4973.2  357.28  4997.5  354.52  4998.1  353.72
  5008.4  353.72  5009.0  354.52  5020.8  356.38  5043.6  355.33  5134.6  358.56
  5205.5  358.47  5225.7  359.61  5320.4  360.11  5589.9  359.63  5853.0  356.76
  5933.9  359.76  6109.4  362.41  6298.2  363.64  6389.2  366.24  6648.3  370.96
#Mann=6,-1,0
  3797.7    0.05       0  3920.8     0.1       0  4529.2    0.05       0
  4893.0     0.1       0  4997.5    0.07       0  5009.0     0.1       0
Bank Sta=4997.5,5009
Exp/Cntr=0.3,0.1

Type RM Length L Ch R = 1,14908,115,115,115
BEGIN DESCRIPTION:
Raccoon Creek 16.0
END DESCRIPTION:
XS GIS Cut Line= 3
      2056575.16     13429215.56      2056450.00     13428025.00
      2056158.69     13426829.19
#Sta/Elev= 30
  3780.4  359.29  4112.2  358.05  4414.4  360.22  4575.3  360.36  4736.2  358.81
  4826.7  354.89  5002.5  352.60  5003.1  351.80  5013.7  351.80  5014.2  352.60
  5016.7  353.92  5021.8  353.34  5058.4  354.87  5078.1  354.56  5100.1  354.94
  5105.2  354.00  5188.6  355.32  5230.4  354.94  5235.5  353.85  5245.1  353.65
  5272.1  354.85  5277.2  354.15  5313.8  356.21  5327.5  355.33  5444.0  354.69
  5512.7  355.84  5652.6  355.73  5718.6  357.13  5866.3  356.36  6208.3  358.89
#Mann=4,-1,0
  3780.4    0.05       0  5002.5    0.04       0  5014.2    0.05       0
  5078.1     0.1       0
Bank Sta=5002.5,5014.2
Exp/Cntr=0.3,0.1

Type RM Length L Ch R = 1,14793,264,264,264
BEGIN DESCRIPTION:
Mapping XS d64da9cc
END DESCRIPTION:
XS GIS Cut Line= 3
      2056956.59     13429268.61      2056737.84     13428773.80
      2056253.47     13426711.33
#Sta/Elev= 30
  3677.9  364.14  4015.5  363.35  4067.6  361.16  4117.8  361.12  4160.8  359.32
  4226.6  359.23  4310.1  357.86  4338.2  355.91  4343.4  357.04  4590.3  358.56
  4634.9  359.04  4803.2  355.81  4936.7  356.66  4994.3  351.05  4994.8  350.25
  5006.0  351.05  5060.0  356.09  5217.3  355.60  5254.6  352.98  5302.2  356.55
  5349.0  356.75  5349.5  356.74  5614.7  360.69  5831.7  357.57  6076.9  358.79
  6109.7  360.92  6128.3  361.83  6166.2  360.62  6251.6  362.46  6337.5  362.05
#Mann=11,-1,0
  3677.9    0.05       0  4117.8    0.08       0  4226.6    0.05       0
  4590.3    0.08       0  4634.9    0.05       0  4994.3    0.04       0
  5006.0    0.05       0  5349.0     0.1       0  5349.5    0.05       0
  6109.7    0.08       0  6166.2    0.05       0
Bank Sta=4994.3,5006
Exp/Cntr=0.3,0.1