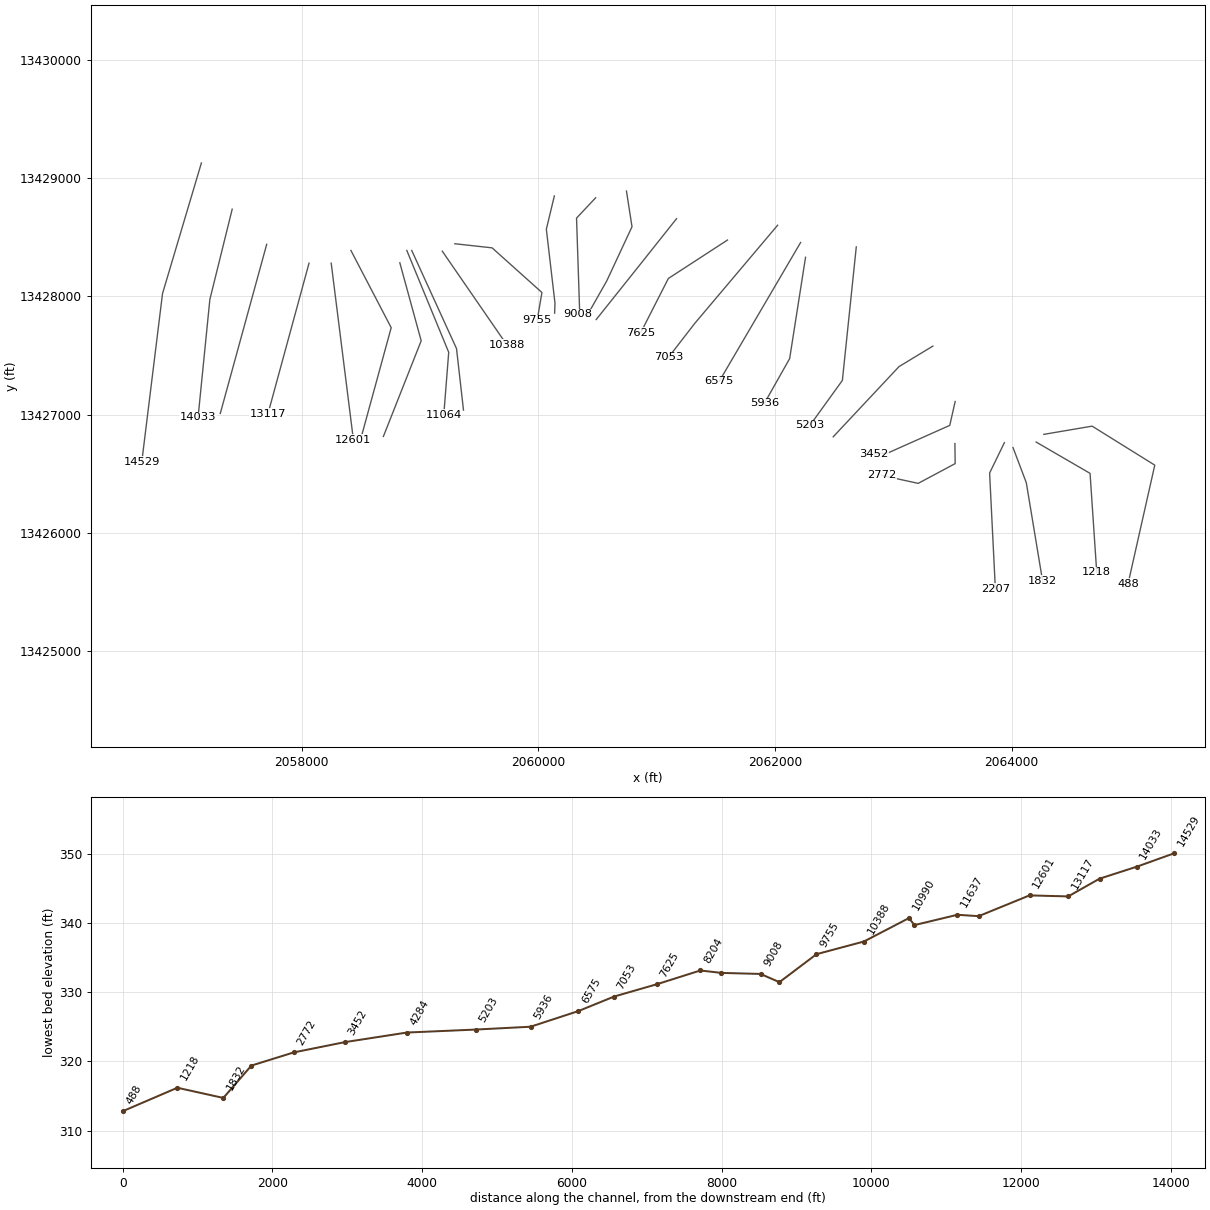
HEC-RAS study Raccoon Creek.prj: Raccoon Creek Base Level Engineering

--- Raccoon Creek.g01 (geometry) --- (continued)

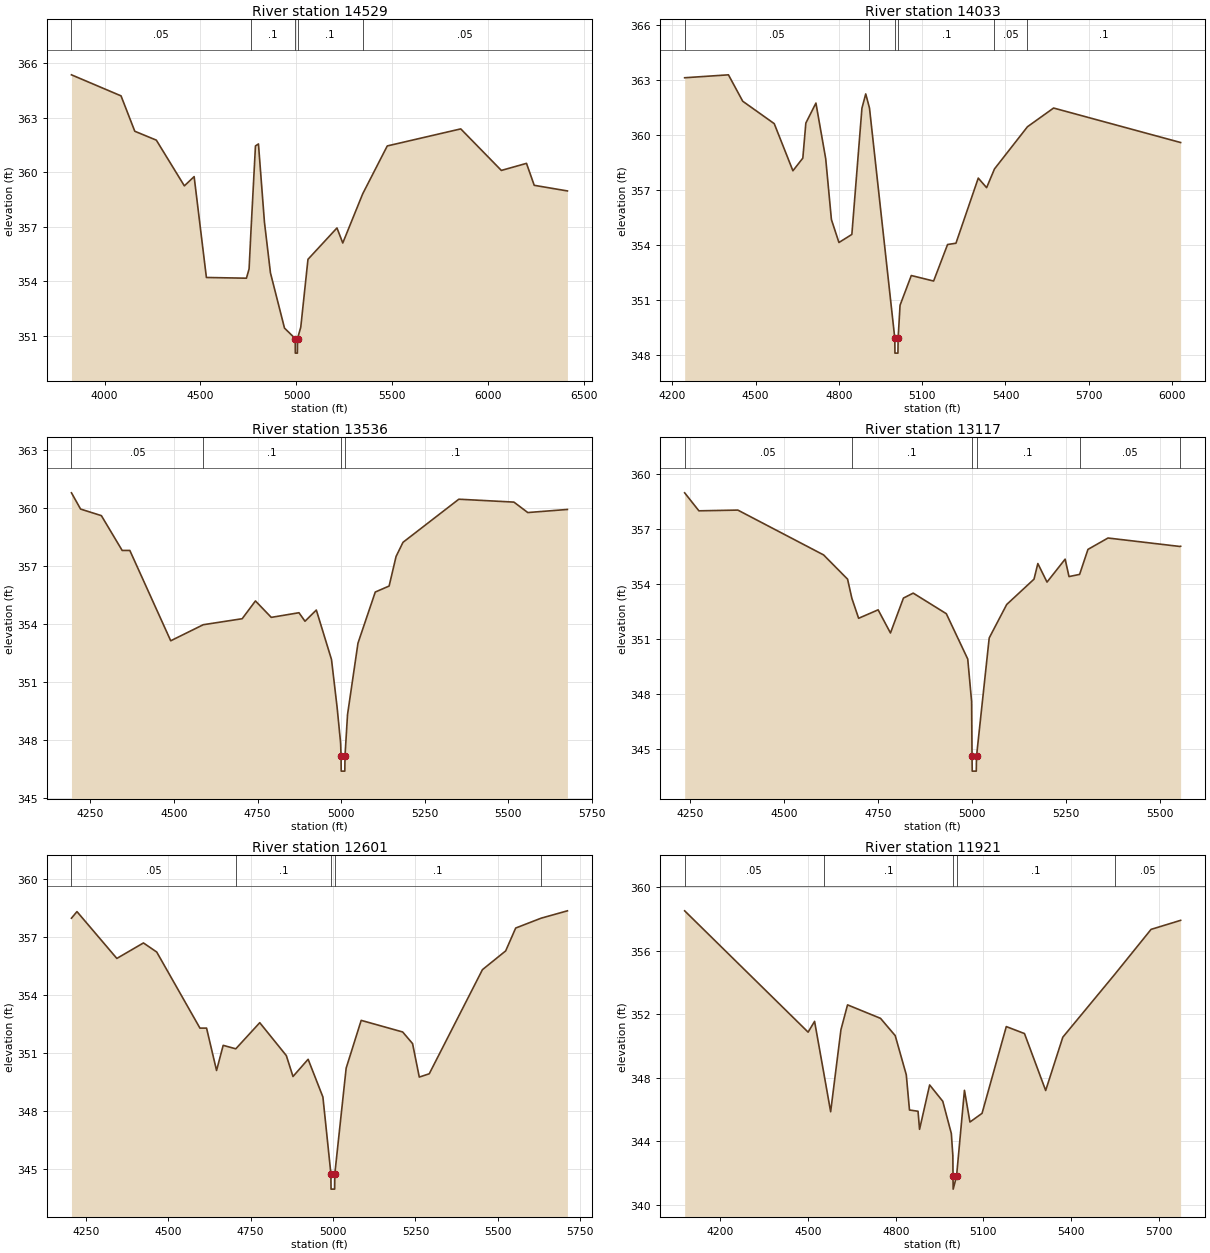
Type RM Length L Ch R = 1,14529,496,496,496
BEGIN DESCRIPTION:
Raccoon Creek 15.0
END DESCRIPTION:
XS GIS Cut Line= 3
      2057153.30     13429128.79      2056825.00     13428025.00
      2056649.90     13426603.43
#Sta/Elev= 30
  3827.8  365.37  4086.1  364.21  4157.7  362.26  4269.9  361.77  4416.0  359.25
  4466.9  359.76  4530.8  354.20  4739.4  354.16  4753.2  354.67  4763.5  356.86
  4786.4  361.45  4802.0  361.56  4833.3  357.24  4864.6  354.45  4937.7  351.41
  4993.6  350.83  4994.1  350.03  5004.9  350.03  5005.5  350.83  5022.5  351.46
  5060.0  355.20  5211.1  356.93  5241.3  356.10  5345.1  358.81  5473.1  361.45
  5856.0  362.39  6067.5  360.10  6198.5  360.49  6238.8  359.28  6411.7  358.97
#Mann=5,-1,0
  3827.8    0.05       0  4763.5     0.1       0  4993.6    0.07       0
  5005.5     0.1       0  5345.1    0.05       0
Bank Sta=4993.6,5005.5
Exp/Cntr=0.3,0.1

Type RM Length L Ch R = 1,14033,497,497,497
BEGIN DESCRIPTION:
Raccoon Creek 14.0
END DESCRIPTION:
XS GIS Cut Line= 3
      2057413.70     13428738.13      2057225.00     13427975.00
      2057125.54     13426979.77
#Sta/Elev= 30
  4244.5  363.12  4402.2  363.28  4453.7  361.84  4567.1  360.62  4634.4  358.05
  4670.1  358.74  4681.0  360.65  4717.3  361.74  4752.5  358.71  4773.1  355.39
  4800.2  354.14  4846.7  354.58  4883.0  361.46  4896.7  362.24  4910.2  361.47
  5001.4  348.91  5001.9  348.11  5012.7  348.11  5013.3  348.91  5020.3  350.72
  5060.8  352.34  5141.2  352.04  5191.4  354.03  5221.6  354.10  5302.0  357.65
  5332.1  357.13  5360.4  358.15  5479.2  360.45  5573.3  361.47  6030.8  359.59
#Mann=6,-1,0
  4244.5    0.05       0  4910.2     0.1       0  5001.4    0.07       0
  5013.3     0.1       0  5360.4    0.05       0  5479.2     0.1       0
Bank Sta=5001.4,5013.3
Exp/Cntr=0.3,0.1

Type RM Length L Ch R = 1,13536,419,419,419
BEGIN DESCRIPTION:
Mapping XS bba36538
END DESCRIPTION:
XS GIS Cut Line= 2
      2057705.38     13428441.30      2057313.02     13427010.73
#Sta/Elev= 30
  4193.3  360.77  4220.6  359.93  4282.8  359.59  4345.0  357.79  4367.9  357.79
  4490.2  353.12  4587.5  353.95  4703.9  354.26  4743.6  355.18  4790.9  354.33
  4873.8  354.57  4891.8  354.13  4925.7  354.71  4971.1  352.15  4987.9  349.67
  4998.3  347.84  4999.6  347.18  5000.1  346.38  5010.9  346.38  5011.5  347.18
  5019.0  349.30  5050.3  353.00  5102.0  355.64  5143.4  355.95  5164.2  357.48
  5184.9  358.21  5351.9  360.44  5516.7  360.29  5558.2  359.75  5676.7  359.91
#Mann=4,-1,0
  4193.3    0.05       0  4587.5     0.1       0  4999.6    0.07       0
  5011.5     0.1       0
Bank Sta=4999.6,5011.5
Exp/Cntr=0.3,0.1

Type RM Length L Ch R = 1,13117,516,516,516
BEGIN DESCRIPTION:
Mapping XS b27c5e28
END DESCRIPTION:
XS GIS Cut Line= 2
      2058063.02     13428281.57      2057716.16     13427008.58
#Sta/Elev= 30
  4236.1  358.97  4274.0  357.99  4377.6  358.03  4605.7  355.59  4669.5  354.27
  4680.9  353.23  4698.9  352.14  4750.8  352.60  4783.6  351.34  4818.1  353.24
  4844.1  353.51  4932.2  352.39  4989.2  349.92  4999.5  347.60  5000.6  344.62
  5001.1  343.82  5011.9  343.82  5012.5  344.62  5046.3  351.07  5092.8  352.89
  5165.5  354.27  5175.7  355.12  5200.1  354.11  5248.3  355.36  5258.6  354.41
  5286.8  354.53  5309.0  355.89  5362.3  356.51  5553.5  356.05  5555.5  356.06
#Mann=6,-1,0
  4236.1    0.05       0  4680.9     0.1       0  5000.6    0.07       0
  5012.5     0.1       0  5286.8    0.05       0  5553.5     0.1       0
Bank Sta=5000.6,5012.5
Exp/Cntr=0.3,0.1

Type RM Length L Ch R = 1,12601,680,680,680
BEGIN DESCRIPTION:
Mapping XS 82904cbe
END DESCRIPTION:
XS GIS Cut Line= 2
      2058250.51     13428281.56      2058437.91     13426789.28
#Sta/Elev= 30
  4206.8  357.97  4223.5  358.31  4344.4  355.89  4425.1  356.69  4465.4  356.22
  4596.4  352.29  4616.5  352.29  4646.8  350.10  4666.9  351.40  4705.1  351.22
  4777.8  352.57  4858.4  350.87  4878.6  349.79  4924.5  350.68  4969.3  348.73
  4993.5  344.77  4994.0  343.97  5005.0  343.97  5005.5  344.77  5039.8  350.22
  5085.4  352.69  5211.2  352.09  5241.2  351.49  5261.6  349.76  5291.8  349.93
  5453.1  355.31  5523.6  356.28  5553.9  357.46  5631.0  357.97  5710.8  358.35
#Mann=5,-1,0
  4206.8    0.05       0  4705.1     0.1       0  4993.5    0.07       0
  5005.5     0.1       0  5631.0    0.05       0
Bank Sta=4993.5,5005.5
Exp/Cntr=0.3,0.1

Type RM Length L Ch R = 1,11921,284,284,284
BEGIN DESCRIPTION:
Mapping XS 31292106
END DESCRIPTION:
XS GIS Cut Line= 3
      2058417.16     13428389.19      2058757.45     13427736.39
      2058504.08     13426809.67
#Sta/Elev= 30
  4077.8  358.52  4500.2  350.87  4522.3  351.55  4553.1  348.37  4577.3  345.85
  4612.5  351.02  4635.1  352.59  4747.9  351.74  4798.2  350.65  4836.1  348.18
  4847.0  345.96  4876.3  345.88  4881.5  344.74  4916.0  347.54  4960.9  346.51
  4990.2  344.48  4995.4  343.09  4996.0  341.77  4996.5  340.97  5008.0  341.77
  5035.1  347.20  5053.9  345.20  5095.3  345.75  5178.3  351.22  5240.5  350.78
  5313.0  347.19  5371.6  350.55  5549.2  354.51  5673.6  357.35  5774.7  357.92
#Mann=5,-1,0
  4077.8    0.05       0  4553.1     0.1       0  4996.0    0.07       0
  5008.0     0.1       0  5549.2    0.05       0
Bank Sta=4996,5008
Exp/Cntr=0.3,0.1

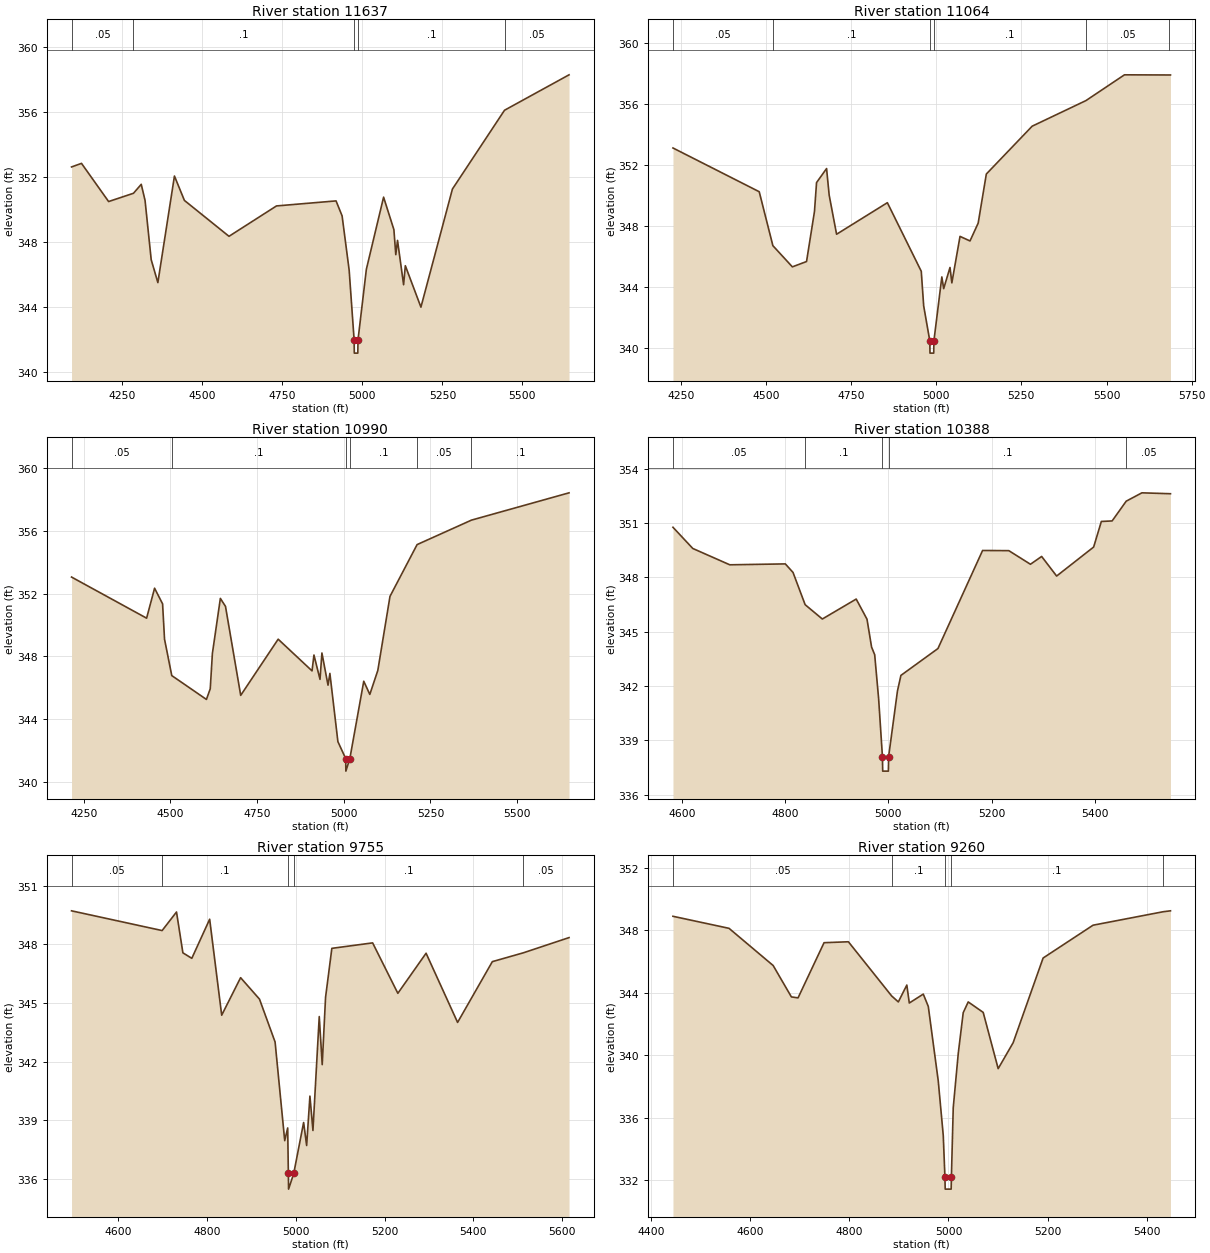
Type RM Length L Ch R = 1,11637,573,573,573
BEGIN DESCRIPTION:
Mapping XS e3963411
END DESCRIPTION:
XS GIS Cut Line= 3
      2058830.37     13428285.02      2059010.93     13427625.28
      2058691.49     13426816.26
#Sta/Elev= 30
  4091.8  352.63  4122.9  352.85  4207.6  350.50  4285.3  351.01  4309.5  351.56
  4321.4  350.57  4340.6  346.92  4361.4  345.51  4413.2  352.07  4444.3  350.57
  4583.6  348.36  4731.9  350.23  4917.9  350.54  4936.8  349.62  4958.9  346.27
  4974.4  341.97  4974.9  341.17  4985.9  341.17  4986.4  341.97  5012.6  346.33
  5066.4  350.77  5098.6  348.77  5104.5  347.23  5109.9  348.11  5128.9  345.38
  5134.3  346.55  5183.0  344.00  5281.4  351.27  5444.1  356.12  5645.6  358.30
#Mann=5,-1,0
  4091.8    0.05       0  4285.3     0.1       0  4974.4    0.07       0
  4986.4     0.1       0  5444.1    0.05       0
Bank Sta=4974.4,4986.4
Exp/Cntr=0.3,0.1

Type RM Length L Ch R = 1,11064,74,74,74
BEGIN DESCRIPTION:
Mapping XS 47ab1a85
END DESCRIPTION:
XS GIS Cut Line= 3
      2058889.40     13428389.16      2059243.57     13427528.06
      2059201.90     13427000.29
#Sta/Elev= 30
  4227.3  353.14  4480.5  350.27  4520.6  346.73  4577.8  345.34  4619.4  345.69
  4642.7  348.97  4648.8  350.87  4678.2  351.79  4685.9  350.04  4707.6  347.48
  4856.7  349.55  4956.2  345.05  4963.3  342.78  4981.3  340.48  4981.8  339.68
  4992.8  339.68  4993.3  340.48  5016.6  344.68  5022.0  343.91  5040.6  345.30
  5046.0  344.29  5070.0  347.34  5099.3  347.04  5123.3  348.21  5147.2  351.43
  5281.8  354.57  5439.7  356.25  5552.7  357.94  5683.0  357.93  5687.8  357.93
#Mann=6,-1,0
  4227.3    0.05       0  4520.6     0.1       0  4981.3    0.07       0
  4993.3     0.1       0  5439.7    0.05       0  5683.0     0.1       0
Bank Sta=4981.3,4993.3
Exp/Cntr=0.3,0.1

Type RM Length L Ch R = 1,10990,602,602,602
BEGIN DESCRIPTION:
Mapping XS d9b761c6
END DESCRIPTION:
XS GIS Cut Line= 3
      2058931.08     13428389.13      2059309.54     13427559.31
      2059368.47     13427039.28
#Sta/Elev= 30
  4214.6  353.06  4431.2  350.44  4454.2  352.35  4477.3  351.35  4482.9  349.10
  4503.8  346.78  4603.8  345.26  4614.8  345.94  4621.0  348.19  4644.0  351.70
  4658.8  351.19  4702.7  345.52  4810.8  349.10  4908.5  347.08  4914.0  348.09
  4931.5  346.54  4937.0  348.22  4954.6  346.17  4960.0  346.92  4983.1  342.57
  5005.6  341.49  5006.1  340.69  5017.6  341.49  5057.7  346.42  5075.2  345.58
  5098.3  347.11  5133.4  351.83  5211.6  355.13  5368.5  356.69  5650.0  358.43
#Mann=6,-1,0
  4214.6    0.05       0  4503.8     0.1       0  5005.6    0.07       0
  5017.6     0.1       0  5211.6    0.05       0  5368.5     0.1       0
Bank Sta=5005.6,5017.6
Exp/Cntr=0.3,0.1

Type RM Length L Ch R = 1,10388,633,633,633
BEGIN DESCRIPTION:
Mapping XS 7871718b
END DESCRIPTION:
XS GIS Cut Line= 2
      2059189.29     13428383.12      2059735.80     13427589.48
#Sta/Elev= 30
  4582.9  350.76  4621.3  349.59  4693.0  348.69  4800.5  348.74  4815.4  348.27
  4838.9  346.49  4872.2  345.70  4937.8  346.80  4958.7  345.69  4967.6  344.15
  4973.6  343.73  4981.3  341.28  4988.6  338.11  4989.1  337.31  5000.1  337.31
  5000.6  338.11  5017.7  341.73  5024.4  342.59  5096.1  344.07  5182.6  349.48
  5233.4  349.47  5275.3  348.72  5297.0  349.15  5326.0  348.07  5397.7  349.67
  5412.6  351.08  5433.5  351.11  5460.8  352.20  5491.2  352.66  5546.5  352.61
#Mann=5,-1,0
  4582.9    0.05       0  4838.9     0.1       0  4988.6    0.07       0
  5000.6     0.1       0  5460.8    0.05       0
Bank Sta=4988.6,5000.6
Exp/Cntr=0.3,0.1

Type RM Length L Ch R = 1,9755,495,495,495
BEGIN DESCRIPTION:
Mapping XS ee5ed221
END DESCRIPTION:
XS GIS Cut Line= 4
      2059295.63     13428446.03      2059610.32     13428411.30
      2060031.33     13428033.70      2059991.12     13427798.34
#Sta/Elev= 30
  4494.7  349.72  4698.8  348.71  4731.2  349.66  4745.6  347.57  4765.7  347.29
  4805.9  349.29  4833.0  344.38  4875.6  346.30  4918.2  345.20  4953.3  343.01
  4975.0  337.96  4981.7  338.61  4983.2  336.28  4983.7  335.48  4995.3  336.28
  5017.6  338.89  5024.4  337.71  5031.8  340.24  5038.6  338.48  5052.8  344.31
  5059.5  341.85  5067.0  345.29  5081.2  347.80  5173.1  348.08  5229.9  345.50
  5293.5  347.55  5364.5  344.01  5442.8  347.12  5512.4  347.57  5615.6  348.35
#Mann=5,-1,0
  4494.7    0.05       0  4698.8     0.1       0  4983.2    0.07       0
  4995.3     0.1       0  5512.4    0.05       0
Bank Sta=4983.2,4995.3
Exp/Cntr=0.3,0.1

Type RM Length L Ch R = 1,9260,252,252,252
BEGIN DESCRIPTION:
Mapping XS 5bba1f59
END DESCRIPTION:
XS GIS Cut Line= 4
      2060136.35     13428850.21      2060068.65     13428569.01
      2060141.57     13427944.01      2060138.62     13427859.43
#Sta/Elev= 30
  4444.5  348.90  4557.5  348.13  4646.5  345.75  4683.3  343.74  4696.7  343.68
  4749.1  347.21  4798.2  347.27  4885.5  343.80  4898.9  343.42  4916.0  344.50
  4921.0  343.35  4949.2  343.92  4959.3  343.13  4979.4  338.36  4989.5  334.86
  4992.8  332.24  4993.4  331.44  5005.4  331.44  5005.9  332.24  5009.6  336.65
  5019.7  340.12  5029.7  342.73  5039.8  343.42  5070.0  342.75  5100.2  339.15
  5130.4  340.81  5190.8  346.23  5291.5  348.33  5432.6  349.19  5447.6  349.25
#Mann=5,-1,0
  4444.5    0.05       0  4885.5     0.1       0  4992.8    0.07       0
  5005.9     0.1       0  5432.6    0.05       0
Bank Sta=4992.8,5005.9
Exp/Cntr=0.3,0.1

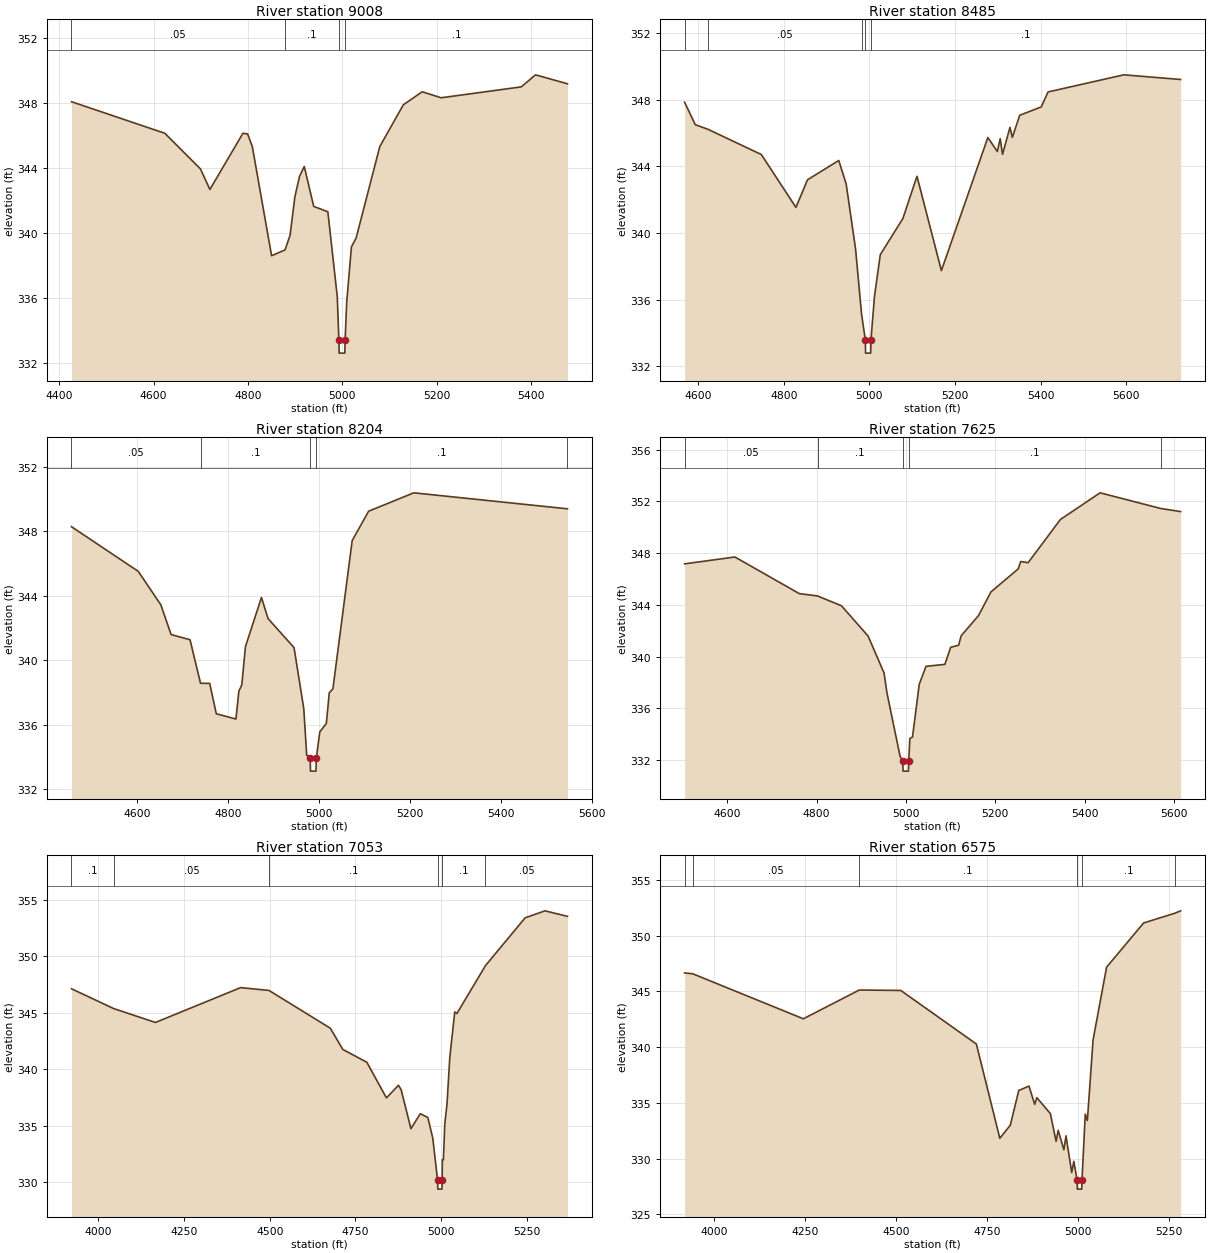
Type RM Length L Ch R = 1,9008,523,523,523
BEGIN DESCRIPTION:
Mapping XS 6f5eaf0c
END DESCRIPTION:
XS GIS Cut Line= 4
      2060485.30     13428834.61      2060323.86     13428662.76
      2060349.90     13427881.51      2060335.62     13427850.30
#Sta/Elev= 30
  4425.8  348.07  4623.8  346.13  4699.4  343.94  4719.4  342.68  4789.4  346.13
  4799.4  346.09  4809.4  345.30  4850.2  338.61  4878.8  338.97  4889.5  339.88
  4899.5  342.22  4909.5  343.49  4919.5  344.09  4939.5  341.64  4969.5  341.31
  4989.5  336.09  4992.9  333.43  4993.5  332.63  5005.5  332.63  5006.1  333.43
  5009.5  335.76  5019.5  339.15  5029.6  339.71  5079.6  345.31  5129.6  347.88
  5169.6  348.68  5209.7  348.31  5379.7  348.98  5409.8  349.72  5477.6  349.17
#Mann=4,-1,0
  4425.8    0.05       0  4878.8     0.1       0  4992.9    0.07       0
  5006.1     0.1       0
Bank Sta=4992.9,5006.1
Exp/Cntr=0.3,0.1

Type RM Length L Ch R = 1,8485,281,281,281
BEGIN DESCRIPTION:
Mapping XS d7be0e1c
END DESCRIPTION:
XS GIS Cut Line= 4
      2060745.73     13428891.96      2060792.61     13428589.84
      2060579.07     13428131.51      2060407.98     13427829.58
#Sta/Elev= 30
  4568.5  347.86  4593.5  346.51  4622.7  346.24  4747.6  344.72  4828.5  341.54
  4855.5  343.20  4928.5  344.36  4945.8  342.95  4967.8  339.03  4981.8  335.11
  4990.5  333.58  4991.1  332.78  5003.1  332.78  5003.7  333.58  5012.0  336.21
  5025.5  338.70  5078.2  340.87  5111.2  343.41  5168.2  337.74  5276.7  345.74
  5298.8  344.90  5305.5  345.67  5311.0  344.73  5328.3  346.35  5333.9  345.75
  5351.2  347.08  5401.4  347.58  5417.3  348.48  5594.2  349.51  5726.9  349.23
#Mann=5,-1,0
  4568.5     0.1       0  4622.7    0.05       0  4981.8     0.1       0
  4990.5    0.07       0  5003.7     0.1       0
Bank Sta=4990.5,5003.7
Exp/Cntr=0.3,0.1

Type RM Length L Ch R = 1,8204,579,579,579
BEGIN DESCRIPTION:
Raccoon Creek 10.0
END DESCRIPTION:
XS GIS Cut Line= 3
      2061168.93     13428657.94      2060825.00     13428225.00
      2060490.19     13427805.18
#Sta/Elev= 30
  4456.4  348.29  4603.2  345.52  4652.9  343.44  4675.3  341.60  4716.9  341.28
  4740.0  338.58  4760.2  338.57  4774.6  336.69  4817.8  336.36  4824.3  338.09
  4830.7  338.48  4838.7  340.85  4873.9  343.90  4888.4  342.59  4945.5  340.79
  4966.9  337.00  4973.3  334.12  4981.0  333.93  4981.6  333.13  4993.7  333.13
  4994.4  333.93  5002.1  335.56  5016.5  336.09  5022.9  337.99  5030.9  338.23
  5073.3  347.43  5109.4  349.25  5208.7  350.39  5545.7  349.40  5546.3  349.40
#Mann=5,-1,0
  4456.4    0.05       0  4740.0     0.1       0  4981.0    0.07       0
  4994.4     0.1       0  5545.7    0.05       0
Bank Sta=4981,4994.4
Exp/Cntr=0.3,0.1

Type RM Length L Ch R = 1,7625,572,572,572
BEGIN DESCRIPTION:
Raccoon Creek 9.0
END DESCRIPTION:
XS GIS Cut Line= 3
      2061599.48     13428477.38      2061099.90     13428152.34
      2060866.05     13427693.40
#Sta/Elev= 30
  4504.2  347.17  4616.9  347.70  4761.1  344.87  4801.9  344.69  4855.5  343.93
  4915.2  341.59  4951.0  338.73  4957.4  337.21  4986.8  332.30  4992.9  331.95
  4993.5  331.15  5005.6  331.15  5006.3  331.95  5008.7  333.66  5014.7  333.79
  5029.8  337.86  5045.0  339.25  5087.2  339.40  5100.2  340.72  5118.0  340.88
  5123.7  341.61  5162.5  343.17  5190.4  345.00  5251.5  346.78  5257.1  347.35
  5273.7  347.26  5346.0  350.60  5435.0  352.66  5570.7  351.45  5615.3  351.21
#Mann=5,-1,0
  4504.2    0.05       0  4801.9     0.1       0  4992.9    0.07       0
  5006.3     0.1       0  5570.7    0.05       0
Bank Sta=4992.9,5006.3
Exp/Cntr=0.3,0.1

Type RM Length L Ch R = 1,7053,478,478,478
BEGIN DESCRIPTION:
Raccoon Creek 8.0
END DESCRIPTION:
XS GIS Cut Line= 3
      2062023.13     13428602.41      2061325.00     13427775.00
      2061101.39     13427486.25
#Sta/Elev= 30
  3921.2  347.14  4044.5  345.38  4166.4  344.15  4415.0  347.24  4497.8  346.99
  4676.8  343.64  4713.2  341.76  4783.4  340.62  4840.6  337.46  4875.7  338.58
  4883.5  338.19  4912.1  334.73  4939.5  336.06  4961.5  335.72  4975.8  333.90
  4989.9  330.17  4990.6  329.37  5002.7  329.37  5003.3  330.17  5003.8  331.98
  5006.9  331.98  5011.0  335.18  5017.4  336.90  5025.5  341.02  5040.0  345.08
  5046.3  344.94  5129.7  349.19  5245.5  353.43  5303.5  354.05  5369.0  353.56
#Mann=6,-1,0
  3921.2     0.1       0  4044.5    0.05       0  4497.8     0.1       0
  4989.9    0.07       0  5003.3     0.1       0  5129.7    0.05       0
Bank Sta=4989.9,5003.3
Exp/Cntr=0.3,0.1

Type RM Length L Ch R = 1,6575,639,639,639
BEGIN DESCRIPTION:
Raccoon Creek 7.0
END DESCRIPTION:
XS GIS Cut Line= 2
      2062217.55     13428456.55      2061529.13     13427281.57
#Sta/Elev= 30
  3919.8  346.65  3941.8  346.58  4245.8  342.54  4399.3  345.12  4513.4  345.08
  4720.8  340.28  4785.2  331.83  4814.0  333.00  4837.2  336.11  4865.3  336.51
  4881.0  334.87  4886.8  335.47  4924.0  334.04  4939.7  331.55  4945.4  332.54
  4961.1  330.80  4966.9  332.05  4982.6  328.76  4988.4  329.76  4997.4  328.07
  4998.0  327.27  5010.1  327.27  5010.8  328.07  5019.8  334.00  5025.6  333.42
  5041.3  340.66  5078.4  347.17  5180.0  351.13  5266.2  352.01  5281.6  352.22
#Mann=6,-1,0
  3919.8     0.1       0  3941.8    0.05       0  4399.3     0.1       0
  4997.4    0.07       0  5010.8     0.1       0  5266.2    0.05       0
Bank Sta=4997.4,5010.8
Exp/Cntr=0.3,0.1

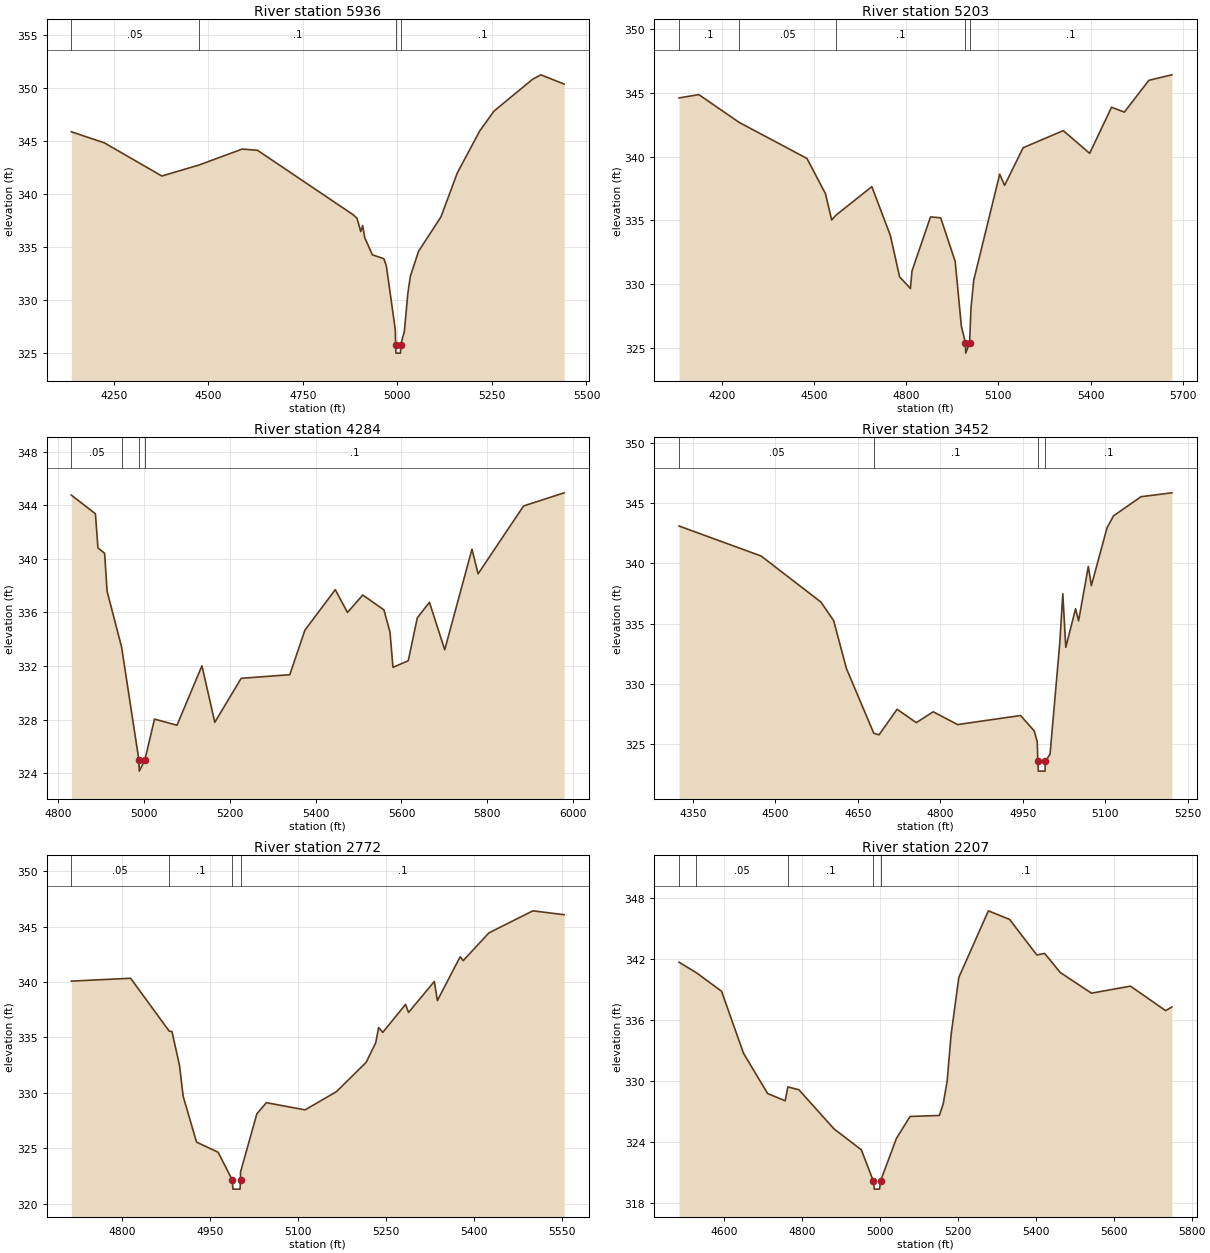
Type RM Length L Ch R = 1,5936,733,733,733
BEGIN DESCRIPTION:
Raccoon Creek 6.0
END DESCRIPTION:
XS GIS Cut Line= 3
      2062259.21     13428331.52      2062125.00     13427475.00
      2061910.60     13427095.09
#Sta/Elev= 30
  4137.7  345.86  4225.3  344.81  4377.1  341.69  4475.8  342.73  4589.8  344.23
  4630.2  344.11  4883.2  338.04  4893.3  337.71  4903.1  336.46  4908.1  337.02
  4913.6  335.89  4933.8  334.27  4964.2  333.90  4970.8  333.24  4994.5  327.20
  4995.4  325.81  4996.1  325.01  5008.2  325.01  5008.8  325.81  5018.4  327.05
  5027.6  330.63  5034.3  332.25  5055.9  334.60  5115.2  337.84  5158.5  341.99
  5217.7  345.93  5255.3  347.80  5357.8  350.81  5379.5  351.22  5440.9  350.35
#Mann=4,-1,0
  4137.7    0.05       0  4475.8     0.1       0  4995.4    0.07       0
  5008.8     0.1       0
Bank Sta=4995.4,5008.8
Exp/Cntr=0.3,0.1

Type RM Length L Ch R = 1,5203,919,919,919
BEGIN DESCRIPTION:
Raccoon Creek 5.0
END DESCRIPTION:
XS GIS Cut Line= 3
      2062688.03     13428419.18      2062570.49     13427290.45
      2062295.99     13426909.48
#Sta/Elev= 30
  4060.3  344.59  4124.8  344.85  4255.6  342.68  4476.7  339.85  4537.0  337.09
  4557.2  335.03  4570.8  335.40  4687.9  337.64  4748.2  333.82  4778.3  330.58
  4813.6  329.66  4818.6  331.03  4878.9  335.27  4912.1  335.20  4959.3  331.78
  4979.4  326.71  4992.8  325.40  4993.5  324.60  5006.2  325.40  5010.7  328.13
  5019.6  330.30  5104.2  338.62  5120.2  337.74  5180.5  340.69  5311.2  342.03
  5397.1  340.25  5468.3  343.86  5510.0  343.48  5589.8  345.97  5664.7  346.40
#Mann=5,-1,0
  4060.3     0.1       0  4255.6    0.05       0  4570.8     0.1       0
  4992.8    0.07       0  5006.2     0.1       0
Bank Sta=4992.8,5006.2
Exp/Cntr=0.3,0.1

Type RM Length L Ch R = 1,4284,832,832,832
BEGIN DESCRIPTION:
Raccoon Creek 4.0
END DESCRIPTION:
XS GIS Cut Line= 3
      2063335.58     13427580.67      2063049.14     13427407.07
      2062493.10     13426813.46
#Sta/Elev= 30
  4830.7  344.75  4886.9  343.36  4892.8  340.81  4908.3  340.41  4914.1  337.58
  4947.9  333.42  4988.3  324.97  4989.0  324.17  5001.8  324.97  5024.6  328.05
  5076.9  327.59  5135.1  332.02  5165.1  327.81  5226.5  331.09  5339.8  331.36
  5375.0  334.68  5445.8  337.70  5474.2  336.00  5509.8  337.30  5559.2  336.19
  5573.3  334.53  5580.2  331.91  5615.8  332.40  5636.8  335.59  5665.2  336.76
  5700.8  333.22  5764.3  340.72  5778.5  338.88  5884.5  343.94  5979.0  344.92
#Mann=4,-1,0
  4830.7    0.05       0  4947.9     0.1       0  4988.3    0.07       0
  5001.8     0.1       0
Bank Sta=4988.3,5001.8
Exp/Cntr=0.3,0.1

Type RM Length L Ch R = 1,3452,680,680,680
BEGIN DESCRIPTION:
Mapping XS a17a62d8
END DESCRIPTION:
XS GIS Cut Line= 4
      2063523.71     13427111.93      2063478.13     13426910.07
      2062952.95     13426675.69      2062838.98     13426671.39
#Sta/Elev= 30
  4325.1  343.10  4474.4  340.61  4583.0  336.80  4606.2  335.26  4629.5  331.28
  4679.2  325.92  4688.8  325.79  4721.6  327.91  4756.5  326.80  4787.3  327.70
  4831.6  326.64  4946.1  327.39  4971.0  326.11  4976.4  325.21  4977.5  323.58
  4978.3  322.78  4990.5  322.78  4991.3  323.58  4999.7  324.19  5017.3  333.35
  5022.9  337.49  5028.3  333.04  5046.1  336.24  5051.6  335.24  5069.3  339.75
  5074.8  338.16  5103.3  342.95  5115.1  343.94  5165.1  345.53  5221.2  345.85
#Mann=4,-1,0
  4325.1    0.05       0  4679.2     0.1       0  4977.5    0.07       0
  4991.3     0.1       0
Bank Sta=4977.5,4991.3
Exp/Cntr=0.3,0.1

Type RM Length L Ch R = 1,2772,565,565,565
BEGIN DESCRIPTION:
Mapping XS 956ea32c
END DESCRIPTION:
XS GIS Cut Line= 4
      2063521.53     13426756.01      2063523.70     13426586.72
      2063211.20     13426419.62      2062903.04     13426486.89
#Sta/Elev= 30
  4714.0  340.09  4815.0  340.35  4880.6  335.58  4885.4  335.53  4898.2  332.49
  4904.5  329.68  4927.2  325.55  4964.0  324.63  4988.3  322.10  4989.1  321.30
  5001.3  321.30  5002.1  322.10  5002.2  322.86  5029.9  328.10  5046.1  329.11
  5112.0  328.46  5165.3  330.10  5216.0  332.75  5232.3  334.52  5237.3  335.90
  5244.3  335.46  5283.1  337.99  5288.2  337.26  5332.1  340.06  5337.3  338.33
  5376.0  342.29  5381.2  341.94  5425.1  344.45  5499.9  346.44  5553.1  346.09
#Mann=4,-1,0
  4714.0    0.05       0  4880.6     0.1       0  4988.3    0.07       0
  5002.1     0.1       0
Bank Sta=4988.3,5002.1
Exp/Cntr=0.3,0.1

Type RM Length L Ch R = 1,2207,375,375,375
BEGIN DESCRIPTION:
Mapping XS 00a5a465
END DESCRIPTION:
XS GIS Cut Line= 3
      2063939.78     13426763.86      2063814.77     13426506.90
      2063863.32     13425528.86
#Sta/Elev= 30
  4484.2  341.67  4528.6  340.64  4593.3  338.82  4649.7  332.73  4711.6  328.78
  4756.7  328.07  4763.5  329.43  4791.9  329.15  4882.0  325.31  4952.1  323.26
  4982.9  320.20  4985.4  319.40  4998.9  319.40  5001.4  320.20  5042.2  324.38
  5077.2  326.53  5152.3  326.63  5162.3  327.77  5172.4  330.00  5182.4  334.51
  5202.4  340.18  5278.2  346.71  5332.5  345.87  5402.6  342.38  5422.7  342.53
  5462.7  340.66  5542.8  338.63  5642.9  339.32  5733.0  336.92  5749.2  337.27
#Mann=5,-1,0
  4484.2     0.1       0  4528.6    0.05       0  4763.5     0.1       0
  4982.9    0.07       0  5001.4     0.1       0
Bank Sta=4982.9,5001.4
Exp/Cntr=0.3,0.1

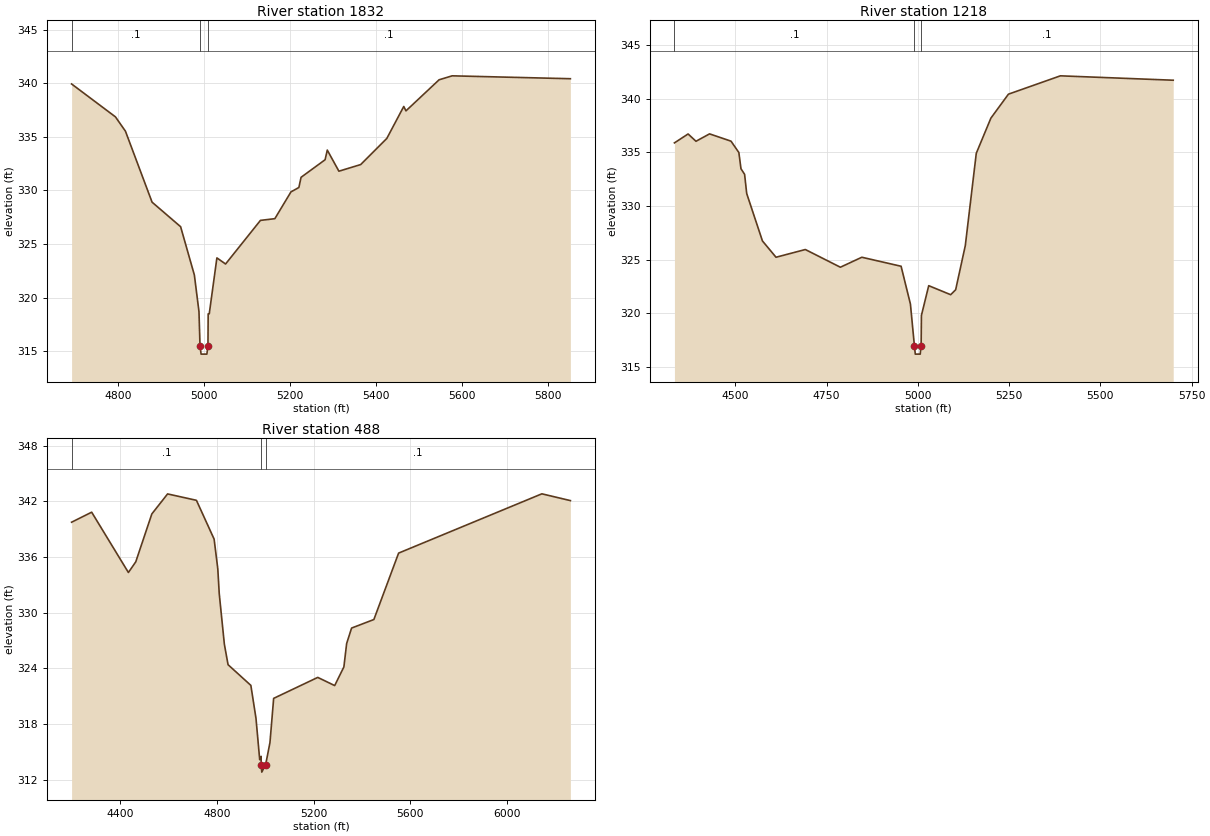
Type RM Length L Ch R = 1,1832,614,614,614
BEGIN DESCRIPTION:
Raccoon Creek 3.0
END DESCRIPTION:
XS GIS Cut Line= 3
      2064012.68     13426722.18      2064125.00     13426425.00
      2064262.68     13425593.72
#Sta/Elev= 30
  4692.5  339.94  4794.5  336.87  4817.8  335.53  4879.7  328.91  4946.1  326.62
  4978.1  322.11  4988.8  318.70  4991.2  315.53  4993.7  314.73  5007.2  314.73
  5009.7  315.53  5010.2  318.49  5012.7  318.49  5030.5  323.71  5050.7  323.14
  5131.8  327.21  5165.3  327.37  5202.8  329.87  5221.2  330.28  5226.3  331.23
  5282.2  332.87  5287.3  333.77  5314.3  331.80  5365.0  332.42  5425.8  334.86
  5465.2  337.84  5470.3  337.43  5547.4  340.33  5577.8  340.70  5852.8  340.43
#Mann=3,-1,0
  4692.5     0.1       0  4991.2    0.07       0  5009.7     0.1       0
Bank Sta=4991.2,5009.7
Exp/Cntr=0.3,0.1

Type RM Length L Ch R = 1,1218,730,730,730
BEGIN DESCRIPTION:
Raccoon Creek 2.0
END DESCRIPTION:
XS GIS Cut Line= 3
      2064208.02     13426769.04      2064663.73     13426504.29
      2064720.15     13425666.62
#Sta/Elev= 30
  4332.9  335.89  4370.3  336.72  4391.9  336.04  4429.1  336.73  4487.9  336.05
  4509.4  334.99  4515.2  333.48  4525.1  332.96  4530.9  331.17  4574.0  326.75
  4611.2  325.23  4691.5  325.95  4787.5  324.30  4846.3  325.23  4953.9  324.39
  4979.5  320.86  4990.3  317.00  4992.8  316.20  5006.3  316.20  5008.8  317.00
  5009.6  319.81  5029.6  322.58  5089.7  321.74  5103.4  322.20  5129.8  326.31
  5159.9  334.92  5200.0  338.20  5248.0  340.43  5390.4  342.14  5699.5  341.73
#Mann=3,-1,0
  4332.9     0.1       0  4990.3    0.07       0  5008.8     0.1       0
Bank Sta=4990.3,5008.8
Exp/Cntr=0.3,0.1

Type RM Length L Ch R = 1,488,0,0,0
BEGIN DESCRIPTION:
Raccoon Creek 1.0
END DESCRIPTION:
XS GIS Cut Line= 4
      2064273.11     13426834.16      2064681.09     13426903.60
      2065210.60     13426573.74      2064984.90     13425571.13
#Sta/Elev= 30
  4197.7  339.75  4280.8  340.83  4432.9  334.33  4463.4  335.48  4529.9  340.64
  4595.2  342.80  4714.6  342.11  4787.8  337.93  4803.1  334.72  4809.0  332.06
  4830.3  326.59  4845.6  324.39  4940.0  322.16  4961.2  318.61  4976.6  314.15
  4982.5  314.51  4982.7  313.61  4985.2  312.81  5001.2  313.61  5019.1  316.00
  5034.4  320.76  5217.0  323.02  5287.1  322.14  5325.2  324.15  5336.6  326.67
  5357.1  328.34  5449.4  329.26  5551.8  336.42  6145.0  342.81  6263.1  342.08
#Mann=3,-1,0
  4197.7     0.1       0  4982.7    0.07       0  5001.2     0.1       0
Bank Sta=4982.7,5001.2
Exp/Cntr=0.3,0.1

Chan Stop Cuts=-1