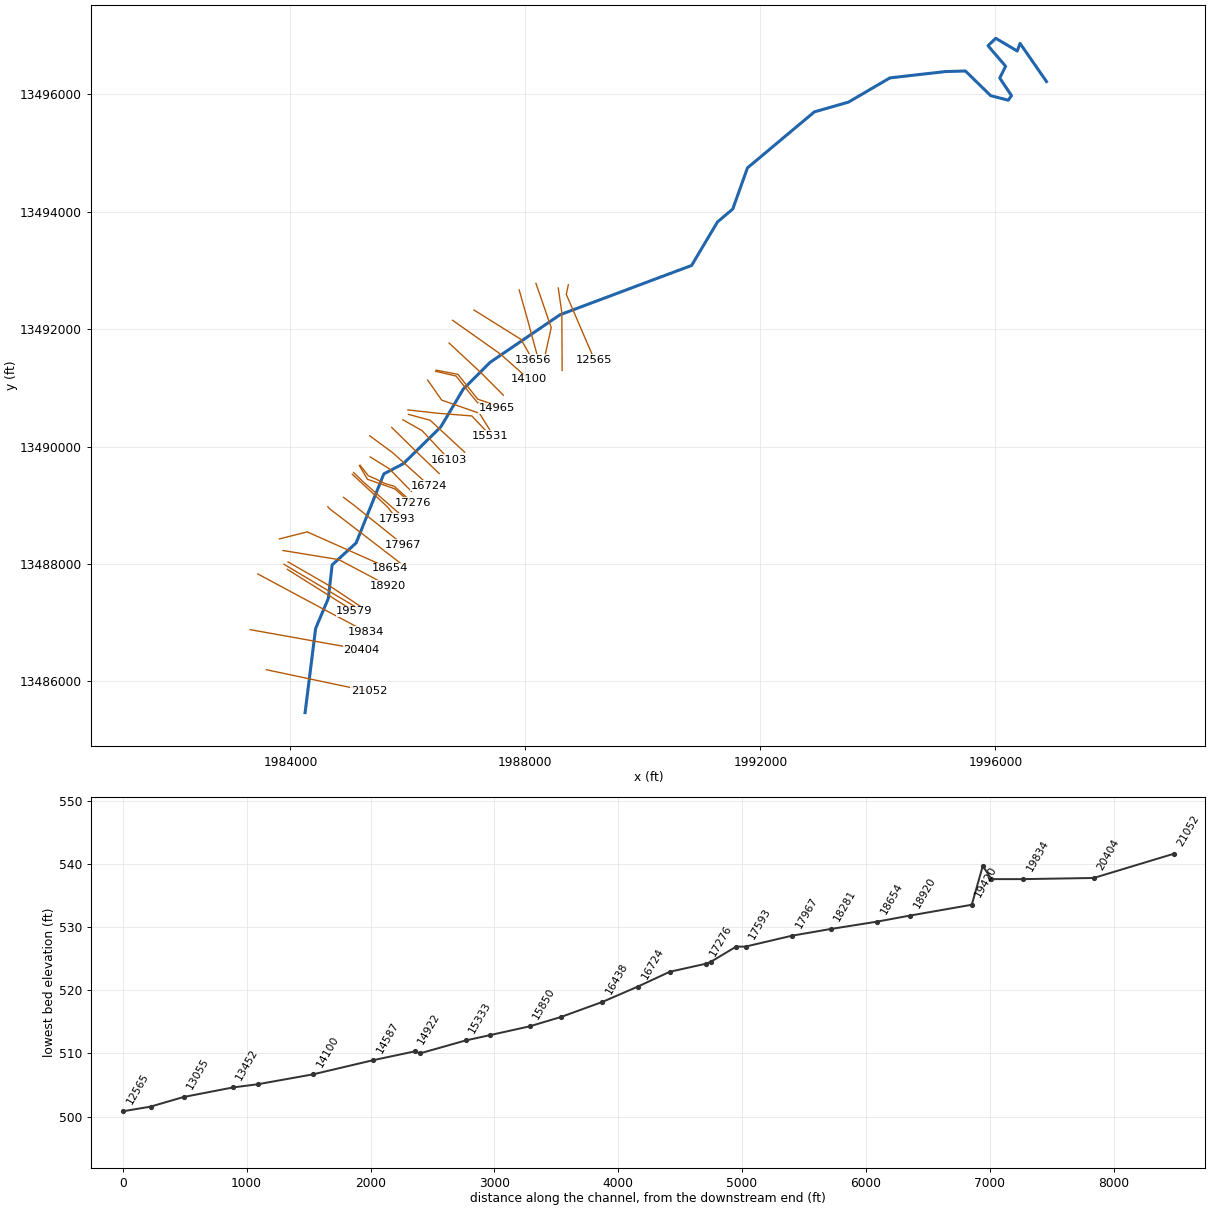
--- UNT 001 in RCW.prj (project) ---

Proj Title=UNT 001 in RCW Base Level Engineering
Current Plan=p01
Default Exp/Contr=0.3,0.1
English Units
Geom File=g01
Flow File=f01
Plan File=p01
BEGIN DESCRIPTION:
UNT 001 in RCW
END DESCRIPTION:

--- UNT 001 in RCW.p01 (plan) ---

Plan Title=Multiple Run
Short Identifier=Multiple
Geom File=g01
Flow File=f01
Subcritical Flow
K Sum by GR= 0
Std Step Tol= 0.01
Critical Tol= 0.01
Num of Std Step Trials= 20
Max Error Tol= 0.3
Flow Tol Ratio= 0.001
Split Flow NTrial= 30
Split Flow Tol= 0.02
Split Flow Ratio= 0.02
Log Output Level= 0
Friction Slope Method= 1
Unsteady Friction Slope Method= 2
Unsteady Bridges Friction Slope Method= 1
Parabolic Critical Depth
Global Vel Dist=  1 , 1 , 1
Global Log Level= 0
CheckData=True
Encroach Param= -1, 0, 0, 0
BEGIN DESCRIPTION:
Multiple Run
END DESCRIPTION:

--- UNT 001 in RCW.f01 (steady flow) ---

Flow Title=Multiple
Number of Profiles=7
Profile Names=10-year,25-year,50-year,1pct_min,100-year,1pct_plu,500-year
River Rch & RM= UNT 001 in RCW,Reach-1,21052
     168     228     277     168     336     670     500
River Rch & RM= UNT 001 in RCW,Reach-1,18920
     263     366     452     278     555    1107     849
River Rch & RM= UNT 001 in RCW,Reach-1,10014
     341     480     596     369     736    1469    1141
River Rch & RM= UNT 001 in RCW,Reach-1,6369
     336     471     583     360     717    1432    1103
Boundary for River Rch & Prof#=UNT 001 in RCW,Reach-1,1
Up Type=0
Dn Type=3
Dn Slope=0.005
Boundary for River Rch & Prof#=UNT 001 in RCW,Reach-1,2
Up Type=0
Dn Type=3
Dn Slope=0.005
Boundary for River Rch & Prof#=UNT 001 in RCW,Reach-1,3
Up Type=0
Dn Type=3
Dn Slope=0.005
Boundary for River Rch & Prof#=UNT 001 in RCW,Reach-1,4
Up Type=0
Dn Type=3
Dn Slope=0.005
Boundary for River Rch & Prof#=UNT 001 in RCW,Reach-1,5
Up Type=0
Dn Type=3
Dn Slope=0.005
Boundary for River Rch & Prof#=UNT 001 in RCW,Reach-1,6
Up Type=0
Dn Type=3
Dn Slope=0.005
Boundary for River Rch & Prof#=UNT 001 in RCW,Reach-1,7
Up Type=0
Dn Type=3
Dn Slope=0.005

--- UNT 001 in RCW.g01 (geometry) ---

Geom Title=Existing Conditions

River Reach=UNT 001 in RCW,Reach-1
Reach XY= 30
      1984250.73     13485469.78      1984429.78     13486902.71
      1984645.82     13487414.22      1984710.80     13487984.54
      1985119.78     13488359.42      1985590.80     13489534.54
      1985923.47     13489708.12      1986560.80     13490334.54
      1986940.80     13490974.54      1987400.80     13491434.54
      1988590.80     13492244.54      1990829.55     13493083.29
      1991270.80     13493824.54      1991530.80     13494044.54
      1991780.80     13494744.54      1992920.18     13495698.66
      1993500.80     13495864.54      1994205.99     13496277.00
      1995150.80     13496384.54      1995490.80     13496394.54
      1995920.80     13495974.54      1996220.16     13495896.86
      1996275.00     13495975.00      1996075.00     13496275.00
      1996175.00     13496475.00      1995875.00     13496825.00
      1996007.74     13496950.94      1996372.33     13496734.79
      1996420.80     13496864.54      1996870.80     13496214.54

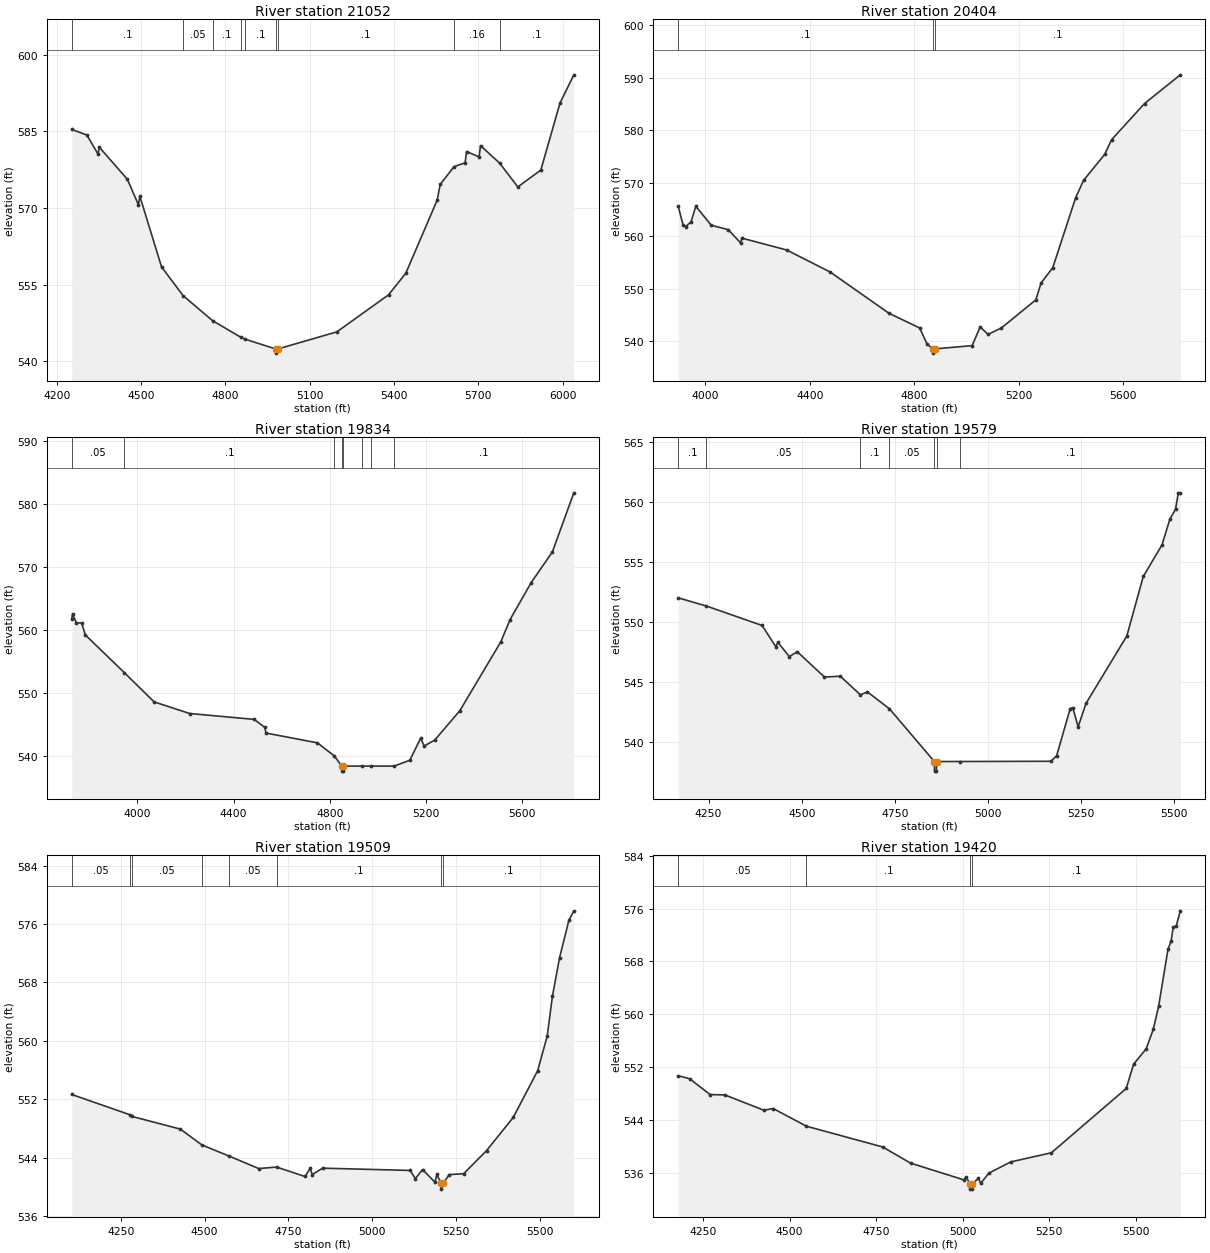
Type RM Length L Ch R = 1,21052,648,648,648
BEGIN DESCRIPTION:
Mapping XS 5eb77f2f
END DESCRIPTION:
XS GIS Cut Line= 2
      1983592.64     13486200.05      1985340.04     13485830.25
#Sta/Elev= 30
  4253.8  585.35  4307.4  584.27  4346.9  580.57  4352.0  581.86  4451.4  575.63
  4490.9  570.63  4496.0  572.31  4573.1  558.49  4649.9  552.87  4754.5  547.98
  4855.6  544.72  4871.6  544.34  4979.8  542.43  4980.3  541.63  4985.8  542.43
  5196.6  545.78  5380.6  553.02  5441.9  557.23  5553.7  571.54  5564.6  574.61
  5613.6  578.08  5653.1  578.83  5658.2  581.03  5702.8  579.99  5707.9  582.18
  5776.2  578.76  5840.5  574.12  5922.3  577.40  5990.8  590.54  6039.9  596.03
#Mann=9,-1,0
  4253.8     0.1       0  4649.9    0.05       0  4754.5     0.1       0
  4855.6    0.05       0  4871.6     0.1       0  4979.8    0.07       0
  4985.8     0.1       0  5613.6    0.16       0  5776.2     0.1       0
Bank Sta=4979.8,4985.8
Exp/Cntr=0.3,0.1

Type RM Length L Ch R = 1,20404,570,570,570
BEGIN DESCRIPTION:
Mapping XS 2cfe2e91
END DESCRIPTION:
XS GIS Cut Line= 2
      1983316.59     13486882.34      1985209.86     13486543.79
#Sta/Elev= 30
  3896.4  565.59  3915.1  562.05  3925.3  561.78  3945.6  562.67  3963.7  565.62
  4022.5  562.03  4087.8  561.19  4135.2  558.68  4140.3  559.58  4311.9  557.33
  4478.3  553.16  4703.7  545.34  4821.5  542.55  4849.7  539.47  4872.3  538.59
  4872.8  537.79  4878.3  538.59  5022.4  539.21  5052.9  542.76  5083.3  541.34
  5134.1  542.55  5266.2  547.88  5286.5  551.10  5331.1  553.98  5418.6  567.21
  5449.0  570.52  5530.3  575.46  5556.4  578.23  5682.7  585.08  5819.7  590.52
#Mann=3,-1,0
  3896.4     0.1       0  4872.3    0.07       0  4878.3     0.1       0
Bank Sta=4872.3,4878.3
Exp/Cntr=0.3,0.1

Type RM Length L Ch R = 1,19834,255,255,255
BEGIN DESCRIPTION:
UNT 001 in RCW 36.0
END DESCRIPTION:
XS GIS Cut Line= 3
      1983445.54     13487830.69      1984575.00     13487225.00
      1985287.97     13486847.62
#Sta/Elev= 30
  3726.8  561.82  3730.1  562.51  3746.3  561.15  3768.2  561.11  3782.9  559.23
  3945.2  553.24  4069.5  548.59  4217.4  546.75  4485.4  545.82  4529.2  544.57
  4534.9  543.65  4748.5  542.10  4819.4  540.00  4849.5  538.41  4850.0  537.61
  4855.0  537.61  4855.5  538.41  4935.8  538.41  4972.3  538.41  5067.8  538.41
  5132.9  539.34  5178.1  542.84  5192.6  541.59  5236.6  542.54  5341.0  547.20
  5511.3  558.12  5549.7  561.64  5637.7  567.52  5725.7  572.38  5815.1  581.76
#Mann=8,-1,0
  3726.8    0.05       0  3945.2     0.1       0  4819.4    0.05       0
  4849.5    0.03       0  4855.5    0.05       0  4935.8     0.1       0
  4972.3    0.05       0  5067.8     0.1       0
Bank Sta=4849.5,4855.5
Exp/Cntr=0.3,0.1

Type RM Length L Ch R = 1,19579,70,70,70
BEGIN DESCRIPTION:
Mapping XS 2d1ee6db
END DESCRIPTION:
XS GIS Cut Line= 2
      1983948.53     13487909.25      1985089.18     13487192.22
#Sta/Elev= 30
  4168.7  552.03  4244.3  551.35  4393.8  549.73  4430.3  547.97  4436.2  548.33
  4466.8  547.14  4488.0  547.55  4561.1  545.44  4603.5  545.51  4657.6  543.96
  4676.5  544.20  4735.4  542.80  4856.0  538.41  4856.5  537.61  4861.5  537.61
  4862.0  538.41  4926.0  538.41  5168.8  538.43  5184.1  538.89  5220.6  542.82
  5227.6  542.87  5241.8  541.30  5263.0  543.25  5372.5  548.86  5416.6  553.81
  5466.8  556.43  5488.0  558.58  5503.3  559.41  5510.6  560.77  5516.0  560.77
#Mann=7,-1,0
  4168.7     0.1       0  4244.3    0.05       0  4657.6     0.1       0
  4735.4    0.05       0  4856.0    0.07       0  4862.0    0.05       0
  4926.0     0.1       0
Bank Sta=4856,4862
Exp/Cntr=0.3,0.1

Type RM Length L Ch R = 1,19509,89,89,89
BEGIN DESCRIPTION:
Mapping XS 5af91991
END DESCRIPTION:
XS GIS Cut Line= 2
      1983891.21     13487995.38      1985177.75     13487229.01
#Sta/Elev= 30
  4104.0  552.66  4276.4  549.90  4284.0  549.65  4427.8  547.92  4492.1  545.75
  4573.5  544.22  4661.5  542.52  4714.9  542.72  4799.7  541.43  4815.3  542.56
  4821.1  541.69  4852.3  542.57  5113.2  542.26  5128.7  541.14  5150.2  542.38
  5187.2  540.65  5193.0  541.71  5205.6  540.50  5206.1  539.70  5211.6  540.50
  5230.0  541.69  5272.8  541.81  5341.0  544.97  5420.8  549.52  5493.5  555.91
  5522.0  560.64  5537.6  566.11  5559.0  571.41  5586.7  576.51  5601.5  577.81
#Mann=8,-1,0
  4104.0    0.05       0  4276.4     0.1       0  4284.0    0.05       0
  4492.1     0.1       0  4573.5    0.05       0  4714.9     0.1       0
  5205.6    0.07       0  5211.6     0.1       0
Bank Sta=5205.6,5211.6
Exp/Cntr=0.3,0.1

Type RM Length L Ch R = 1,19420,500,500,500
BEGIN DESCRIPTION:
UNT 001 in RCW 35.0
END DESCRIPTION:
XS GIS Cut Line= 3
      1983960.64     13488036.01      1984662.07     13487631.47
      1985195.10     13487277.28
#Sta/Elev= 30
  4178.5  550.71  4211.5  550.25  4270.4  547.86  4313.5  547.80  4425.5  545.49
  4452.8  545.74  4548.7  543.07  4768.7  539.93  4849.2  537.49  5003.3  534.95
  5009.4  535.39  5021.4  534.35  5021.9  533.55  5026.9  533.55  5027.4  534.35
  5045.4  535.18  5051.8  534.43  5075.5  535.97  5138.6  537.67  5255.9  539.05
  5472.0  548.78  5493.4  552.46  5529.5  554.77  5550.5  557.78  5565.6  561.22
  5592.6  569.84  5601.6  571.08  5607.6  573.14  5616.1  573.32  5628.2  575.66
#Mann=4,-1,0
  4178.5    0.05       0  4548.7     0.1       0  5021.4    0.07       0
  5027.4     0.1       0
Bank Sta=5021.4,5027.4
Exp/Cntr=0.3,0.1

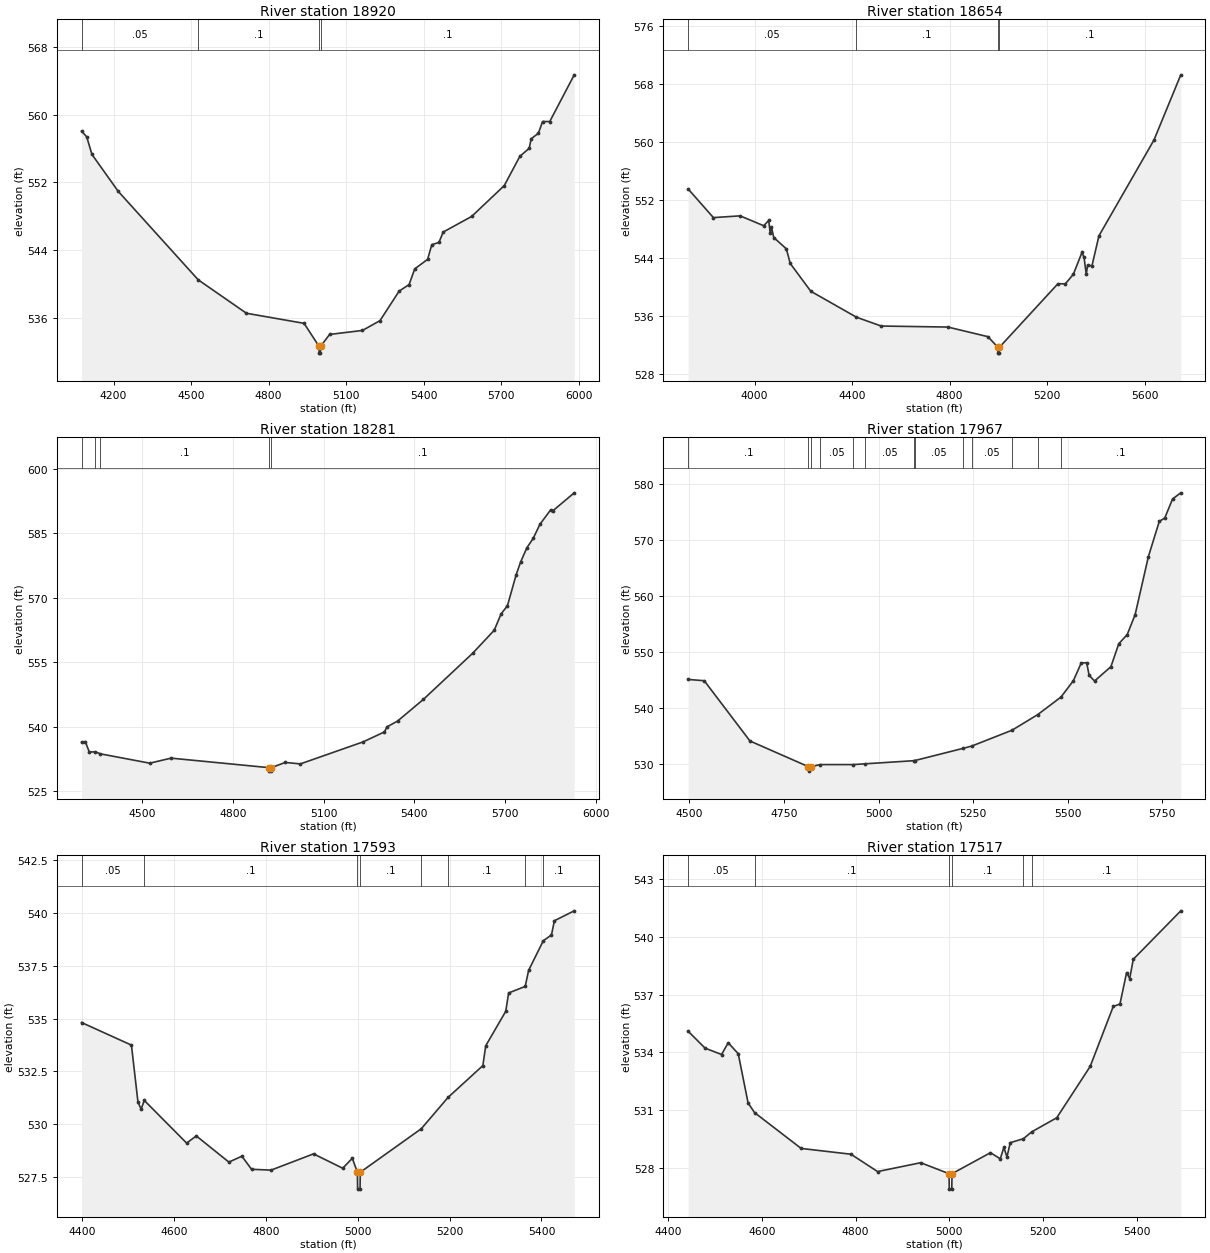
Type RM Length L Ch R = 1,18920,266,266,266
BEGIN DESCRIPTION:
UNT 001 in RCW 34.0
END DESCRIPTION:
XS GIS Cut Line= 3
      1983875.21     13488229.99      1984825.00     13488075.00
      1985659.07     13487633.21
#Sta/Elev= 30
  4076.3  558.07  4096.3  557.39  4116.6  555.31  4217.9  550.96  4527.8  540.49
  4714.4  536.54  4937.3  535.35  4995.1  532.63  4995.6  531.83  5000.6  531.83
  5001.1  532.63  5036.1  534.04  5163.1  534.51  5231.0  535.67  5305.1  539.16
  5343.5  539.93  5365.5  541.79  5415.1  542.91  5431.5  544.65  5459.1  544.91
  5475.5  546.14  5585.5  547.98  5711.8  551.63  5772.1  555.09  5808.2  556.03
  5816.1  557.17  5843.8  557.81  5860.1  559.20  5887.8  559.20  5982.5  564.72
#Mann=4,-1,0
  4076.3    0.05       0  4527.8     0.1       0  4995.1    0.07       0
  5001.1     0.1       0
Bank Sta=4995.1,5001.1
Exp/Cntr=0.3,0.1

Type RM Length L Ch R = 1,18654,373,373,373
BEGIN DESCRIPTION:
UNT 001 in RCW 33.0
END DESCRIPTION:
XS GIS Cut Line= 3
      1983814.49     13488427.47      1984287.56     13488546.83
      1985687.34     13487923.98
#Sta/Elev= 30
  3727.7  553.54  3831.4  549.58  3941.0  549.82  4037.6  548.46  4058.3  549.18
  4064.2  547.45  4069.4  548.27  4078.9  546.83  4130.5  545.27  4146.4  543.25
  4230.8  539.41  4417.9  535.83  4519.3  534.61  4792.8  534.47  4957.1  533.14
  4997.9  531.67  4998.4  530.87  5003.4  530.87  5003.9  531.67  5244.0  540.45
  5274.5  540.44  5307.3  541.76  5342.5  544.77  5351.1  544.08  5360.2  541.76
  5365.7  543.02  5383.5  542.92  5412.2  547.07  5637.8  560.29  5747.7  569.29
#Mann=4,-1,0
  3727.7    0.05       0  4417.9     0.1       0  4997.9    0.07       0
  5003.9     0.1       0
Bank Sta=4997.9,5003.9
Exp/Cntr=0.3,0.1

Type RM Length L Ch R = 1,18281,314,314,314
BEGIN DESCRIPTION:
UNT 001 in RCW 32.0
END DESCRIPTION:
XS GIS Cut Line= 3
      1984638.26     13488974.77      1984663.67     13488944.18
      1985924.96     13487975.03
#Sta/Elev= 30
  4299.1  536.41  4311.4  536.59  4324.8  534.15  4344.6  534.20  4361.6  533.73
  4524.8  531.56  4595.5  532.73  4920.5  530.51  4921.0  529.71  4926.1  529.71
  4926.6  530.51  4973.4  531.73  5023.2  531.39  5230.8  536.51  5301.5  538.83
  5309.7  540.00  5345.0  541.36  5430.2  546.39  5594.2  557.18  5664.9  562.49
  5687.6  566.30  5708.4  568.16  5737.4  575.41  5752.0  578.33  5772.8  581.67
  5793.6  583.83  5816.0  587.12  5851.6  590.49  5857.9  590.21  5929.5  594.44
#Mann=5,-1,0
  4299.1    0.08       0  4344.6    0.05       0  4361.6     0.1       0
  4920.5    0.07       0  4926.6     0.1       0
Bank Sta=4920.5,4926.6
Exp/Cntr=0.3,0.1

Type RM Length L Ch R = 1,17967,374,374,374
BEGIN DESCRIPTION:
UNT 001 in RCW 31.0
END DESCRIPTION:
XS GIS Cut Line= 3
      1984904.31     13489134.51      1985083.14     13489000.82
      1985924.96     13488325.03
#Sta/Elev= 30
  4496.5  545.04  4539.2  544.81  4660.1  534.03  4814.6  529.44  4815.1  528.64
  4820.7  529.44  4846.1  529.81  4933.2  529.81  4964.8  529.95  5094.1  530.51
  5095.2  530.52  5223.5  532.71  5246.7  533.13  5352.8  535.95  5420.6  538.73
  5482.7  541.90  5515.3  544.82  5536.1  547.99  5550.5  548.03  5556.9  545.78
  5571.3  544.76  5614.5  547.32  5635.3  551.42  5657.7  553.07  5678.5  556.61
  5713.7  567.02  5742.5  573.32  5756.9  573.91  5777.7  577.33  5799.3  578.42
#Mann=13,-1,0
  4496.5     0.1       0  4814.6    0.03       0  4820.7     0.1       0
  4846.1    0.05       0  4933.2     0.1       0  4964.8    0.05       0
  5094.1     0.1       0  5095.2    0.05       0  5223.5     0.1       0
  5246.7    0.05       0  5352.8     0.1       0  5420.6    0.05       0
  5482.7     0.1       0
Bank Sta=4814.6,4820.7
Exp/Cntr=0.3,0.1

Type RM Length L Ch R = 1,17593,76,76,76
BEGIN DESCRIPTION:
Mapping XS 60fed9e8
END DESCRIPTION:
XS GIS Cut Line= 3
      1985054.49     13489527.73      1985653.45     13488971.74
      1985809.65     13488769.97
#Sta/Elev= 30
  4398.9  534.81  4507.5  533.74  4521.7  531.04  4528.5  530.71  4535.5  531.12
  4627.7  529.10  4648.7  529.44  4719.6  528.20  4747.9  528.48  4768.9  527.86
  4811.4  527.82  4903.8  528.59  4967.3  527.91  4988.3  528.38  4999.3  527.72
  4999.8  526.92  5005.1  526.92  5005.6  527.72  5138.4  529.78  5196.5  531.26
  5272.4  532.77  5278.7  533.71  5322.2  535.34  5328.5  536.21  5364.6  536.52
  5372.0  537.28  5403.9  538.68  5421.8  538.96  5428.1  539.63  5471.3  540.10
#Mann=8,-1,0
  4398.9    0.05       0  4535.5     0.1       0  4999.3    0.07       0
  5005.6     0.1       0  5138.4    0.05       0  5196.5     0.1       0
  5364.6    0.05       0  5403.9     0.1       0
Bank Sta=4999.3,5005.6
Exp/Cntr=0.3,0.1

Type RM Length L Ch R = 1,17517,206,206,206
BEGIN DESCRIPTION:
Mapping XS e710bbfb
END DESCRIPTION:
XS GIS Cut Line= 4
      1985076.60     13489557.70      1985248.50     13489392.31
      1985616.99     13489066.79      1985859.19     13488855.85
#Sta/Elev= 30
  4442.6  535.10  4478.8  534.22  4514.0  533.89  4528.2  534.50  4549.6  533.93
  4570.6  531.38  4584.3  530.88  4683.9  529.02  4790.1  528.72  4847.0  527.82
  4939.0  528.28  4999.5  527.71  5000.0  526.91  5005.3  526.91  5005.8  527.71
  5087.9  528.80  5108.8  528.48  5116.4  529.07  5123.1  528.58  5130.1  529.32
  5158.0  529.52  5175.9  529.88  5229.3  530.61  5300.6  533.27  5349.9  536.38
  5364.2  536.51  5378.4  538.14  5385.0  537.83  5392.7  538.83  5494.0  541.34
#Mann=6,-1,0
  4442.6    0.05       0  4584.3     0.1       0  4999.5    0.07       0
  5005.8     0.1       0  5158.0    0.05       0  5175.9     0.1       0
Bank Sta=4999.5,5005.8
Exp/Cntr=0.3,0.1

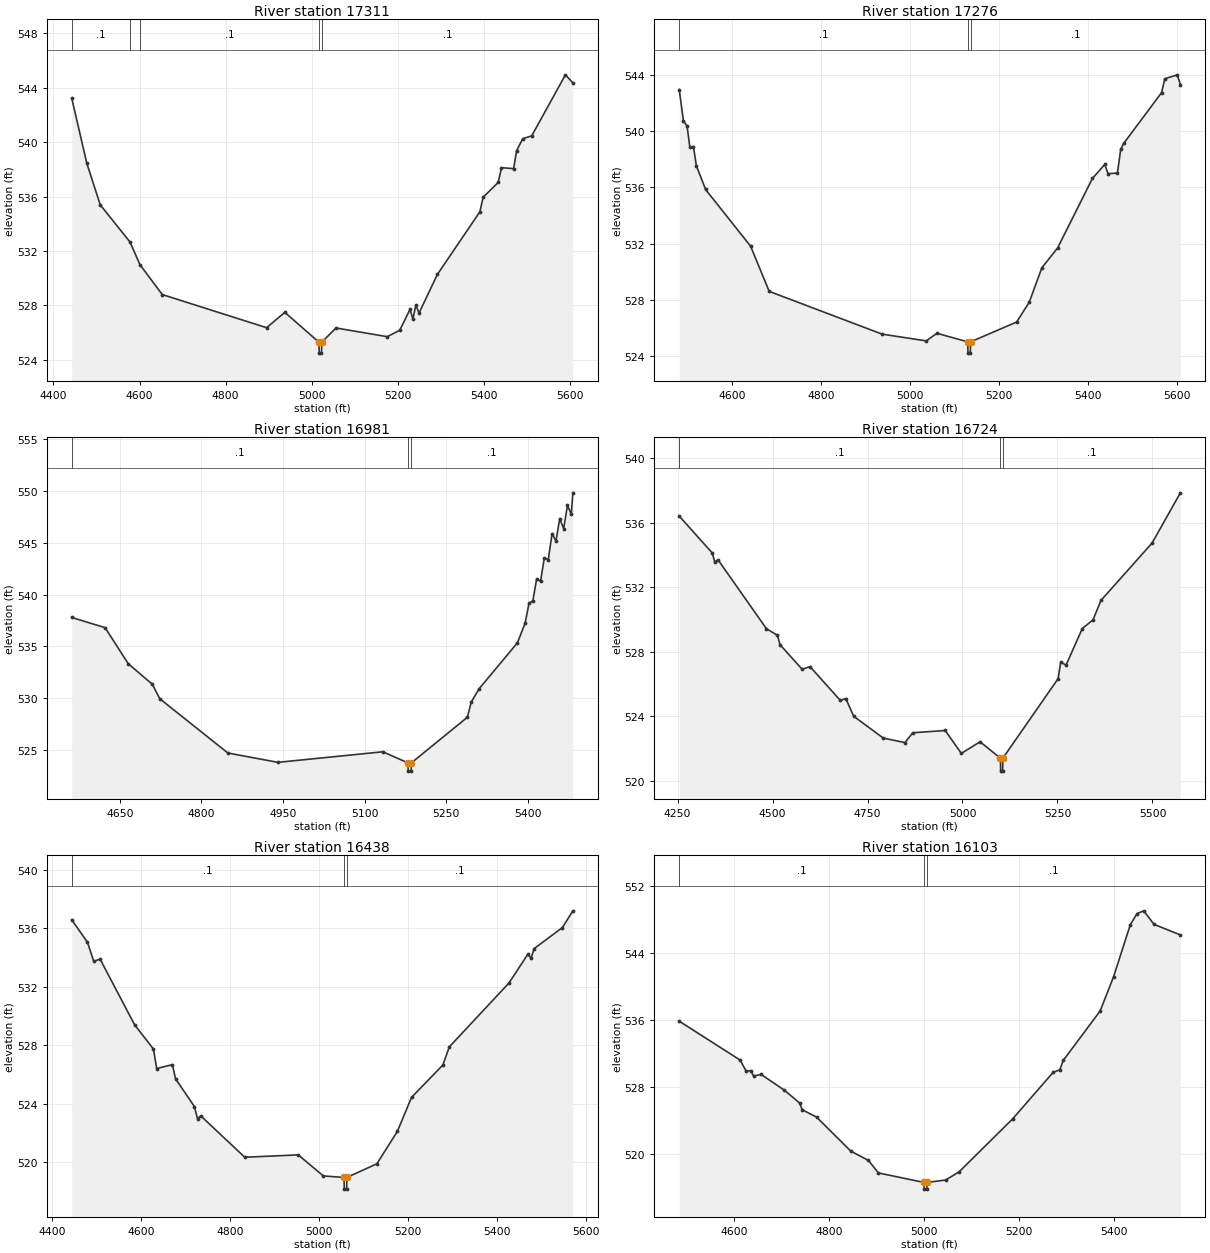
Type RM Length L Ch R = 1,17311,35,35,35
BEGIN DESCRIPTION:
UNT 001 in RCW 30.0
END DESCRIPTION:
XS GIS Cut Line= 4
      1985175.01     13489674.99      1985313.60     13489441.79
      1985777.15     13489280.33      1986077.95     13489013.39
#Sta/Elev= 30
  4442.5  543.25  4477.5  538.46  4508.7  535.40  4578.0  532.66  4600.9  531.00
  4652.8  528.80  4895.3  526.36  4937.6  527.49  5017.0  525.29  5017.5  524.49
  5022.8  524.49  5023.3  525.29  5056.5  526.34  5175.6  525.70  5204.6  526.17
  5228.5  527.71  5235.2  526.99  5241.9  528.02  5249.4  527.44  5292.1  530.28
  5390.8  534.89  5398.3  535.95  5433.4  537.05  5441.0  538.13  5469.2  538.06
  5476.1  539.38  5490.3  540.26  5511.2  540.47  5589.5  544.96  5606.8  544.37
#Mann=5,-1,0
  4442.5     0.1       0  4578.0    0.05       0  4600.9     0.1       0
  5017.0    0.07       0  5023.3     0.1       0
Bank Sta=5017,5023.3
Exp/Cntr=0.3,0.1

Type RM Length L Ch R = 1,17276,295,295,295
BEGIN DESCRIPTION:
Mapping XS e25450d6
END DESCRIPTION:
XS GIS Cut Line= 6
      1985187.28     13489681.41      1985326.63     13489502.99
      1985434.70     13489457.42      1985606.57     13489371.48
      1985768.03     13489324.61      1986080.94     13489041.56
#Sta/Elev= 30
  4481.8  542.95  4491.2  540.74  4499.4  540.36  4505.7  538.86  4513.8  538.90
  4520.2  537.55  4541.0  535.85  4642.2  531.82  4683.9  528.61  4937.6  525.57
  5036.8  525.09  5060.8  525.63  5130.0  525.02  5130.5  524.22  5135.8  524.22
  5136.3  525.02  5239.9  526.43  5268.2  527.84  5296.6  530.29  5331.8  531.69
  5410.2  536.64  5437.9  537.63  5445.3  536.97  5466.3  537.02  5473.7  538.70
  5480.5  539.13  5565.6  542.74  5572.7  543.72  5600.8  544.00  5607.7  543.31
#Mann=3,-1,0
  4481.8     0.1       0  5130.0    0.07       0  5136.3     0.1       0
Bank Sta=5130,5136.3
Exp/Cntr=0.3,0.1

Type RM Length L Ch R = 1,16981,257,257,257
BEGIN DESCRIPTION:
UNT 001 in RCW 29.0
END DESCRIPTION:
XS GIS Cut Line= 3
      1985359.20     13489823.29      1985682.09     13489622.78
      1986060.52     13489236.56
#Sta/Elev= 30
  4561.7  537.79  4623.1  536.80  4665.6  533.31  4709.8  531.33  4723.5  529.93
  4848.7  524.68  4940.6  523.78  5133.3  524.80  5179.5  523.73  5180.0  522.93
  5185.3  522.93  5185.8  523.73  5288.7  528.14  5295.8  529.61  5310.0  530.88
  5380.7  535.34  5394.9  537.26  5401.9  539.15  5409.0  539.41  5416.0  541.53
  5423.1  541.27  5430.1  543.56  5437.3  543.37  5444.3  545.90  5451.4  545.18
  5458.4  547.35  5465.6  546.38  5472.6  548.63  5479.7  547.78  5482.5  549.84
#Mann=3,-1,0
  4561.7     0.1       0  5179.5    0.07       0  5185.8     0.1       0
Bank Sta=5179.5,5185.8
Exp/Cntr=0.3,0.1

Type RM Length L Ch R = 1,16724,286,286,286
BEGIN DESCRIPTION:
Mapping XS 30064696
END DESCRIPTION:
XS GIS Cut Line= 3
      1985350.97     13490182.65      1985734.61     13489901.43
      1986360.65     13489336.09
#Sta/Elev= 30
  4254.3  536.41  4341.6  534.11  4347.8  533.55  4356.3  533.70  4483.7  529.43
  4513.0  529.01  4519.7  528.43  4577.8  526.91  4598.7  527.07  4678.2  524.98
  4692.8  525.09  4713.7  523.99  4791.5  522.64  4848.3  522.36  4869.2  522.97
  4954.4  523.11  4997.0  521.69  5046.3  522.41  5099.9  521.39  5100.4  520.59
  5105.7  520.59  5106.2  521.39  5251.8  526.33  5258.5  527.34  5272.7  527.17
  5315.3  529.43  5343.7  529.98  5364.6  531.18  5499.2  534.74  5573.5  537.85
#Mann=3,-1,0
  4254.3     0.1       0  5099.9    0.07       0  5106.2     0.1       0
Bank Sta=5099.9,5106.2
Exp/Cntr=0.3,0.1

Type RM Length L Ch R = 1,16438,335,335,335
BEGIN DESCRIPTION:
UNT 001 in RCW 28.0
END DESCRIPTION:
XS GIS Cut Line= 3
      1985724.98     13490325.02      1986246.76     13489814.62
      1986533.21     13489540.33
#Sta/Elev= 30
  4443.5  536.57  4478.9  535.03  4493.0  533.73  4507.2  533.88  4584.9  529.39
  4627.3  527.73  4634.5  526.40  4669.8  526.67  4676.9  525.70  4719.3  523.80
  4726.3  522.97  4733.5  523.17  4832.5  520.34  4952.7  520.50  5009.2  519.06
  5055.7  518.96  5056.2  518.16  5061.5  518.16  5062.0  518.96  5129.4  519.89
  5175.6  522.11  5207.3  524.43  5278.0  526.65  5292.2  527.88  5426.5  532.25
  5468.9  534.22  5475.9  533.93  5483.1  534.60  5546.6  536.04  5570.0  537.18
#Mann=3,-1,0
  4443.5     0.1       0  5055.7    0.07       0  5062.0     0.1       0
Bank Sta=5055.7,5062
Exp/Cntr=0.3,0.1

Type RM Length L Ch R = 1,16103,253,253,253
BEGIN DESCRIPTION:
UNT 001 in RCW 27.0
END DESCRIPTION:
XS GIS Cut Line= 3
      1985913.41     13490457.00      1986241.56     13490271.22
      1986705.10     13489776.42
#Sta/Elev= 30
  4484.3  535.86  4612.5  531.21  4625.0  529.91  4635.2  529.93  4640.9  529.30
  4656.8  529.49  4705.8  527.60  4737.6  526.08  4743.4  525.26  4773.4  524.39
  4845.8  520.30  4882.6  519.21  4903.6  517.71  4999.5  516.57  5000.0  515.77
  5005.4  515.77  5005.9  516.57  5045.2  516.86  5073.6  517.84  5186.4  524.18
  5271.4  529.73  5285.6  530.05  5292.9  531.17  5370.6  537.09  5398.9  541.19
  5434.1  547.41  5448.2  548.73  5462.4  549.06  5483.9  547.44  5539.4  546.18
#Mann=3,-1,0
  4484.3     0.1       0  4999.5    0.07       0  5005.9     0.1       0
Bank Sta=4999.5,5005.9
Exp/Cntr=0.3,0.1

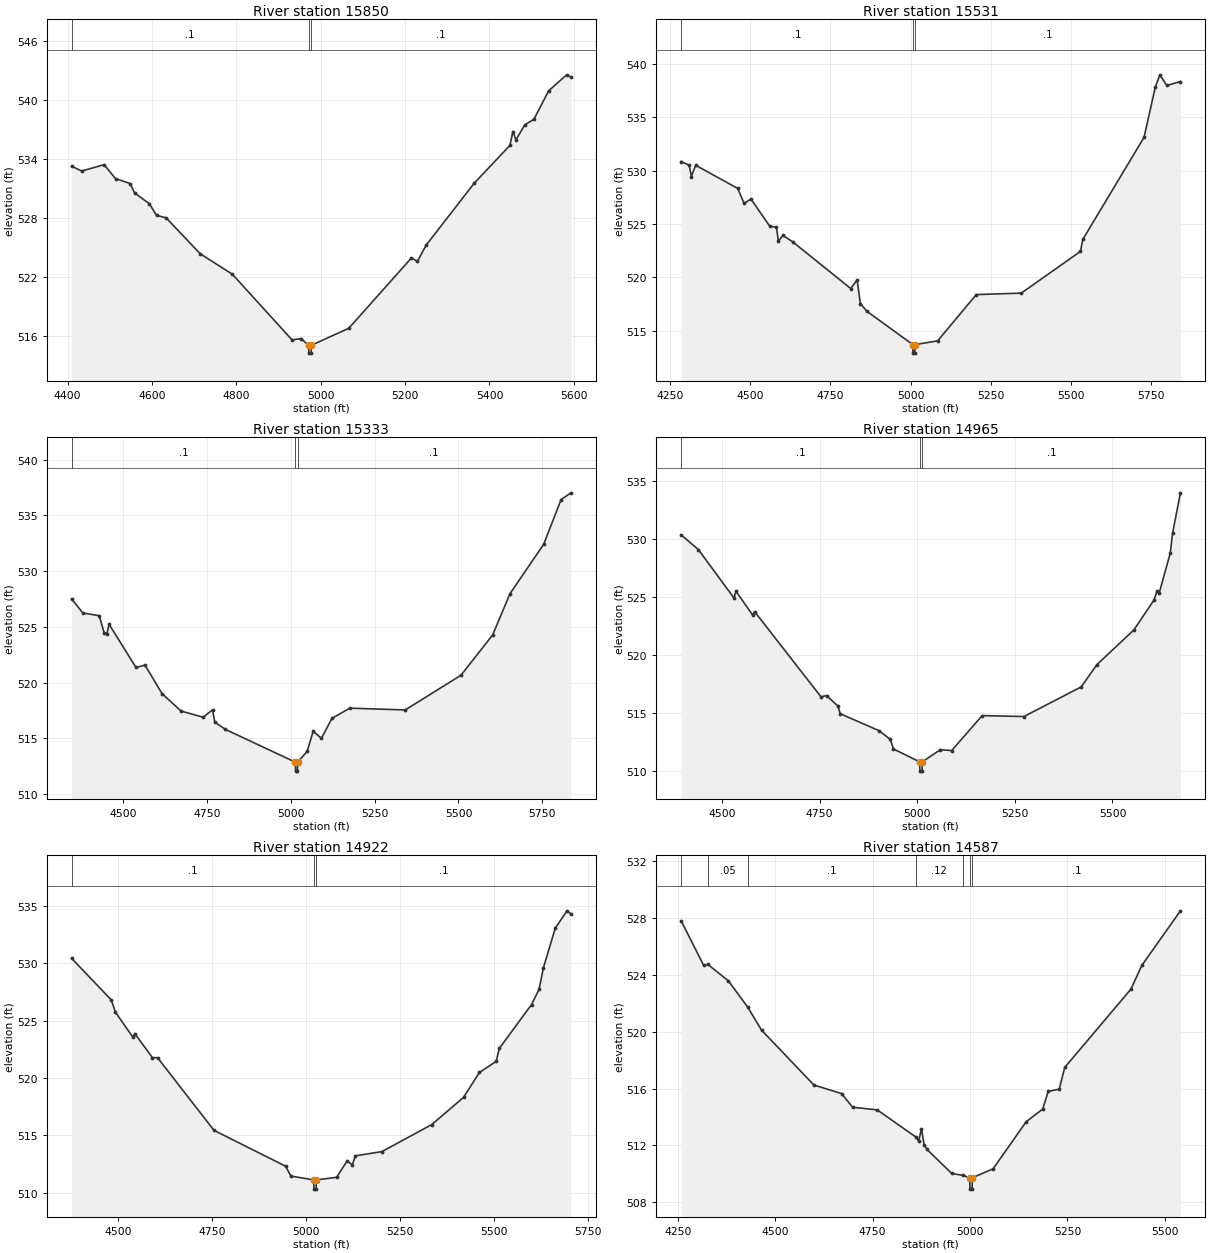
Type RM Length L Ch R = 1,15850,319,319,319
BEGIN DESCRIPTION:
Mapping XS 13c7d552
END DESCRIPTION:
XS GIS Cut Line= 3
      1986010.64     13490547.27      1986378.71     13490448.30
      1986967.28     13489903.14
#Sta/Elev= 30
  4409.5  533.27  4433.5  532.78  4486.5  533.43  4513.5  532.01  4548.2  531.51
  4559.0  530.54  4593.4  529.48  4610.8  528.28  4633.4  528.03  4714.3  524.38
  4790.6  522.30  4932.0  515.63  4953.0  515.77  4971.3  515.09  4971.8  514.29
  4977.2  514.29  4977.7  515.09  5066.4  516.81  5214.9  523.95  5229.1  523.61
  5250.1  525.27  5363.5  531.53  5448.5  535.39  5455.3  536.79  5462.7  535.95
  5483.7  537.47  5505.2  538.03  5540.4  540.94  5582.9  542.55  5592.9  542.32
#Mann=3,-1,0
  4409.5     0.1       0  4971.3    0.07       0  4977.7     0.1       0
Bank Sta=4971.3,4977.7
Exp/Cntr=0.3,0.1

Type RM Length L Ch R = 1,15531,198,198,198
BEGIN DESCRIPTION:
UNT 001 in RCW 26.0
END DESCRIPTION:
XS GIS Cut Line= 4
      1986000.19     13490623.66      1986514.13     13490566.36
      1987088.78     13490521.22      1987406.49     13490186.14
#Sta/Elev= 30
  4285.6  530.87  4310.6  530.52  4317.1  529.46  4330.7  530.52  4461.5  528.35
  4481.6  526.94  4502.9  527.35  4562.1  524.78  4582.2  524.72  4588.3  523.39
  4602.4  523.94  4632.5  523.35  4813.6  518.96  4833.7  519.77  4843.7  517.55
  4863.8  516.83  5007.2  513.70  5007.7  512.90  5013.1  512.90  5013.6  513.70
  5084.5  514.05  5204.8  518.39  5345.3  518.53  5529.3  522.44  5536.6  523.56
  5727.5  533.14  5762.7  537.87  5776.9  539.00  5798.3  538.00  5840.9  538.37
#Mann=3,-1,0
  4285.6     0.1       0  5007.2    0.07       0  5013.6     0.1       0
Bank Sta=5007.2,5013.6
Exp/Cntr=0.3,0.1

Type RM Length L Ch R = 1,15333,368,368,368
BEGIN DESCRIPTION:
Mapping XS 5c47dfa1
END DESCRIPTION:
XS GIS Cut Line= 4
      1986336.59     13491132.36      1986576.19     13490790.32
      1987218.55     13490566.36      1987425.15     13490234.76
#Sta/Elev= 30
  4346.5  527.51  4379.9  526.24  4428.7  526.00  4443.3  524.48  4452.0  524.39
  4458.1  525.23  4538.4  521.35  4565.4  521.56  4615.9  519.01  4672.9  517.44
  4738.0  516.89  4766.6  517.54  4773.4  516.45  4805.2  515.79  5013.8  512.85
  5014.3  512.05  5019.7  512.05  5020.2  512.85  5048.8  513.82  5066.8  515.63
  5091.2  514.99  5122.9  516.79  5175.9  517.70  5341.1  517.54  5507.3  520.65
  5601.7  524.26  5653.7  527.98  5754.0  532.40  5805.9  536.41  5835.1  537.02
#Mann=3,-1,0
  4346.5     0.1       0  5013.8    0.07       0  5020.2     0.1       0
Bank Sta=5013.8,5020.2
Exp/Cntr=0.3,0.1

Type RM Length L Ch R = 1,14965,43,43,43
BEGIN DESCRIPTION:
Mapping XS 2da04215
END DESCRIPTION:
XS GIS Cut Line= 5
      1986472.02     13491281.64      1986820.98     13491200.04
      1987025.84     13490943.09      1987190.77     13490741.71
      1987510.10     13490654.93
#Sta/Elev= 30
  4395.9  530.39  4440.0  529.12  4531.1  524.94  4536.2  525.53  4578.7  523.48
  4583.9  523.77  4753.8  516.42  4767.9  516.53  4796.8  515.64  4803.2  514.96
  4902.4  513.50  4931.3  512.75  4939.3  511.92  5006.5  510.81  5007.0  510.01
  5012.5  510.01  5013.0  510.81  5059.4  511.86  5088.2  511.78  5166.4  514.80
  5273.3  514.72  5420.1  517.28  5460.2  519.20  5554.8  522.19  5606.6  524.78
  5614.2  525.56  5619.4  525.34  5648.1  528.83  5654.0  530.56  5674.1  534.02
#Mann=3,-1,0
  4395.9     0.1       0  5006.5    0.07       0  5013.0     0.1       0
Bank Sta=5006.5,5013
Exp/Cntr=0.3,0.1

Type RM Length L Ch R = 1,14922,335,335,335
BEGIN DESCRIPTION:
UNT 001 in RCW 25.0
END DESCRIPTION:
XS GIS Cut Line= 4
      1986480.75     13491300.73      1986852.23     13491229.55
      1987190.77     13490805.94      1987574.96     13490675.01
#Sta/Elev= 30
  4377.3  530.42  4482.9  526.79  4493.6  525.73  4540.0  523.56  4545.1  523.87
  4592.0  521.77  4605.6  521.77  4755.5  515.44  4945.6  512.32  4960.0  511.46
  5020.8  511.12  5021.3  510.32  5026.8  510.32  5027.3  511.12  5081.4  511.35
  5108.9  512.76  5123.3  512.46  5131.3  513.22  5201.7  513.59  5334.0  515.94
  5418.5  518.31  5460.7  520.48  5505.3  521.45  5513.6  522.58  5599.3  526.40
  5619.2  527.72  5630.7  529.59  5662.0  533.03  5693.3  534.56  5703.7  534.30
#Mann=3,-1,0
  4377.3     0.1       0  5020.8    0.07       0  5027.3     0.1       0
Bank Sta=5020.8,5027.3
Exp/Cntr=0.3,0.1

Type RM Length L Ch R = 1,14587,487,487,487
BEGIN DESCRIPTION:
UNT 001 in RCW 24.0
END DESCRIPTION:
XS GIS Cut Line= 3
      1986701.21     13491762.52      1987225.00     13491275.00
      1987624.97     13490875.03
#Sta/Elev= 30
  4258.8  527.79  4316.5  524.66  4327.5  524.73  4380.0  523.57  4429.4  521.73
  4465.0  520.11  4599.4  516.25  4670.2  515.65  4698.6  514.69  4762.1  514.50
  4861.1  512.59  4868.1  512.31  4875.4  513.16  4882.3  512.04  4889.6  511.72
  4953.1  510.03  4981.1  509.90  4999.3  509.73  4999.8  508.93  5005.4  508.93
  5005.9  509.73  5059.2  510.36  5144.1  513.67  5186.5  514.56  5200.6  515.80
  5228.9  515.96  5243.1  517.49  5412.8  522.99  5441.1  524.67  5540.0  528.50
#Mann=7,-1,0
  4258.8     0.1       0  4327.5    0.05       0  4429.4     0.1       0
  4861.1    0.12       0  4981.1     0.1       0  4999.3    0.07       0
  5005.9     0.1       0
Bank Sta=4999.3,5005.9
Exp/Cntr=0.3,0.1

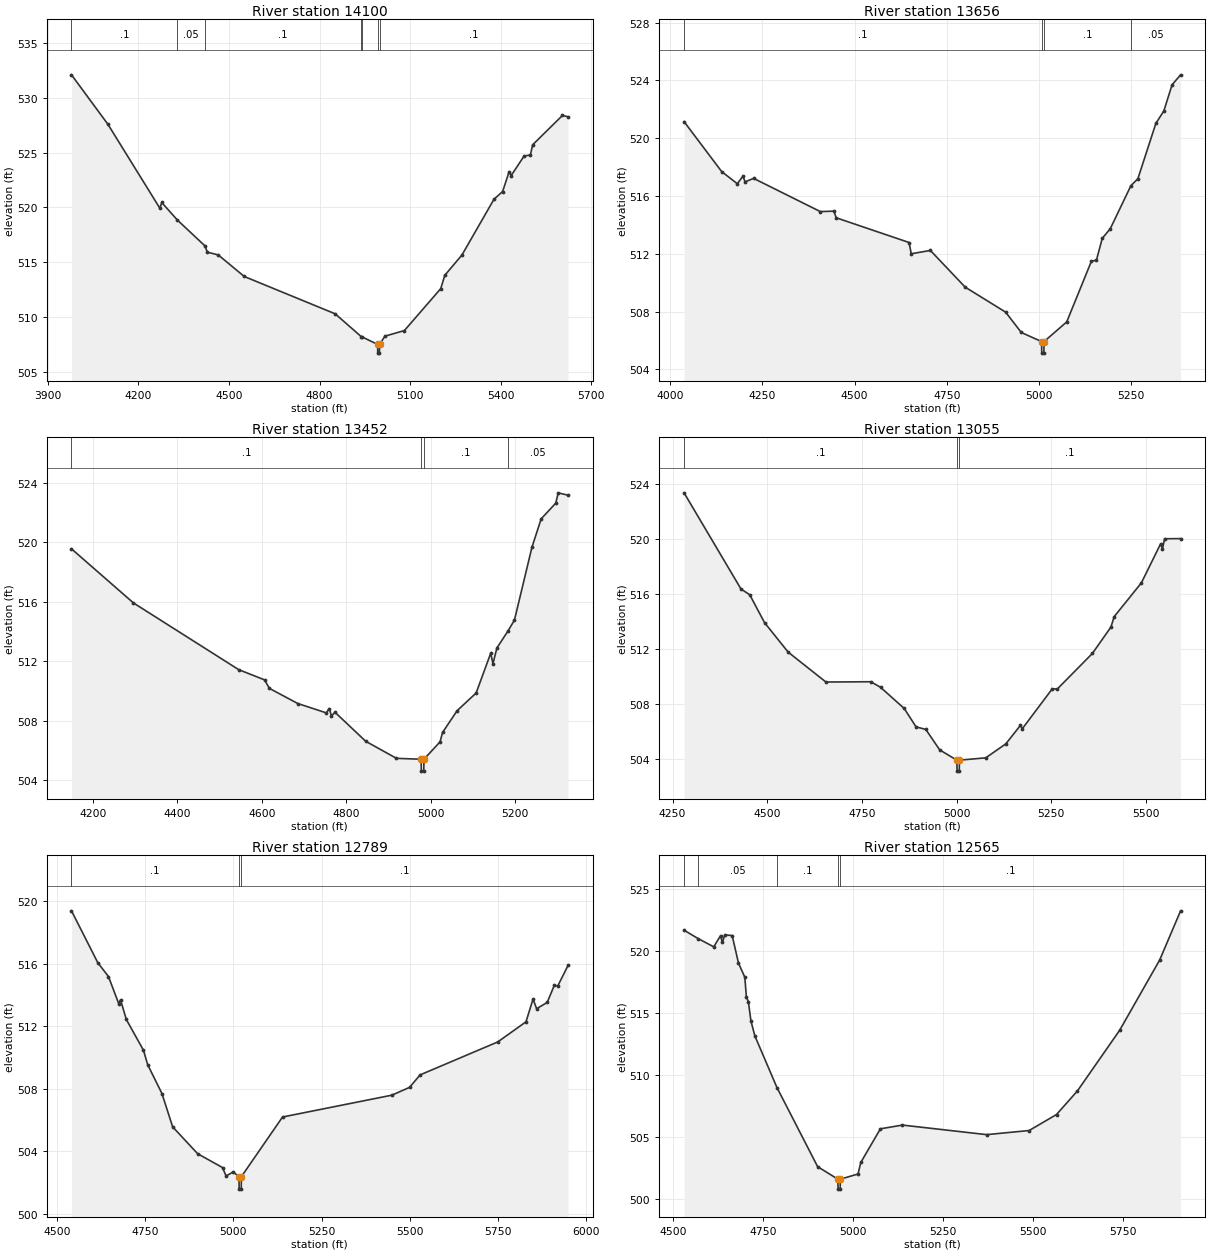
Type RM Length L Ch R = 1,14100,444,444,444
BEGIN DESCRIPTION:
UNT 001 in RCW 23.0
END DESCRIPTION:
XS GIS Cut Line= 3
      1986761.98     13492149.67      1987575.00     13491575.00
      1988060.30     13491144.72
#Sta/Elev= 30
  3978.7  532.10  4099.1  527.59  4271.4  519.91  4277.5  520.44  4329.2  518.84
  4419.7  516.50  4429.0  515.90  4464.7  515.65  4550.8  513.68  4851.9  510.27
  4938.9  508.17  4940.8  508.16  4992.3  507.48  4992.8  506.68  4998.4  506.68
  4998.9  507.48  5016.5  508.23  5081.0  508.74  5201.4  512.57  5214.9  513.79
  5271.6  515.64  5377.8  520.74  5406.3  521.44  5428.0  523.26  5434.7  522.90
  5477.4  524.68  5498.3  524.78  5505.8  525.71  5604.5  528.39  5622.9  528.27
#Mann=7,-1,0
  3978.7     0.1       0  4329.2    0.05       0  4419.7     0.1       0
  4938.9    0.07       0  4940.8     0.1       0  4992.3    0.07       0
  4998.9     0.1       0
Bank Sta=4992.3,4998.9
Exp/Cntr=0.3,0.1

Type RM Length L Ch R = 1,13656,204,204,204
BEGIN DESCRIPTION:
UNT 001 in RCW 22.0
END DESCRIPTION:
XS GIS Cut Line= 3
      1987125.04     13492324.98      1987925.00     13491825.00
      1988125.02     13491474.97
#Sta/Elev= 30
  4037.4  521.15  4139.4  517.69  4181.8  516.85  4197.1  517.37  4203.0  516.98
  4226.0  517.22  4407.0  514.92  4443.6  514.95  4450.1  514.49  4647.6  512.78
  4653.5  512.00  4705.4  512.23  4799.7  509.69  4909.4  507.96  4951.9  506.55
  5006.9  505.92  5007.4  505.12  5013.1  505.12  5013.6  505.92  5075.1  507.28
  5142.0  511.48  5155.7  511.56  5171.5  513.07  5193.1  513.73  5249.3  516.72
  5268.0  517.19  5316.9  521.03  5338.5  521.89  5360.8  523.70  5383.9  524.39
#Mann=4,-1,0
  4037.4     0.1       0  5006.9    0.07       0  5013.6     0.1       0
  5249.3    0.05       0
Bank Sta=5006.9,5013.6
Exp/Cntr=0.3,0.1

Type RM Length L Ch R = 1,13452,397,397,397
BEGIN DESCRIPTION:
Mapping XS 79b67881
END DESCRIPTION:
XS GIS Cut Line= 3
      1987895.19     13492666.23      1988037.56     13492159.24
      1988207.70     13491532.52
#Sta/Elev= 30
  4149.1  519.56  4295.8  515.92  4545.1  511.43  4606.5  510.74  4617.8  510.17
  4685.1  509.15  4752.6  508.52  4759.6  508.81  4764.8  508.32  4773.3  508.56
  4845.9  506.61  4918.8  505.46  4977.2  505.40  4977.7  504.60  4983.4  504.60
  4983.9  505.40  5022.0  506.57  5027.9  507.20  5062.5  508.67  5107.5  509.86
  5142.1  512.54  5147.3  511.83  5156.7  512.89  5182.4  514.01  5198.2  514.76
  5239.6  519.66  5261.5  521.58  5296.2  522.64  5301.8  523.33  5325.1  523.17
#Mann=4,-1,0
  4149.1     0.1       0  4977.2    0.07       0  4983.9     0.1       0
  5182.4    0.05       0
Bank Sta=4977.2,4983.9
Exp/Cntr=0.3,0.1

Type RM Length L Ch R = 1,13055,266,266,266
BEGIN DESCRIPTION:
UNT 001 in RCW 21.0
END DESCRIPTION:
XS GIS Cut Line= 3
      1988179.94     13492778.99      1988440.34     13492025.56
      1988329.61     13491523.80
#Sta/Elev= 30
  4280.3  523.39  4430.5  516.38  4453.8  515.95  4492.8  513.92  4555.2  511.77
  4654.8  509.59  4773.4  509.61  4799.3  509.20  4861.6  507.66  4892.8  506.32
  4918.7  506.13  4955.2  504.64  5000.6  503.89  5001.1  503.09  5006.9  503.09
  5007.4  503.89  5076.9  504.06  5129.9  505.08  5168.5  506.43  5173.6  506.19
  5252.1  509.08  5266.1  509.09  5358.6  511.68  5407.4  513.60  5416.0  514.36
  5487.7  516.82  5538.4  519.66  5543.5  519.31  5549.1  520.04  5591.3  520.05
#Mann=3,-1,0
  4280.3     0.1       0  5000.6    0.07       0  5007.4     0.1       0
Bank Sta=5000.6,5007.4
Exp/Cntr=0.3,0.1

Type RM Length L Ch R = 1,12789,224,224,224
BEGIN DESCRIPTION:
UNT 001 in RCW 20.0
END DESCRIPTION:
XS GIS Cut Line= 3
      1988560.13     13492698.73      1988620.90     13492282.07
      1988626.10     13491295.95
#Sta/Elev= 30
  4541.4  519.40  4615.9  516.08  4646.2  515.19  4675.3  513.45  4680.3  513.70
  4696.8  512.44  4745.3  510.47  4757.4  509.54  4797.8  507.69  4828.1  505.56
  4898.9  503.84  4969.5  502.95  4979.5  502.41  4999.5  502.67  5016.1  502.37
  5016.6  501.57  5022.4  501.57  5022.9  502.37  5139.5  506.19  5449.5  507.59
  5499.5  508.09  5529.5  508.89  5749.5  511.00  5829.5  512.29  5849.5  513.75
  5859.6  513.13  5889.6  513.53  5909.6  514.62  5919.6  514.59  5948.6  515.90
#Mann=3,-1,0
  4541.4     0.1       0  5016.1    0.07       0  5022.9     0.1       0
Bank Sta=5016.1,5022.9
Exp/Cntr=0.3,0.1

Type RM Length L Ch R = 1,12565,331,331,331
BEGIN DESCRIPTION:
Mapping XS 38a97e9e
END DESCRIPTION:
XS GIS Cut Line= 3
      1988731.58     13492755.61      1988696.85     13492590.66
      1989174.20     13491479.74
#Sta/Elev= 30
  4530.9  521.69  4570.1  521.01  4613.3  520.35  4632.1  521.25  4637.2  520.70
  4643.9  521.31  4664.4  521.26  4681.9  519.04  4699.5  517.90  4703.8  516.30
  4709.3  515.94  4716.5  514.37  4727.4  513.17  4788.7  509.01  4901.5  502.64
  4957.7  501.63  4958.2  500.83  4964.0  500.83  4964.5  501.63  5013.6  502.05
  5021.3  502.98  5075.7  505.69  5136.8  505.99  5370.5  505.22  5488.3  505.55
  5564.3  506.84  5622.3  508.74  5739.6  513.63  5850.6  519.29  5908.6  523.25
#Mann=5,-1,0
  4530.9     0.1       0  4570.1    0.05       0  4788.7     0.1       0
  4957.7    0.07       0  4964.5     0.1       0
Bank Sta=4957.7,4964.5
Exp/Cntr=0.3,0.1