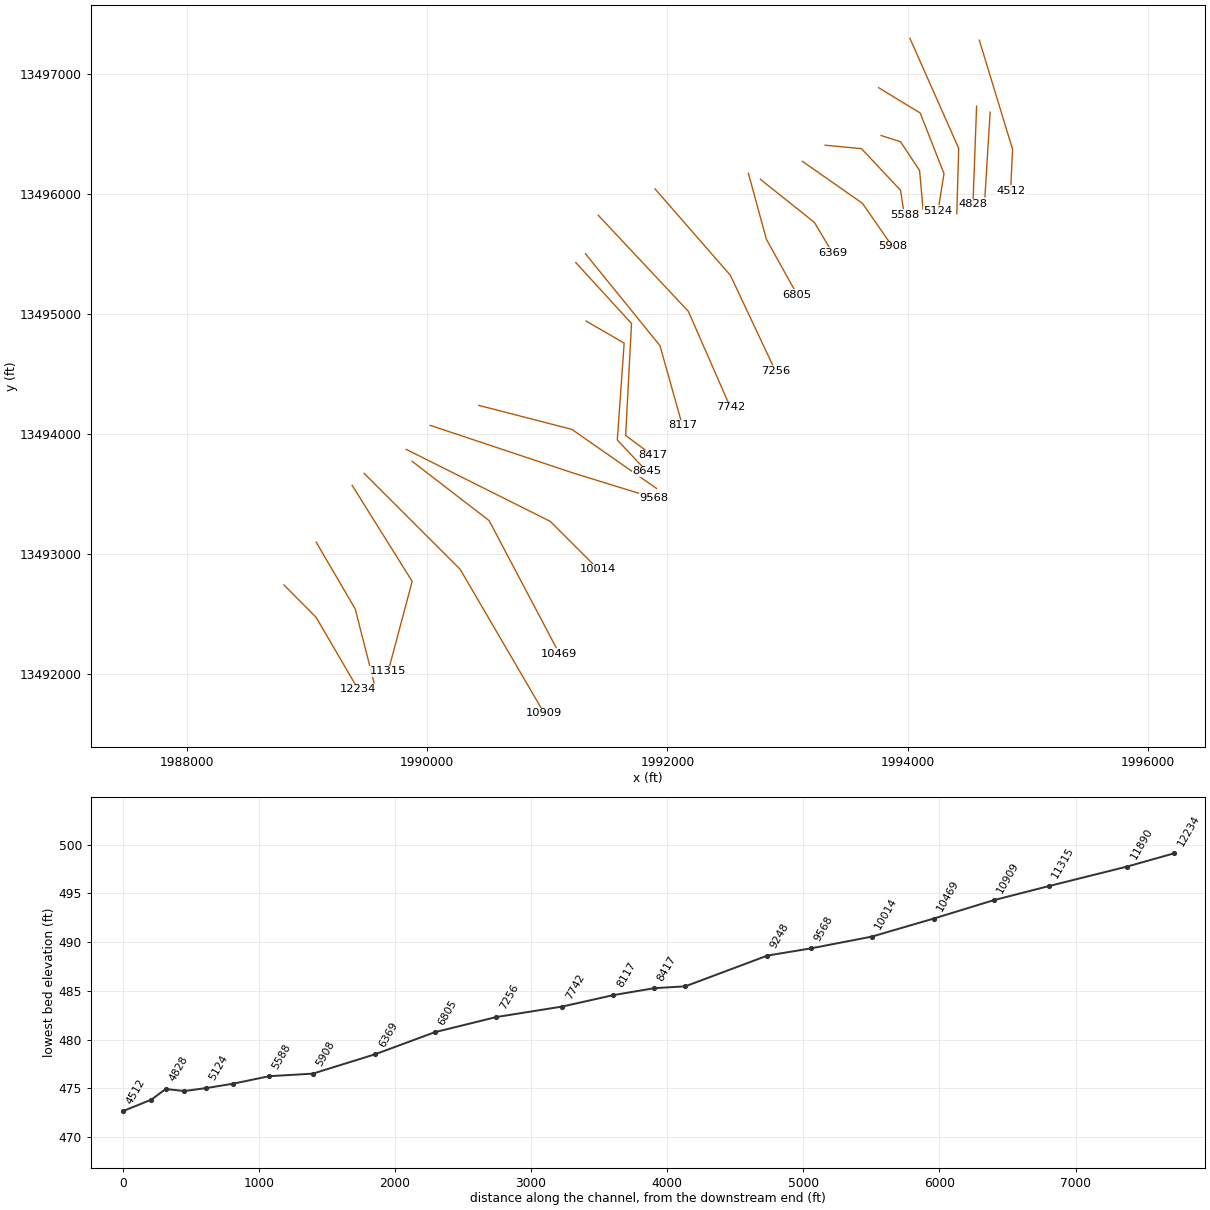
HEC-RAS study UNT 001 in RCW.prj: UNT 001 in RCW Base Level Engineering

--- UNT 001 in RCW.g01 (geometry) --- (continued)

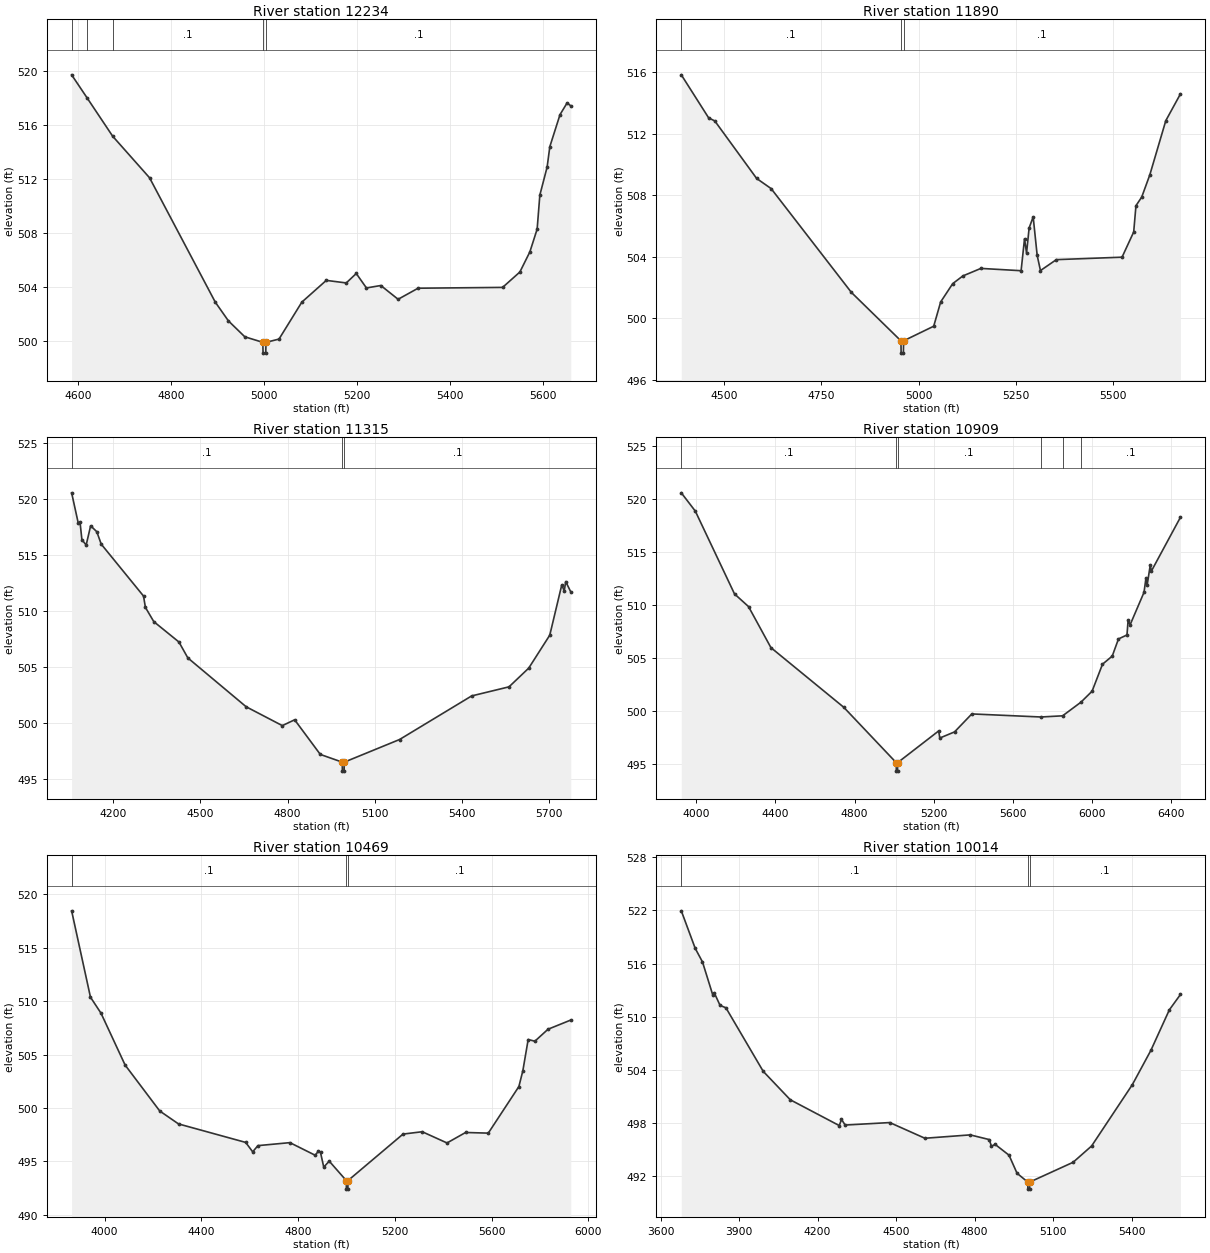
Type RM Length L Ch R = 1,12234,344,344,344
BEGIN DESCRIPTION:
UNT 001 in RCW 19.0
END DESCRIPTION:
XS GIS Cut Line= 3
      1988807.53     13492744.75      1989075.00     13492475.00
      1989425.00     13491875.00
#Sta/Elev= 30
  4586.3  519.71  4620.2  517.97  4674.7  515.16  4754.1  512.08  4895.5  502.87
  4923.8  501.48  4959.1  500.30  4997.9  499.89  4998.4  499.09  5004.2  499.09
  5004.7  499.89  5032.7  500.13  5081.9  502.87  5134.5  504.48  5177.5  504.29
  5199.0  504.99  5220.9  503.92  5251.9  504.10  5289.1  503.08  5332.1  503.90
  5514.0  503.96  5551.2  505.10  5572.7  506.59  5588.4  508.28  5594.2  510.80
  5609.9  512.88  5615.7  514.39  5637.6  516.76  5652.9  517.63  5660.8  517.41
#Mann=5,-1,0
  4586.3     0.1       0  4620.2    0.05       0  4674.7     0.1       0
  4997.9    0.07       0  5004.7     0.1       0
Bank Sta=4997.9,5004.7
Exp/Cntr=0.3,0.1

Type RM Length L Ch R = 1,11890,575,575,575
BEGIN DESCRIPTION:
UNT 001 in RCW 18.0
END DESCRIPTION:
XS GIS Cut Line= 3
      1989075.32     13493101.95      1989400.84     13492544.66
      1989558.08     13491928.71
#Sta/Elev= 30
  4391.1  515.84  4461.3  513.04  4477.1  512.84  4584.5  509.10  4621.7  508.44
  4827.6  501.69  4954.8  498.54  4955.3  497.74  4961.1  497.74  4961.6  498.54
  5038.9  499.49  5056.8  501.07  5087.7  502.26  5113.7  502.76  5160.0  503.25
  5263.2  503.10  5272.0  505.18  5277.2  504.25  5283.8  505.88  5294.2  506.60
  5304.5  504.09  5312.9  503.11  5353.7  503.82  5522.3  503.98  5552.2  505.62
  5558.0  507.33  5572.8  507.89  5593.5  509.33  5634.6  512.86  5672.2  514.60
#Mann=3,-1,0
  4391.1     0.1       0  4954.8    0.07       0  4961.6     0.1       0
Bank Sta=4954.8,4961.6
Exp/Cntr=0.3,0.1

Type RM Length L Ch R = 1,11315,406,406,406
BEGIN DESCRIPTION:
UNT 001 in RCW 17.0
END DESCRIPTION:
XS GIS Cut Line= 3
      1989374.99     13493575.02      1989875.00     13492775.00
      1989675.01     13492025.03
#Sta/Elev= 30
  4056.1  520.57  4079.1  517.85  4085.0  517.97  4091.5  516.39  4106.2  515.91
  4121.6  517.63  4142.8  517.10  4158.1  515.99  4303.8  511.36  4310.3  510.35
  4339.1  509.08  4425.8  507.26  4456.5  505.84  4657.5  501.48  4782.0  499.80
  4824.4  500.32  4912.8  497.23  4988.4  496.54  4988.9  495.74  4994.8  495.74
  4995.3  496.54  5185.8  498.56  5434.2  502.45  5562.9  503.26  5630.8  504.93
  5703.3  507.87  5744.7  512.36  5753.1  511.82  5758.3  512.65  5775.7  511.73
#Mann=3,-1,0
  4056.1     0.1       0  4988.4    0.07       0  4995.3     0.1       0
Bank Sta=4988.4,4995.3
Exp/Cntr=0.3,0.1

Type RM Length L Ch R = 1,10909,440,440,440
BEGIN DESCRIPTION:
UNT 001 in RCW 16.0
END DESCRIPTION:
XS GIS Cut Line= 3
      1989474.97     13493675.03      1990275.00     13492875.00
      1990975.02     13491674.96
#Sta/Elev= 30
  3925.1  520.61  3995.9  518.88  4193.8  511.05  4264.6  509.85  4377.7  505.97
  4745.4  500.33  5010.6  495.09  5011.1  494.29  5017.0  494.29  5017.5  495.09
  5224.8  498.09  5230.6  497.42  5305.0  498.00  5392.2  499.70  5740.7  499.41
  5850.6  499.52  5943.3  500.81  5999.6  501.85  6052.1  504.40  6101.3  505.17
  6132.8  506.79  6175.8  507.17  6181.6  508.60  6191.1  508.11  6261.8  511.20
  6271.7  512.56  6277.5  511.86  6293.2  513.77  6299.0  513.21  6445.8  518.30
#Mann=6,-1,0
  3925.1     0.1       0  5010.6    0.07       0  5017.5     0.1       0
  5740.7    0.12       0  5850.6    0.07       0  5943.3     0.1       0
Bank Sta=5010.6,5017.5
Exp/Cntr=0.3,0.1

Type RM Length L Ch R = 1,10469,455,455,455
BEGIN DESCRIPTION:
UNT 001 in RCW 15.0
END DESCRIPTION:
XS GIS Cut Line= 3
      1989874.96     13493775.03      1990515.86     13493281.20
      1991100.90     13492171.79
#Sta/Elev= 30
  3863.9  518.45  3941.8  510.37  3985.4  508.87  4085.0  504.02  4228.2  499.72
  4305.8  498.51  4583.5  496.78  4612.3  495.90  4634.0  496.48  4766.2  496.76
  4870.7  495.58  4883.5  495.95  4892.7  495.84  4906.1  494.47  4928.7  495.03
  4999.3  493.21  4999.8  492.41  5005.8  492.41  5006.3  493.21  5233.8  497.56
  5313.1  497.78  5415.6  496.73  5492.4  497.71  5586.2  497.65  5712.7  502.01
  5729.0  503.48  5751.1  506.41  5778.7  506.25  5833.1  507.37  5927.2  508.23
#Mann=3,-1,0
  3863.9     0.1       0  4999.3    0.07       0  5006.3     0.1       0
Bank Sta=4999.3,5006.3
Exp/Cntr=0.3,0.1

Type RM Length L Ch R = 1,10014,446,446,446
BEGIN DESCRIPTION:
UNT 001 in RCW 14.0
END DESCRIPTION:
XS GIS Cut Line= 3
      1989825.01     13493875.00      1991025.00     13493275.00
      1991424.99     13492875.01
#Sta/Elev= 30
  3679.3  521.96  3732.4  517.73  3760.3  516.19  3799.5  512.47  3805.1  512.72
  3827.4  511.29  3849.8  511.02  3992.3  503.85  4095.8  500.64  4283.0  497.73
  4291.4  498.43  4305.4  497.79  4475.9  498.07  4610.1  496.30  4783.3  496.68
  4856.0  496.15  4864.4  495.40  4878.4  495.61  4931.5  494.39  4962.2  492.35
  5003.0  491.36  5003.7  490.56  5010.3  490.56  5010.9  491.36  5176.5  493.59
  5247.2  495.43  5402.8  502.35  5473.5  506.21  5544.2  510.79  5586.6  512.52
#Mann=3,-1,0
  3679.3     0.1       0  5003.0    0.07       0  5010.9     0.1       0
Bank Sta=5003,5010.9
Exp/Cntr=0.3,0.1

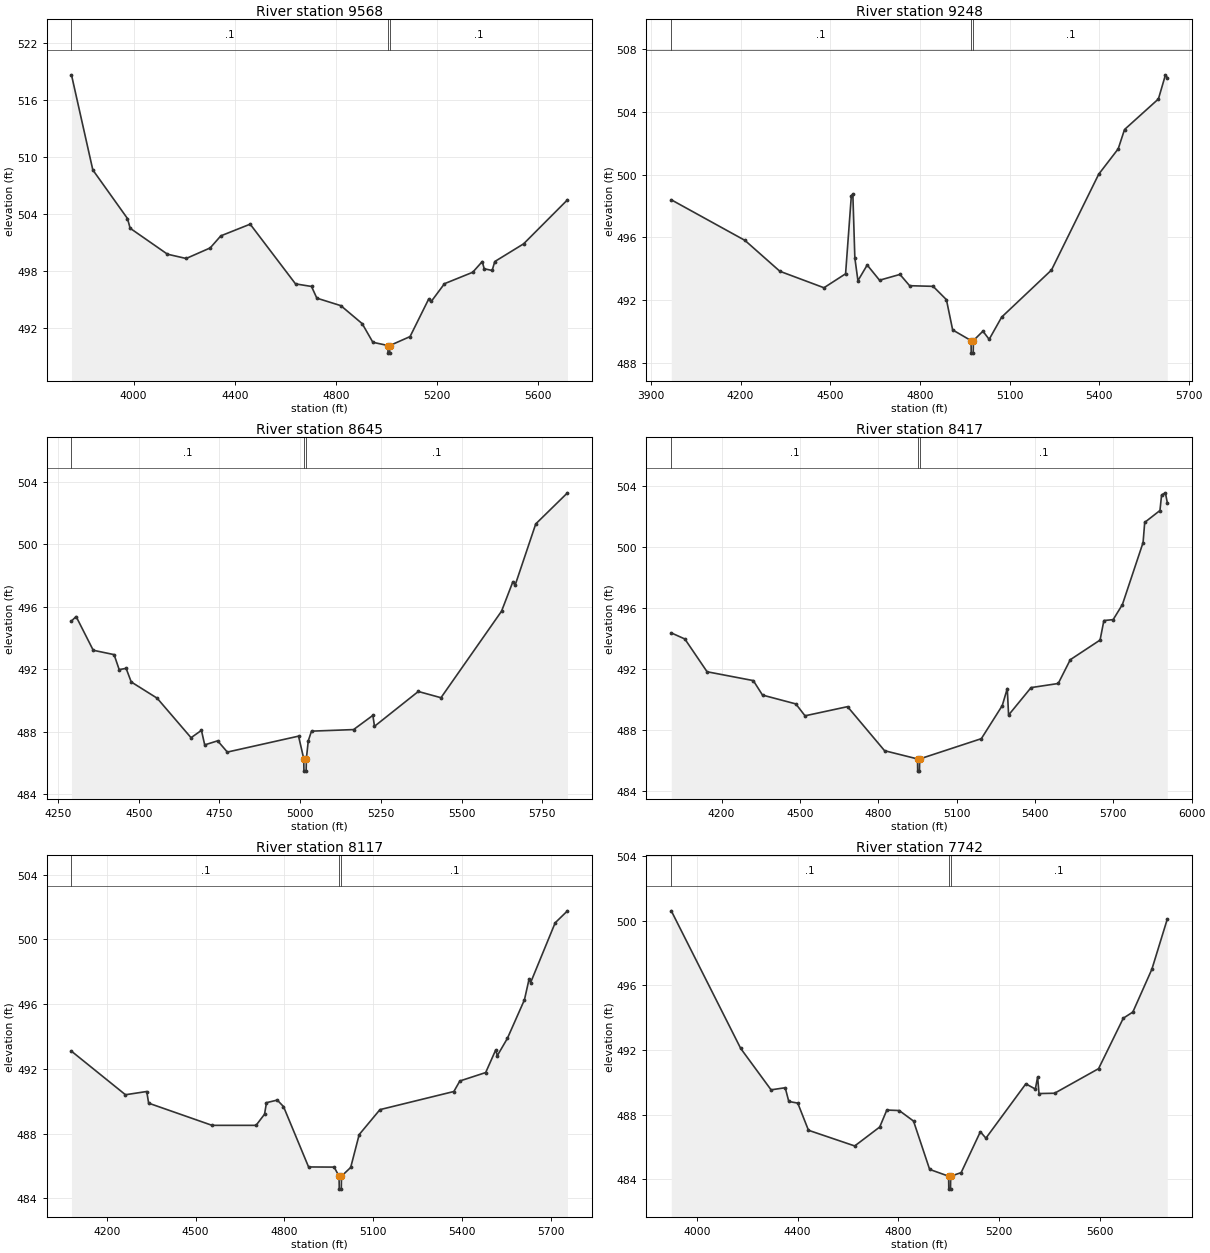
Type RM Length L Ch R = 1,9568,320,320,320
BEGIN DESCRIPTION:
UNT 001 in RCW 13.0
END DESCRIPTION:
XS GIS Cut Line= 3
      1990024.96     13494075.01      1991225.00     13493675.00
      1991889.55     13493470.01
#Sta/Elev= 30
  3754.6  518.62  3839.0  508.62  3976.0  503.51  3986.5  502.49  4134.1  499.76
  4207.9  499.31  4302.8  500.42  4344.9  501.69  4460.9  502.92  4640.1  496.64
  4703.3  496.37  4724.4  495.14  4819.3  494.35  4903.6  492.46  4945.8  490.50
  5005.1  490.16  5005.7  489.36  5012.3  489.36  5013.0  490.16  5092.8  491.10
  5166.1  495.03  5177.0  494.81  5228.8  496.66  5340.3  497.86  5378.2  498.99
  5385.8  498.23  5417.2  498.05  5427.7  498.99  5541.5  500.85  5715.0  505.48
#Mann=3,-1,0
  3754.6     0.1       0  5005.1    0.07       0  5013.0     0.1       0
Bank Sta=5005.1,5013
Exp/Cntr=0.3,0.1

Type RM Length L Ch R = 1,9248,603,603,603
BEGIN DESCRIPTION:
UNT 001 in RCW 12.0
END DESCRIPTION:
XS GIS Cut Line= 3
      1990430.33     13494241.28      1991204.66     13494041.62
      1991909.64     13493549.69
#Sta/Elev= 30
  3968.2  498.40  4214.7  495.81  4331.5  493.84  4479.0  492.79  4551.3  493.68
  4570.5  498.65  4575.6  498.77  4582.3  494.69  4592.6  493.24  4623.6  494.24
  4664.9  493.27  4733.2  493.64  4765.5  492.92  4844.1  492.88  4888.6  492.03
  4909.5  490.10  4971.0  489.42  4971.6  488.62  4978.2  488.62  4978.9  489.42
  5010.7  490.02  5031.6  489.50  5073.5  490.92  5240.1  493.92  5398.0  500.03
  5463.3  501.65  5484.4  502.88  5597.8  504.83  5621.4  506.37  5627.5  506.19
#Mann=3,-1,0
  3968.2     0.1       0  4971.0    0.07       0  4978.9     0.1       0
Bank Sta=4971,4978.9
Exp/Cntr=0.3,0.1

Type RM Length L Ch R = 1,8645,228,228,228
BEGIN DESCRIPTION:
Mapping XS 93264445
END DESCRIPTION:
XS GIS Cut Line= 4
      1991322.69     13494944.41      1991640.43     13494760.37
      1991583.14     13493953.08      1991829.68     13493690.90
#Sta/Elev= 30
  4291.6  495.08  4306.0  495.37  4359.0  493.21  4423.6  492.93  4439.4  491.97
  4460.9  492.05  4476.7  491.18  4557.0  490.14  4662.0  487.61  4694.2  488.08
  4704.3  487.15  4744.4  487.41  4774.4  486.69  4995.0  487.71  5011.0  486.27
  5011.7  485.47  5018.5  485.47  5019.2  486.27  5025.1  487.41  5035.1  488.03
  5165.4  488.13  5225.2  489.04  5230.2  488.34  5365.9  490.57  5436.1  490.17
  5623.7  495.71  5658.9  497.60  5666.2  497.40  5729.7  501.30  5828.0  503.29
#Mann=3,-1,0
  4291.6     0.1       0  5011.0    0.07       0  5019.2     0.1       0
Bank Sta=5011,5019.2
Exp/Cntr=0.3,0.1

Type RM Length L Ch R = 1,8417,300,300,300
BEGIN DESCRIPTION:
UNT 001 in RCW 11.0
END DESCRIPTION:
XS GIS Cut Line= 4
      1991237.64     13495431.39      1991701.74     13494923.58
      1991652.58     13493991.27      1991874.97     13493825.02
#Sta/Elev= 30
  4007.5  494.35  4059.5  493.95  4144.6  491.80  4321.6  491.22  4356.8  490.27
  4484.4  489.69  4519.6  488.91  4682.4  489.51  4824.2  486.62  4950.3  486.08
  4951.0  485.28  4957.8  485.28  4958.5  486.08  5194.7  487.41  5274.8  489.58
  5294.0  490.70  5299.0  488.96  5385.0  490.76  5489.1  491.03  5535.2  492.59
  5649.3  493.88  5663.9  495.16  5699.4  495.22  5734.8  496.21  5814.0  500.28
  5820.2  501.60  5878.6  502.38  5884.8  503.40  5899.4  503.54  5906.7  502.90
#Mann=3,-1,0
  4007.5     0.1       0  4950.3    0.07       0  4958.5     0.1       0
Bank Sta=4950.3,4958.5
Exp/Cntr=0.3,0.1

Type RM Length L Ch R = 1,8117,375,375,375
BEGIN DESCRIPTION:
UNT 001 in RCW 10.0
END DESCRIPTION:
XS GIS Cut Line= 3
      1991317.97     13495505.13      1991938.60     13494739.10
      1992125.01     13494074.96
#Sta/Elev= 30
  4080.4  493.09  4262.8  490.40  4334.7  490.60  4341.1  489.88  4555.3  488.51
  4704.0  488.51  4732.7  489.20  4739.2  489.91  4775.6  490.07  4796.7  489.67
  4881.4  485.94  4967.7  485.93  4984.4  485.37  4985.1  484.57  4991.9  484.57
  4992.6  485.37  5023.7  485.91  5052.4  487.94  5122.5  489.48  5372.2  490.60
  5392.5  491.25  5479.7  491.77  5513.7  493.17  5518.9  492.81  5553.0  493.88
  5610.6  496.26  5626.4  497.55  5631.6  497.33  5714.5  501.02  5756.1  501.76
#Mann=3,-1,0
  4080.4     0.1       0  4984.4    0.07       0  4992.6     0.1       0
Bank Sta=4984.4,4992.6
Exp/Cntr=0.3,0.1

Type RM Length L Ch R = 1,7742,486,486,486
BEGIN DESCRIPTION:
UNT 001 in RCW 9.0
END DESCRIPTION:
XS GIS Cut Line= 3
      1991425.03     13495824.97      1992175.00     13495025.00
      1992525.02     13494224.96
#Sta/Elev= 30
  3898.7  500.61  4174.4  492.10  4295.0  489.54  4351.2  489.67  4365.4  488.82
  4401.0  488.72  4443.5  487.04  4627.2  486.07  4726.4  487.24  4754.7  488.29
  4804.0  488.26  4860.7  487.61  4924.7  484.62  5000.1  484.20  5000.8  483.40
  5007.6  483.40  5008.3  484.20  5049.8  484.42  5126.2  486.95  5148.1  486.55
  5306.7  489.91  5344.5  489.59  5353.5  490.33  5359.0  489.31  5420.9  489.33
  5595.6  490.85  5693.8  493.97  5731.6  494.35  5807.3  497.00  5868.5  500.10
#Mann=3,-1,0
  3898.7     0.1       0  5000.1    0.07       0  5008.3     0.1       0
Bank Sta=5000.1,5008.3
Exp/Cntr=0.3,0.1

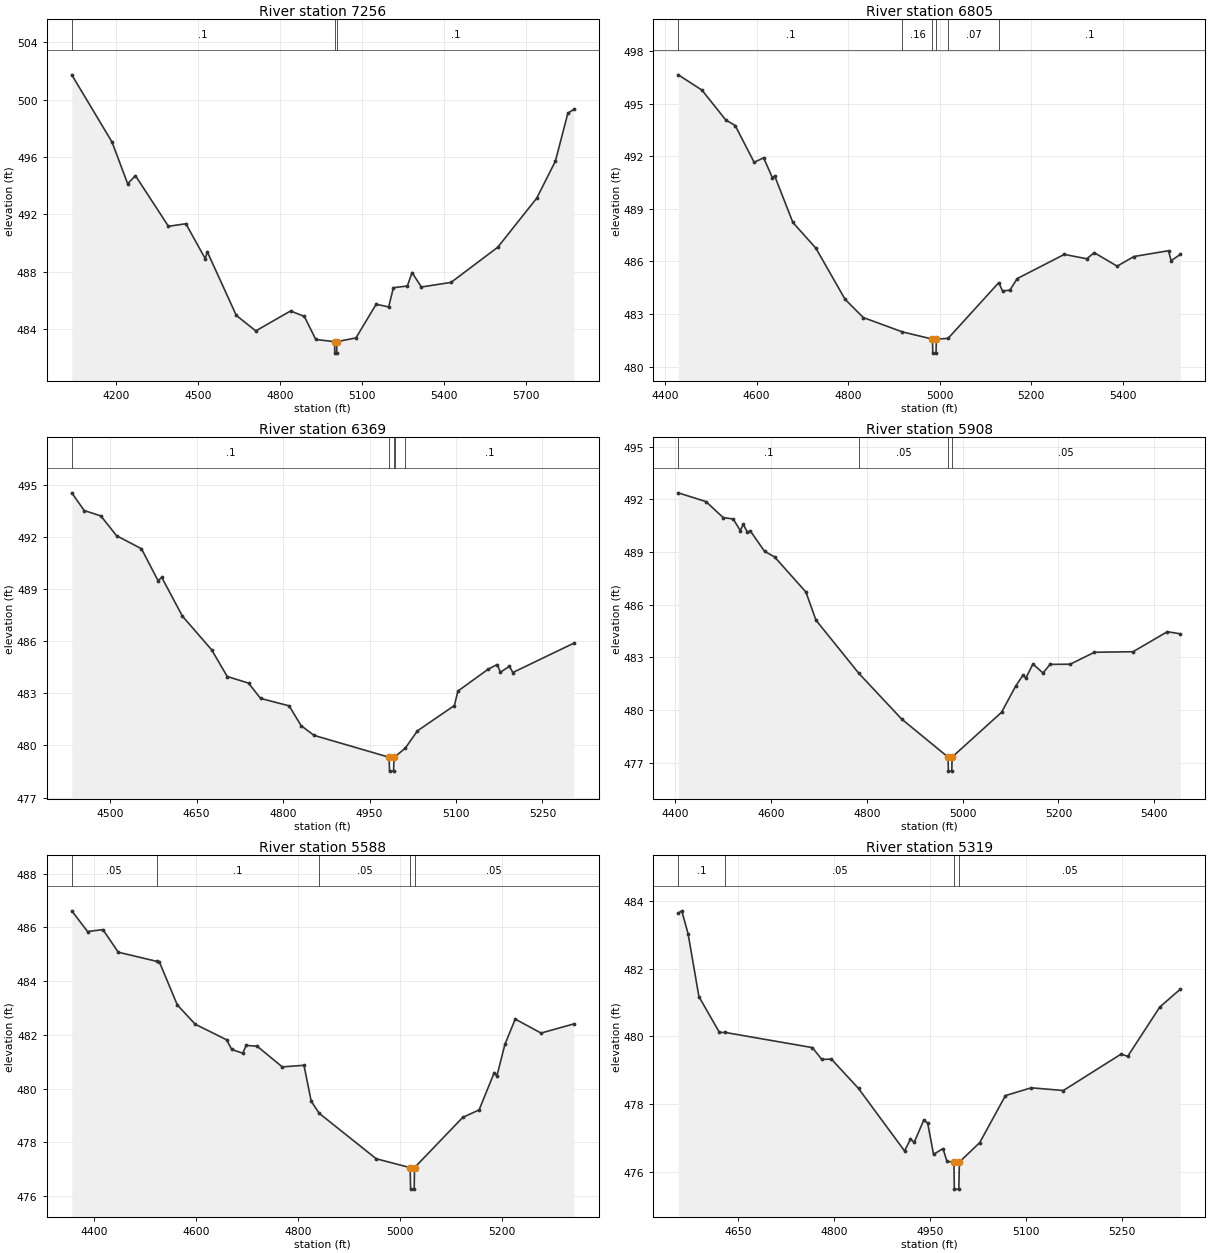
Type RM Length L Ch R = 1,7256,451,451,451
BEGIN DESCRIPTION:
UNT 001 in RCW 8.0
END DESCRIPTION:
XS GIS Cut Line= 3
      1991897.34     13496045.56      1992525.00     13495325.00
      1992899.25     13494530.20
#Sta/Elev= 30
  4039.7  501.72  4186.9  497.03  4243.8  494.13  4272.3  494.69  4392.9  491.16
  4456.5  491.34  4527.7  488.89  4534.4  489.40  4640.7  484.95  4711.9  483.87
  4839.1  485.26  4889.2  484.88  4931.2  483.27  4999.8  483.12  5000.5  482.32
  5007.3  482.32  5008.1  483.12  5077.8  483.38  5151.7  485.73  5197.3  485.54
  5214.6  486.88  5265.7  487.00  5282.7  487.94  5316.8  486.93  5425.2  487.25
  5595.8  489.70  5738.1  493.12  5806.4  495.70  5852.0  499.05  5873.8  499.31
#Mann=3,-1,0
  4039.7     0.1       0  4999.8    0.07       0  5008.1     0.1       0
Bank Sta=4999.8,5008.1
Exp/Cntr=0.3,0.1

Type RM Length L Ch R = 1,6805,436,436,436
BEGIN DESCRIPTION:
UNT 001 in RCW 7.0
END DESCRIPTION:
XS GIS Cut Line= 3
      1992675.00     13496175.01      1992825.00     13495625.00
      1993080.79     13495164.35
#Sta/Elev= 30
  4428.7  496.64  4480.5  495.77  4532.4  494.07  4553.1  493.75  4594.6  491.65
  4615.3  491.91  4634.3  490.78  4639.5  490.87  4679.2  488.22  4729.3  486.76
  4793.2  483.84  4833.0  482.80  4918.5  481.98  4984.2  481.57  4984.9  480.77
  4991.9  480.77  4992.6  481.57  5018.3  481.61  5129.1  484.79  5137.2  484.32
  5153.3  484.36  5169.3  485.02  5272.2  486.40  5321.4  486.15  5337.5  486.50
  5387.7  485.73  5424.4  486.28  5499.9  486.61  5505.6  486.04  5525.7  486.40
#Mann=6,-1,0
  4428.7     0.1       0  4918.5    0.16       0  4984.2    0.07       0
  4992.6    0.16       0  5018.3    0.07       0  5129.1     0.1       0
Bank Sta=4984.2,4992.6
Exp/Cntr=0.3,0.1

Type RM Length L Ch R = 1,6369,461,461,461
BEGIN DESCRIPTION:
UNT 001 in RCW 6.0
END DESCRIPTION:
XS GIS Cut Line= 3
      1992774.99     13496125.01      1993225.00     13495765.97
      1993375.82     13495511.96
#Sta/Elev= 30
  4433.4  494.55  4455.0  493.53  4483.9  493.22  4511.1  492.08  4554.3  491.33
  4583.1  489.49  4589.5  489.68  4625.3  487.45  4676.0  485.51  4703.2  483.97
  4740.1  483.59  4760.9  482.71  4810.5  482.28  4831.3  481.14  4853.7  480.58
  4984.0  479.32  4984.7  478.52  4991.7  478.52  4992.5  479.32  4993.6  479.33
  5012.2  479.85  5033.1  480.84  5097.3  482.30  5103.3  483.13  5155.8  484.39
  5171.4  484.66  5177.2  484.22  5192.8  484.56  5198.6  484.20  5304.5  485.89
#Mann=5,-1,0
  4433.4     0.1       0  4984.0    0.07       0  4992.5     0.1       0
  4993.6    0.07       0  5012.2     0.1       0
Bank Sta=4984,4992.5
Exp/Cntr=0.3,0.1

Type RM Length L Ch R = 1,5908,320,320,320
BEGIN DESCRIPTION:
UNT 001 in RCW 5.0
END DESCRIPTION:
XS GIS Cut Line= 3
      1993124.99     13496275.01      1993625.00     13495925.00
      1993874.10     13495565.76
#Sta/Elev= 30
  4406.7  492.37  4464.7  491.87  4500.4  490.96  4521.4  490.88  4536.2  490.22
  4542.3  490.58  4551.0  490.13  4557.1  490.20  4586.8  489.04  4607.7  488.72
  4673.1  486.72  4694.0  485.12  4783.5  482.09  4872.7  479.49  4969.6  477.32
  4970.4  476.52  4977.4  476.52  4978.1  477.32  5081.2  479.87  5110.9  481.37
  5125.8  481.98  5131.9  481.82  5146.7  482.62  5167.7  482.11  5182.5  482.60
  5224.4  482.61  5275.1  483.29  5355.5  483.32  5427.1  484.46  5454.2  484.34
#Mann=4,-1,0
  4406.7     0.1       0  4783.5    0.05       0  4969.6    0.03       0
  4978.1    0.05       0
Bank Sta=4969.6,4978.1
Exp/Cntr=0.3,0.1

Type RM Length L Ch R = 1,5588,269,269,269
BEGIN DESCRIPTION:
Mapping XS afdc66cb
END DESCRIPTION:
XS GIS Cut Line= 4
      1993314.22     13496409.53      1993616.27     13496380.88
      1993941.79     13496034.53      1993973.03     13495831.44
#Sta/Elev= 30
  4356.4  486.62  4387.3  485.85  4417.5  485.92  4447.6  485.08  4522.8  484.74
  4527.9  484.73  4563.2  483.12  4598.3  482.40  4659.8  481.82  4670.0  481.46
  4691.5  481.32  4698.3  481.61  4719.8  481.58  4769.1  480.81  4811.6  480.87
  4825.8  479.53  4841.6  479.08  4953.2  477.39  5019.8  477.06  5020.6  476.26
  5027.6  476.26  5028.3  477.06  5122.8  478.93  5154.9  479.21  5184.6  480.60
  5189.7  480.47  5205.5  481.65  5225.7  482.59  5276.3  482.07  5340.6  482.41
#Mann=5,-1,0
  4356.4    0.05       0  4522.8     0.1       0  4841.6    0.05       0
  5019.8    0.03       0  5028.3    0.05       0
Bank Sta=5019.8,5028.3
Exp/Cntr=0.3,0.1

Type RM Length L Ch R = 1,5319,195,195,195
BEGIN DESCRIPTION:
Mapping XS f3ff80ba
END DESCRIPTION:
XS GIS Cut Line= 4
      1993780.32     13496490.26      1993941.79     13496438.18
      1994100.64     13496198.59      1994129.29     13495873.07
#Sta/Elev= 30
  4556.9  483.65  4562.4  483.72  4572.3  483.04  4589.2  481.18  4621.2  480.12
  4629.9  480.12  4766.4  479.67  4781.0  479.32  4796.0  479.33  4838.4  478.46
  4910.3  476.61  4919.4  476.96  4925.4  476.87  4940.4  477.53  4946.4  477.43
  4955.5  476.51  4970.3  476.68  4976.5  476.30  4987.3  476.28  4988.0  475.48
  4995.0  475.48  4995.8  476.28  5027.7  476.86  5067.8  478.25  5108.0  478.48
  5158.2  478.40  5248.5  479.48  5258.6  479.41  5308.7  480.87  5340.8  481.40
#Mann=4,-1,0
  4556.9     0.1       0  4629.9    0.05       0  4987.3    0.03       0
  4995.8    0.05       0
Bank Sta=4987.3,4995.8
Exp/Cntr=0.3,0.1

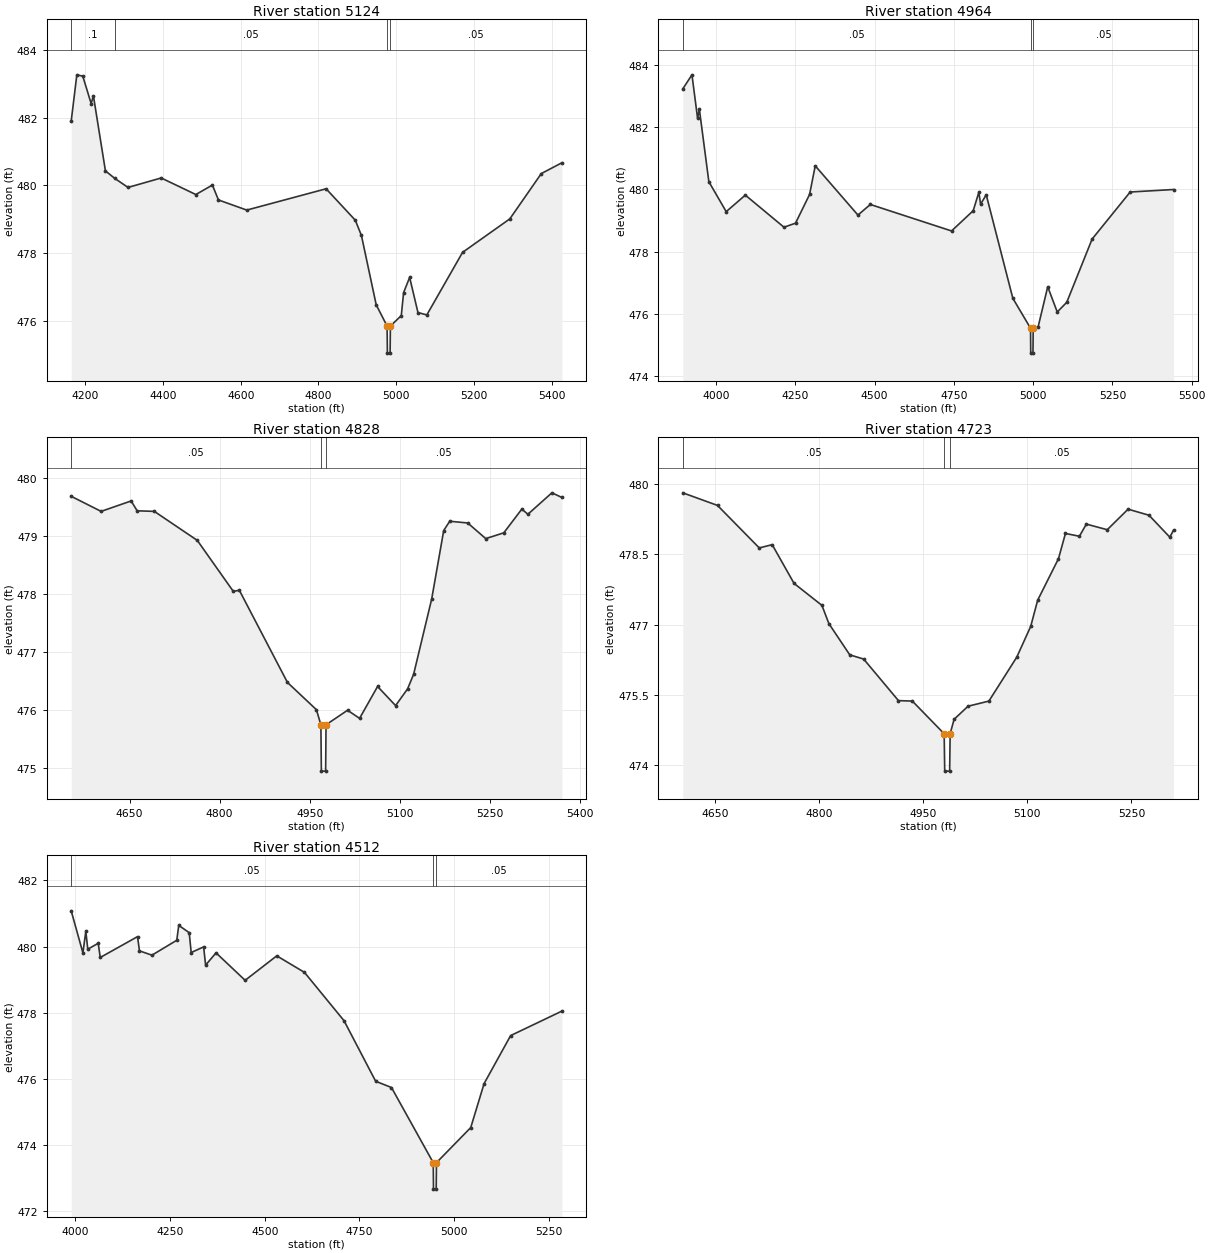
Type RM Length L Ch R = 1,5124,160,160,160
BEGIN DESCRIPTION:
Mapping XS 80342893
END DESCRIPTION:
XS GIS Cut Line= 4
      1993759.54     13496888.67      1994105.85     13496677.76
      1994303.77     13496172.55      1994254.29     13495862.65
#Sta/Elev= 30
  4164.1  481.90  4178.6  483.27  4193.9  483.23  4215.4  482.42  4221.2  482.65
  4252.1  480.43  4275.8  480.21  4310.2  479.94  4395.5  480.22  4484.6  479.73
  4527.2  480.01  4542.7  479.57  4615.5  479.27  4819.6  479.90  4894.7  478.97
  4910.4  478.52  4948.4  476.47  4976.4  475.84  4977.2  475.04  4984.2  475.04
  4984.9  475.84  5012.9  476.15  5018.9  476.83  5034.4  477.28  5055.8  476.24
  5078.6  476.17  5170.5  478.02  5292.0  479.01  5373.0  480.35  5426.0  480.67
#Mann=4,-1,0
  4164.1     0.1       0  4275.8    0.05       0  4976.4    0.03       0
  4984.9    0.05       0
Bank Sta=4976.4,4984.9
Exp/Cntr=0.3,0.1

Type RM Length L Ch R = 1,4964,136,136,136
BEGIN DESCRIPTION:
UNT 001 in RCW 4.0
END DESCRIPTION:
XS GIS Cut Line= 3
      1994019.93     13497300.11      1994426.16     13496383.49
      1994410.59     13495838.32
#Sta/Elev= 30
  3894.8  483.22  3923.7  483.67  3941.5  482.27  3947.0  482.57  3977.0  480.24
  4031.7  479.28  4092.1  479.81  4214.0  478.78  4250.4  478.91  4294.7  479.83
  4312.6  480.75  4447.3  479.17  4486.4  479.51  4742.6  478.66  4810.9  479.31
  4828.7  479.90  4834.2  479.52  4852.0  479.82  4935.9  476.50  4991.7  475.54
  4992.4  474.74  4999.4  474.74  5000.2  475.54  5015.9  475.59  5046.0  476.87
  5076.0  476.06  5106.0  476.37  5186.0  478.40  5306.1  479.91  5442.8  479.99
#Mann=3,-1,0
  3894.8    0.05       0  4991.7    0.03       0  5000.2    0.05       0
Bank Sta=4991.7,5000.2
Exp/Cntr=0.3,0.1

Type RM Length L Ch R = 1,4828,105,105,105
BEGIN DESCRIPTION:
Mapping XS 7abfa3b5
END DESCRIPTION:
XS GIS Cut Line= 2
      1994575.27     13496734.74      1994544.95     13495918.30
#Sta/Elev= 30
  4552.8  479.69  4602.6  479.43  4652.6  479.61  4662.6  479.44  4691.2  479.43
  4762.7  478.93  4822.7  478.05  4832.7  478.07  4912.8  476.48  4961.0  476.01
  4968.5  475.75  4969.3  474.95  4976.4  474.95  4977.1  475.75  5012.9  476.00
  5032.9  475.86  5062.9  476.41  5092.9  476.08  5112.9  476.37  5122.9  476.62
  5153.0  477.92  5173.0  479.10  5183.0  479.26  5213.0  479.23  5243.0  478.96
  5273.0  479.06  5303.1  479.47  5313.1  479.38  5353.1  479.75  5369.8  479.67
#Mann=3,-1,0
  4552.8    0.05       0  4968.5    0.03       0  4977.1    0.05       0
Bank Sta=4968.5,4977.1
Exp/Cntr=0.3,0.1

Type RM Length L Ch R = 1,4723,211,211,211
BEGIN DESCRIPTION:
Mapping XS e3f800a9
END DESCRIPTION:
XS GIS Cut Line= 2
      1994688.12     13496684.91      1994644.72     13495979.74
#Sta/Elev= 30
  4604.0  479.82  4654.0  479.55  4714.1  478.64  4732.7  478.71  4764.2  477.88
  4804.3  477.41  4814.3  477.02  4844.4  476.35  4864.4  476.26  4914.5  475.37
  4934.5  475.36  4980.3  474.66  4981.1  473.86  4988.2  473.86  4988.9  474.66
  4994.6  474.97  5014.7  475.25  5044.7  475.36  5084.8  476.30  5104.9  476.96
  5114.9  477.52  5144.9  478.41  5154.9  478.95  5175.0  478.89  5185.0  479.15
  5215.1  479.03  5245.1  479.47  5275.2  479.34  5305.2  478.87  5310.5  479.02
#Mann=3,-1,0
  4604.0    0.05       0  4980.3    0.04       0  4988.9    0.05       0
Bank Sta=4980.3,4988.9
Exp/Cntr=0.3,0.1

Type RM Length L Ch R = 1,4512,540,540,540
BEGIN DESCRIPTION:
UNT 001 in RCW 3.0
END DESCRIPTION:
XS GIS Cut Line= 3
      1994598.04     13497284.53      1994875.00     13496375.00
      1994858.47     13496029.66
#Sta/Elev= 30
  3988.7  481.08  4019.6  479.81  4027.3  480.46  4032.5  479.92  4060.1  480.10
  4065.4  479.67  4163.9  480.30  4169.1  479.87  4202.0  479.74  4267.6  480.19
  4272.9  480.64  4300.5  480.42  4305.7  479.82  4338.6  479.99  4343.8  479.44
  4371.4  479.81  4448.2  478.98  4531.8  479.72  4605.0  479.22  4709.5  477.76
  4793.1  475.93  4834.9  475.74  4945.2  473.47  4945.9  472.67  4953.0  472.67
  4953.8  473.47  5044.3  474.53  5079.6  475.86  5149.7  477.31  5285.2  478.05
#Mann=3,-1,0
  3988.7    0.05       0  4945.2   0.035       0  4953.8    0.05       0
Bank Sta=4945.2,4953.8
Exp/Cntr=0.3,0.1