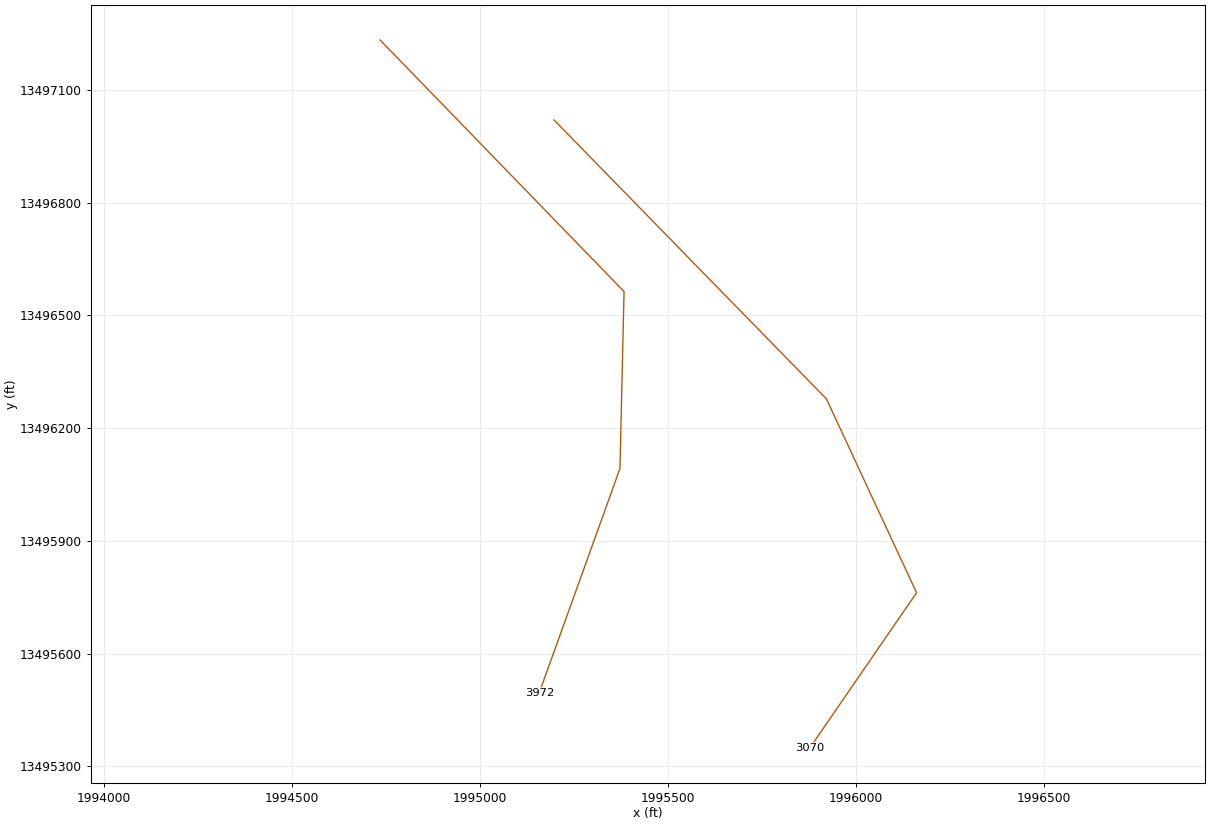
HEC-RAS study UNT 001 in RCW.prj: UNT 001 in RCW Base Level Engineering

--- UNT 001 in RCW.g01 (geometry) --- (continued)

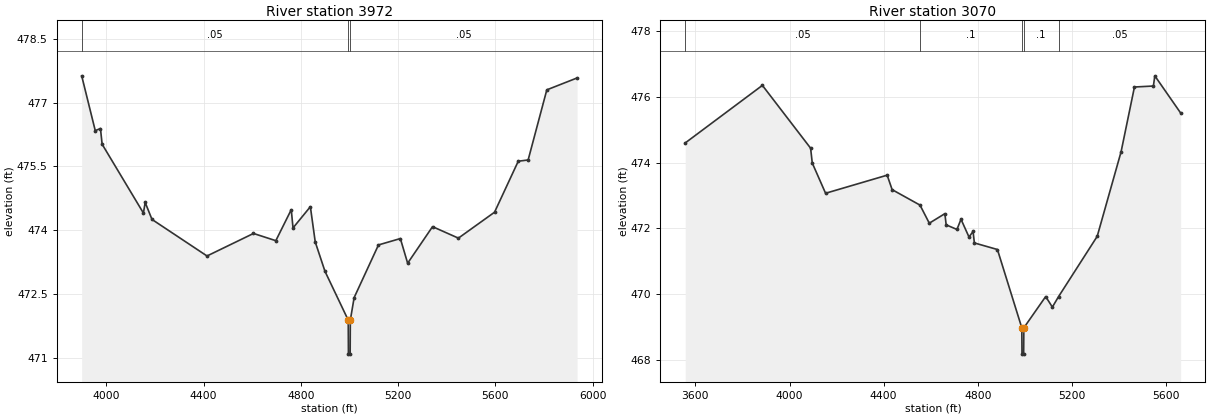
Type RM Length L Ch R = 1,3972,902,902,902
BEGIN DESCRIPTION:
UNT 001 in RCW 2.0
END DESCRIPTION:
XS GIS Cut Line= 4
      1994733.43     13497232.47      1995382.56     13496563.33
      1995371.71     13496092.41      1995156.86     13495495.61
#Sta/Elev= 30
  3898.9  477.63  3954.7  476.34  3976.1  476.39  3983.0  476.02  4152.8  474.40
  4160.0  474.65  4188.1  474.25  4414.4  473.39  4605.5  473.92  4697.4  473.75
  4760.9  474.48  4768.1  474.05  4839.5  474.55  4859.5  473.72  4899.5  473.03
  4995.2  471.88  4996.0  471.08  5003.1  471.08  5003.8  471.88  5019.5  472.41
  5119.6  473.65  5209.6  473.80  5239.6  473.22  5342.0  474.08  5448.3  473.81
  5597.0  474.42  5694.5  475.62  5735.2  475.65  5812.0  477.30  5936.5  477.58
#Mann=3,-1,0
  3898.9    0.05       0  4995.2    0.03       0  5003.8    0.05       0
Bank Sta=4995.2,5003.8
Exp/Cntr=0.3,0.1

Type RM Length L Ch R = 1,3070,0,0,0
BEGIN DESCRIPTION:
UNT 001 in RCW 1.0
END DESCRIPTION:
XS GIS Cut Line= 4
      1995196.15     13497019.75      1995920.95     13496277.59
      1996160.68     13495762.10      1995877.35     13495350.22
#Sta/Elev= 30
  3556.8  474.60  3884.7  476.35  4089.7  474.44  4096.7  473.99  4153.3  473.07
  4415.1  473.62  4436.2  473.18  4554.7  472.71  4594.2  472.16  4660.4  472.45
  4665.9  472.11  4711.7  471.97  4729.0  472.28  4762.9  471.74  4780.3  471.91
  4785.8  471.56  4883.8  471.36  4987.4  468.98  4988.2  468.18  4995.3  468.18
  4996.1  468.98  5088.9  469.93  5117.3  469.61  5143.8  469.93  5307.9  471.76
  5409.4  474.33  5466.2  476.30  5546.8  476.33  5552.8  476.64  5662.6  475.51
#Mann=5,-1,0
  3556.8    0.05       0  4554.7     0.1       0  4987.4    0.07       0
  4996.1     0.1       0  5143.8    0.05       0
Bank Sta=4987.4,4996.1
Exp/Cntr=0.3,0.1

Chan Stop Cuts=-1