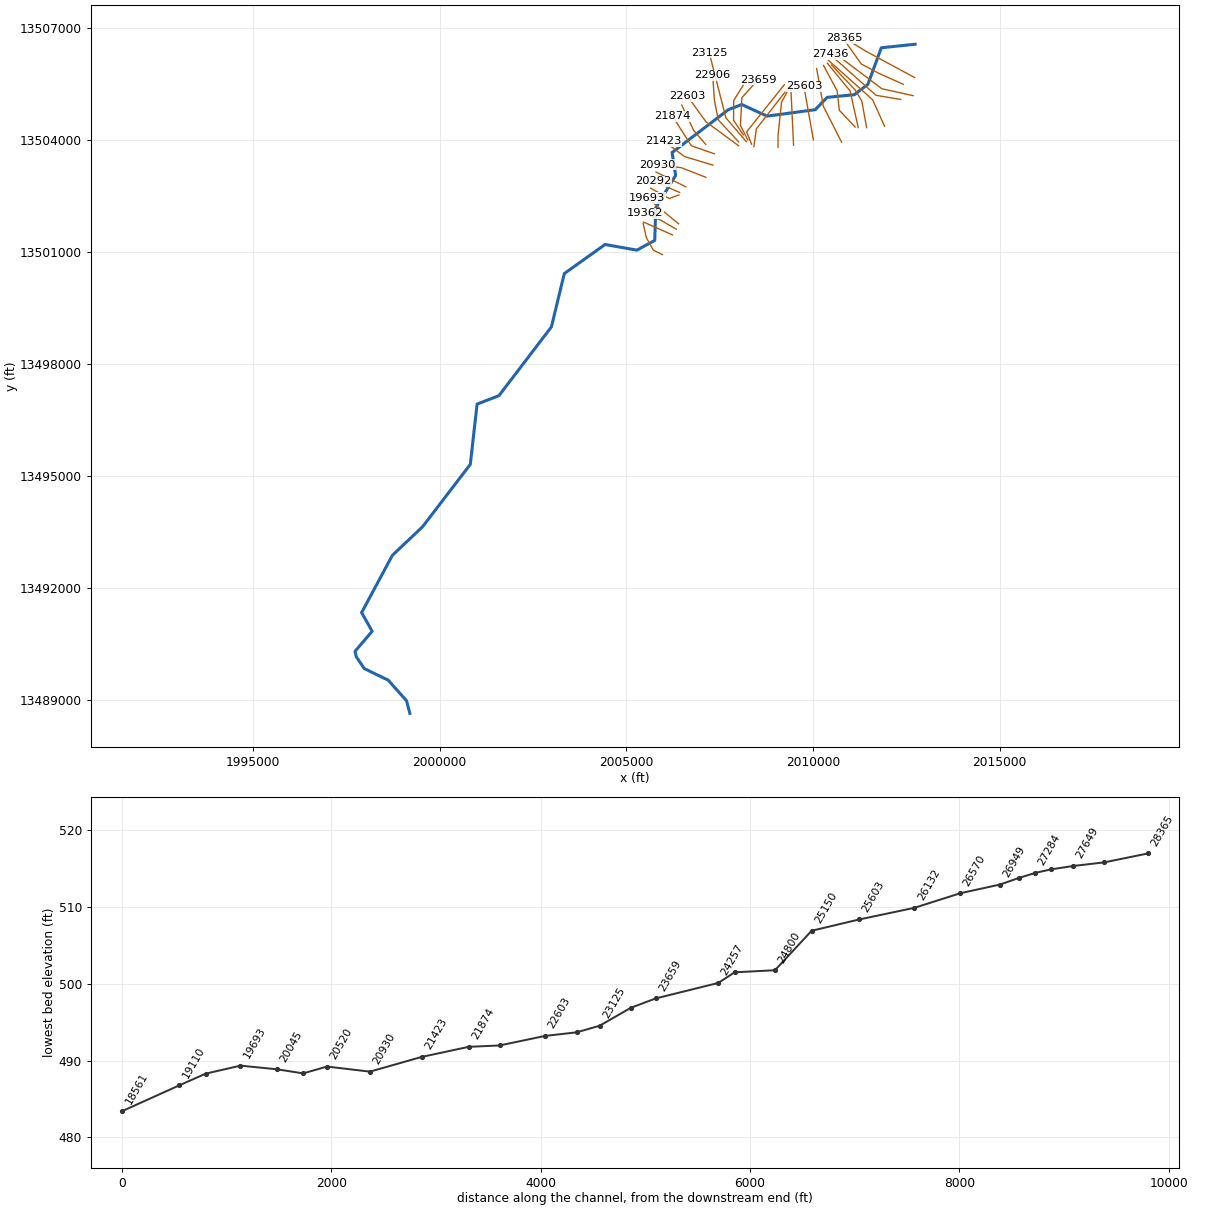
--- UNT 003 in RCW.prj (project) ---

Proj Title=UNT 003 in RCW Base Level Engineering
Current Plan=p01
Default Exp/Contr=0.3,0.1
English Units
Geom File=g01
Flow File=f01
Plan File=p01
Y Axis Title=Elevation
X Axis Title(PF)=Main Channel Distance
X Axis Title(XS)=Station
BEGIN DESCRIPTION:
UNT 003 in RCW
END DESCRIPTION:
DSS Export Rating Curves= 0
DSS Export Rating Curve Sorted= 0
DSS Export Volume Flow Curves= 0
DXF OffsetX= 0
DXF OffsetY= 0
DXF ScaleX= 1
DXF ScaleY= 10

--- UNT 003 in RCW.p01 (plan) ---

Plan Title=Multiple Run
Short Identifier=Multiple
Geom File=g01
Flow File=f01
Subcritical Flow
K Sum by GR= 0
Std Step Tol= 0.01
Critical Tol= 0.01
Num of Std Step Trials= 20
Max Error Tol= 0.3
Flow Tol Ratio= 0.001
Split Flow NTrial= 30
Split Flow Tol= 0.02
Split Flow Ratio= 0.02
Log Output Level= 0
Friction Slope Method= 1
Unsteady Friction Slope Method= 2
Unsteady Bridges Friction Slope Method= 1
Parabolic Critical Depth
Global Vel Dist=  1 , 1 , 1
Global Log Level= 0
CheckData=True
Encroach Param= -1, 0, 0, 0
BEGIN DESCRIPTION:
Multiple Run
END DESCRIPTION:

--- UNT 003 in RCW.f01 (steady flow) ---

Flow Title=Multiple
Program Version=5.05
Number of Profiles= 7
Profile Names=10-year,25-year,50-year,1pct_min,100-year,1pct_plu,500-year
River Rch & RM=UNT 003 in RCW,Reach-1         ,28365
     251     347     425     260     518    1034     782
River Rch & RM=UNT 003 in RCW,Reach-1         ,27128
     416     588     732     453     904    1804    1403
River Rch & RM=UNT 003 in RCW,Reach-1         ,25603
     416     588     732     453     904    1804    1403
River Rch & RM=UNT 003 in RCW,Reach-1         ,20520
     449     635     792     492     981    1957    1527
River Rch & RM=UNT 003 in RCW,Reach-1         ,19693
     533     757     947     588    1174    2342    1832
River Rch & RM=UNT 003 in RCW,Reach-1         ,18561
     533     757     947     588    1174    2342    1832
River Rch & RM=UNT 003 in RCW,Reach-1         ,12365
     747    1075    1356     849    1694    3380    2688
River Rch & RM=UNT 003 in RCW,Reach-1         ,10907
     747    1075    1356     849    1694    3380    2688
Boundary for River Rch & Prof#=UNT 003 in RCW,Reach-1         , 1
Up Type= 0
Dn Type= 3
Dn Slope=0.00201
Boundary for River Rch & Prof#=UNT 003 in RCW,Reach-1         , 2
Up Type= 0
Dn Type= 3
Dn Slope=0.00201
Boundary for River Rch & Prof#=UNT 003 in RCW,Reach-1         , 3
Up Type= 0
Dn Type= 3
Dn Slope=0.00201
Boundary for River Rch & Prof#=UNT 003 in RCW,Reach-1         , 4
Up Type= 0
Dn Type= 3
Dn Slope=0.00201
Boundary for River Rch & Prof#=UNT 003 in RCW,Reach-1         , 5
Up Type= 0
Dn Type= 3
Dn Slope=0.00201
Boundary for River Rch & Prof#=UNT 003 in RCW,Reach-1         , 6
Up Type= 0
Dn Type= 3
Dn Slope=0.00201
Boundary for River Rch & Prof#=UNT 003 in RCW,Reach-1         , 7
Up Type= 0
Dn Type= 3
Dn Slope=0.00201
DSS Import GetInterval= 0
DSS Import GetPeak= 0
DSS Import FillOption= 0

--- UNT 003 in RCW.g01 (geometry) ---

Geom Title=Existing Conditions

River Reach=UNT 003 in RCW,Reach-1
Reach XY= 30
      2012735.80     13506569.54      2011830.80     13506474.54
      2011470.80     13505494.54      2011107.13     13505217.23
      2010377.96     13505145.61      2010060.92     13504816.46
      2008772.17     13504643.26      2008090.80     13504954.54
      2007730.80     13504814.54      2006226.25     13503669.39
      2006320.80     13503054.54      2005790.06     13502194.13
      2005760.80     13501314.54      2005282.24     13501053.50
      2004430.80     13501204.54      2003338.29     13500425.38
      2002993.23     13498997.43      2001586.98     13497154.98
      2001002.13     13496929.29      2000820.80     13495314.54
      1999539.24     13493641.10      1998733.23     13492878.43
      1997908.92     13491344.40      1998190.80     13490844.54
      1997730.80     13490304.54      1997770.80     13490154.54
      1997980.80     13489844.54      1998620.80     13489534.54
      1999110.80     13488984.54      1999200.80     13488644.54

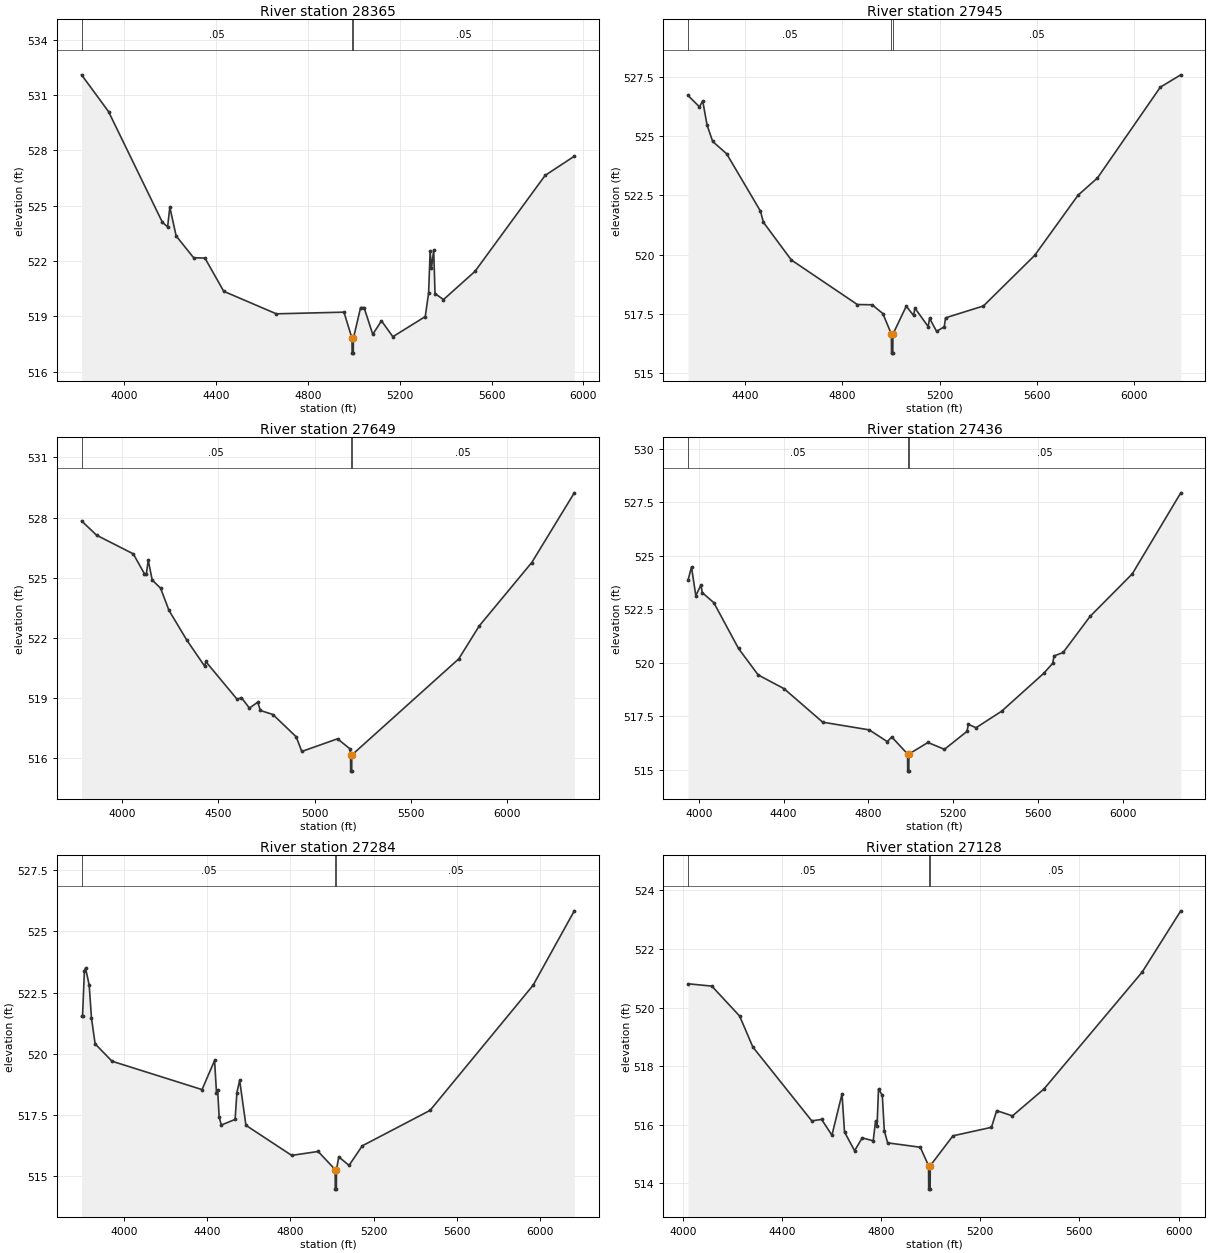
Type RM Length L Ch R = 1,28365,420,420,420
BEGIN DESCRIPTION:
UNT 003 in RCW 41.0
END DESCRIPTION:
XS GIS Cut Line= 3
      2012724.98     13505675.01      2011415.46     13506383.49
      2010852.96     13506727.24
#Sta/Elev= 30
  3812.8  532.09  3930.3  530.10  4165.2  524.10  4188.0  523.85  4197.6  524.92
  4225.2  523.36  4301.3  522.18  4350.7  522.16  4432.6  520.36  4661.9  519.14
  4956.8  519.23  4991.8  517.81  4992.3  517.01  4997.3  517.01  4997.8  517.81
  5029.3  519.48  5044.3  519.48  5082.3  518.03  5120.3  518.76  5169.9  517.90
  5311.1  518.99  5325.7  520.27  5332.4  522.52  5338.3  521.62  5347.9  522.60
  5353.7  520.24  5390.5  519.91  5527.9  521.44  5833.7  526.64  5960.9  527.68
#Mann=3,-1,0
  3812.8    0.05       0  4991.8    0.03       0  4997.8    0.05       0
Bank Sta=4991.8,4997.8
Exp/Cntr=0.3,0.1

Type RM Length L Ch R = 1,27945,296,296,296
BEGIN DESCRIPTION:
Mapping XS 32038eca
END DESCRIPTION:
XS GIS Cut Line= 4
      2012417.78     13505496.37      2011775.40     13505784.57
      2011292.76     13506041.52      2010844.86     13506673.43
#Sta/Elev= 30
  4166.1  526.71  4213.0  526.23  4226.6  526.48  4244.3  525.46  4267.5  524.77
  4324.8  524.25  4463.9  521.83  4476.0  521.36  4590.7  519.77  4862.1  517.89
  4922.9  517.88  4966.9  517.51  5002.1  516.64  5002.6  515.84  5007.8  515.84
  5008.3  516.64  5063.2  517.82  5093.0  517.43  5098.7  517.74  5153.3  516.96
  5158.9  517.31  5187.8  516.76  5219.2  516.95  5224.8  517.33  5380.4  517.83
  5590.7  519.96  5769.1  522.50  5849.1  523.23  6107.5  527.06  6191.5  527.58
#Mann=3,-1,0
  4166.1    0.05       0  5002.1    0.03       0  5008.3    0.05       0
Bank Sta=5002.1,5008.3
Exp/Cntr=0.3,0.1

Type RM Length L Ch R = 1,27649,213,213,213
BEGIN DESCRIPTION:
UNT 003 in RCW 40.0
END DESCRIPTION:
XS GIS Cut Line= 3
      2012682.87     13505192.51      2011846.01     13505376.54
      2010489.77     13506399.79
#Sta/Elev= 30
  3791.0  527.83  3869.0  527.12  4059.4  526.19  4116.5  525.21  4126.7  525.17
  4136.9  525.87  4157.4  524.89  4200.9  524.48  4244.7  523.37  4337.3  521.89
  4430.0  520.59  4435.1  520.83  4597.7  518.95  4620.3  519.03  4661.6  518.51
  4704.4  518.80  4719.0  518.39  4783.5  518.19  4904.3  517.08  4933.4  516.35
  5118.7  516.98  5183.2  516.48  5186.4  516.17  5186.9  515.37  5192.1  515.37
  5192.6  516.17  5747.3  520.96  5853.5  522.60  6126.2  525.76  6346.8  529.23
#Mann=3,-1,0
  3791.0    0.05       0  5186.4    0.03       0  5192.6    0.05       0
Bank Sta=5186.4,5192.6
Exp/Cntr=0.3,0.1

Type RM Length L Ch R = 1,27436,152,152,152
BEGIN DESCRIPTION:
Mapping XS 09270181
END DESCRIPTION:
XS GIS Cut Line= 3
      2012351.20     13505090.09      2011688.03     13505201.20
      2010455.35     13506298.45
#Sta/Elev= 30
  3949.3  523.86  3965.7  524.48  3986.0  523.14  4010.3  523.64  4016.4  523.28
  4071.0  522.81  4187.3  520.67  4280.0  519.43  4401.7  518.79  4584.2  517.22
  4803.4  516.86  4888.7  516.31  4909.6  516.53  4984.3  515.73  4984.8  514.93
  4990.0  514.93  4990.5  515.73  5080.2  516.27  5158.0  515.95  5264.2  516.79
  5270.9  517.12  5306.8  516.96  5427.2  517.73  5625.4  519.50  5668.0  519.97
  5674.7  520.32  5717.4  520.48  5844.5  522.17  6043.5  524.16  6272.0  527.95
#Mann=3,-1,0
  3949.3    0.05       0  4984.3    0.03       0  4990.5    0.05       0
Bank Sta=4984.3,4990.5
Exp/Cntr=0.3,0.1

Type RM Length L Ch R = 1,27284,156,156,156
BEGIN DESCRIPTION:
Mapping XS 233aee2e
END DESCRIPTION:
XS GIS Cut Line= 3
      2011917.19     13504371.35      2011597.75     13505083.14
      2010411.46     13506141.09
#Sta/Elev= 30
  3795.7  521.52  3800.4  521.52  3809.2  523.37  3814.7  523.50  3832.4  522.81
  3843.5  521.45  3861.0  520.40  3942.2  519.69  4375.1  518.53  4435.4  519.72
  4444.6  518.41  4450.1  518.52  4457.4  517.41  4467.8  517.08  4534.1  517.31
  4542.8  518.41  4556.0  518.91  4586.2  517.07  4806.1  515.84  4933.2  516.00
  5015.4  515.26  5015.9  514.46  5021.1  514.46  5021.6  515.26  5032.7  515.78
  5082.0  515.43  5145.6  516.23  5471.6  517.68  5967.4  522.80  6165.4  525.84
#Mann=3,-1,0
  3795.7    0.05       0  5015.4    0.03       0  5021.6    0.05       0
Bank Sta=5015.4,5021.6
Exp/Cntr=0.3,0.1

Type RM Length L Ch R = 1,27128,179,179,179
BEGIN DESCRIPTION:
Mapping XS 065b9cc1
END DESCRIPTION:
XS GIS Cut Line= 4
      2011436.82     13504333.69      2011306.60     13505052.48
      2011129.52     13505344.15      2010500.07     13506010.02
#Sta/Elev= 30
  4021.1  520.81  4117.2  520.73  4229.2  519.71  4282.7  518.65  4520.4  516.13
  4560.1  516.18  4601.7  515.64  4642.4  517.05  4652.5  515.75  4693.2  515.11
  4723.7  515.55  4768.2  515.45  4777.8  516.13  4783.7  515.95  4789.6  517.22
  4805.0  517.00  4813.0  515.80  4826.4  515.38  4958.1  515.23  4991.6  514.60
  4992.1  513.80  4997.9  513.80  4998.4  514.60  5089.9  515.62  5245.3  515.91
  5266.4  516.48  5329.9  516.30  5457.3  517.22  5853.4  521.21  6009.1  523.30
#Mann=3,-1,0
  4021.1    0.05       0  4991.6    0.03       0  4998.4    0.05       0
Bank Sta=4991.6,4998.4
Exp/Cntr=0.3,0.1

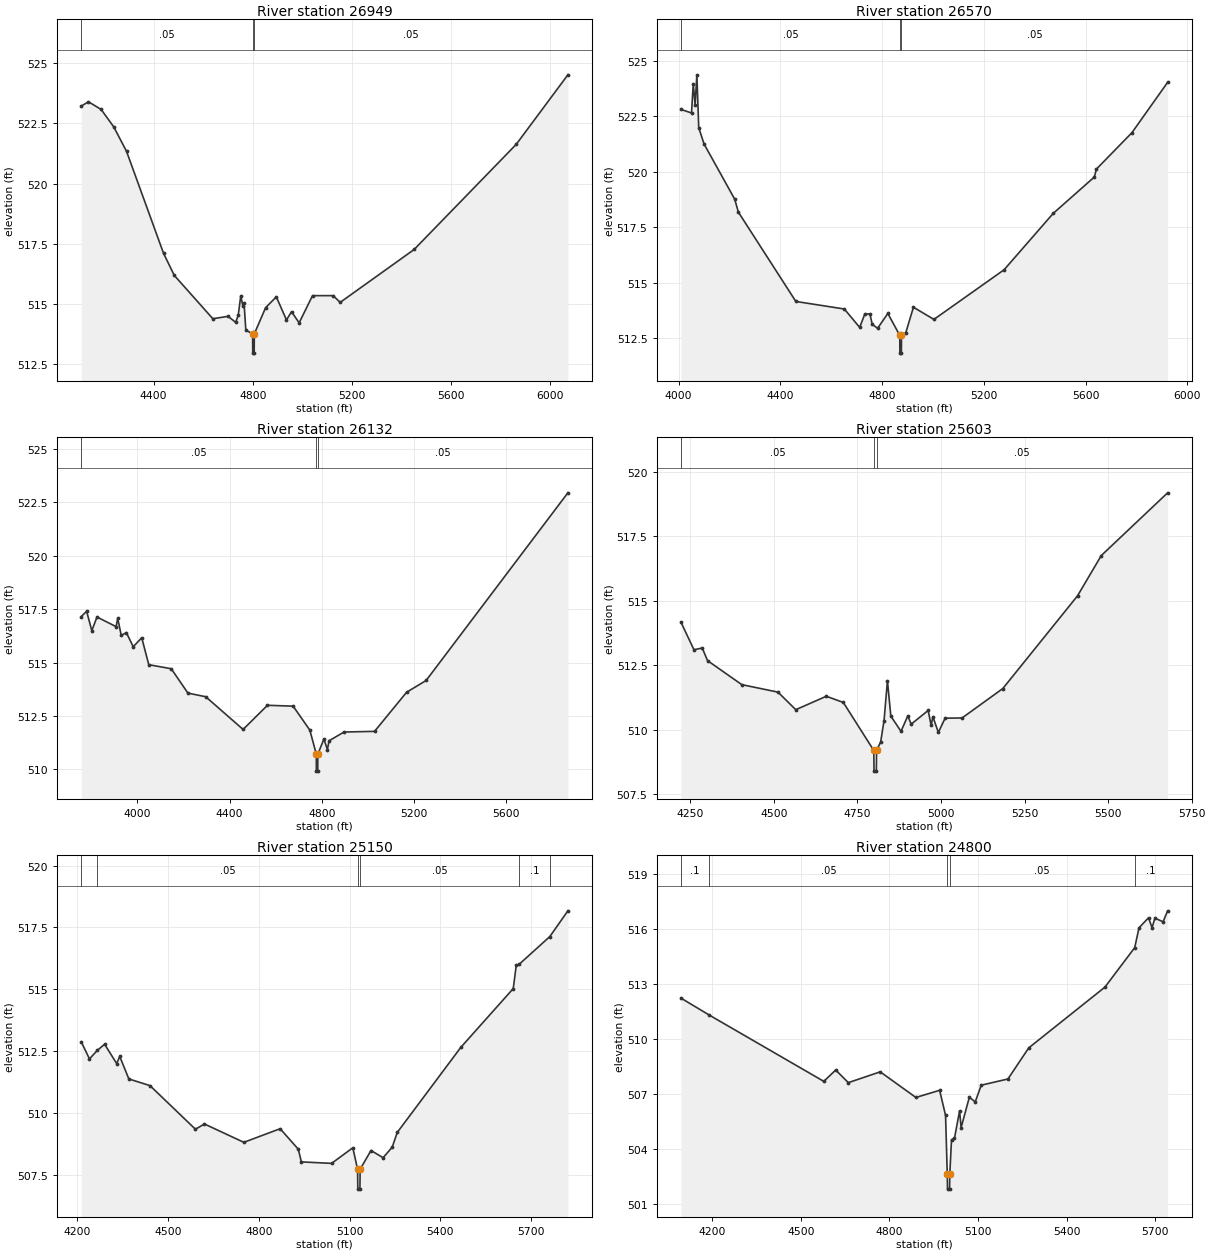
Type RM Length L Ch R = 1,26949,379,379,379
BEGIN DESCRIPTION:
Mapping XS 7bd9e34b
END DESCRIPTION:
XS GIS Cut Line= 3
      2011212.33     13504336.64      2010993.58     13505319.25
      2010385.92     13506058.87
#Sta/Elev= 30
  4107.8  523.22  4136.9  523.40  4188.1  523.08  4239.3  522.35  4290.5  521.34
  4439.9  517.10  4483.4  516.18  4638.9  514.38  4700.3  514.48  4731.1  514.23
  4741.3  514.52  4751.5  515.33  4759.7  514.93  4764.9  515.02  4772.0  513.91
  4799.4  513.75  4799.9  512.95  4805.7  512.95  4806.2  513.75  4851.9  514.84
  4895.0  515.29  4936.0  514.33  4956.4  514.67  4987.2  514.21  5041.2  515.34
  5124.2  515.34  5152.9  515.06  5451.4  517.26  5863.3  521.63  6071.7  524.52
#Mann=3,-1,0
  4107.8    0.05       0  4799.4    0.03       0  4806.2    0.05       0
Bank Sta=4799.4,4806.2
Exp/Cntr=0.3,0.1

Type RM Length L Ch R = 1,26570,438,438,438
BEGIN DESCRIPTION:
Mapping XS c0870570
END DESCRIPTION:
XS GIS Cut Line= 4
      2011129.02     13504350.47      2010705.39     13504801.89
      2010646.36     13505322.72      2010282.67     13506001.61
#Sta/Elev= 30
  4009.0  522.81  4050.5  522.65  4057.3  523.97  4064.6  523.02  4071.5  524.37
  4078.8  521.99  4099.8  521.25  4220.4  518.76  4234.6  518.18  4460.7  514.15
  4651.3  513.81  4711.7  512.98  4731.8  513.58  4752.0  513.59  4760.9  513.12
  4782.2  512.94  4822.4  513.61  4869.3  512.62  4869.8  511.82  4875.6  511.82
  4876.1  512.62  4892.9  512.74  4923.1  513.89  5003.6  513.34  5279.6  515.58
  5472.5  518.12  5634.3  519.76  5642.6  520.12  5782.1  521.76  5922.4  524.03
#Mann=3,-1,0
  4009.0    0.05       0  4869.3   0.035       0  4876.1    0.05       0
Bank Sta=4869.3,4876.1
Exp/Cntr=0.3,0.1

Type RM Length L Ch R = 1,26132,529,529,529
BEGIN DESCRIPTION:
Mapping XS 18bf6acc
END DESCRIPTION:
XS GIS Cut Line= 3
      2010767.90     13503944.22      2010278.30     13504906.06
      2010097.75     13505919.93
#Sta/Elev= 30
  3757.3  517.15  3780.6  517.40  3803.1  516.49  3825.5  517.13  3908.3  516.68
  3915.3  517.07  3930.6  516.27  3952.8  516.40  3982.6  515.74  4019.5  516.16
  4049.9  514.90  4147.4  514.71  4219.7  513.57  4296.8  513.40  4458.8  511.87
  4564.4  513.00  4675.6  512.96  4748.0  511.84  4775.9  510.72  4776.4  509.92
  4782.2  509.92  4782.7  510.72  4809.1  511.42  4824.2  510.93  4831.3  511.34
  4896.4  511.75  5028.5  511.78  5167.4  513.61  5252.0  514.16  5866.4  522.94
#Mann=3,-1,0
  3757.3    0.05       0  4775.9   0.035       0  4782.7    0.05       0
Bank Sta=4775.9,4782.7
Exp/Cntr=0.3,0.1

Type RM Length L Ch R = 1,25603,453,453,453
BEGIN DESCRIPTION:
Mapping XS d2615aab
END DESCRIPTION:
XS GIS Cut Line= 2
      2010010.95     13504006.72      2009757.54     13505440.39
#Sta/Elev= 30
  4222.1  514.17  4261.0  513.10  4285.7  513.17  4301.6  512.68  4404.1  511.75
  4512.3  511.46  4565.6  510.78  4657.0  511.30  4707.8  511.06  4799.0  509.20
  4799.7  508.40  4806.6  508.40  4807.3  509.20  4819.5  509.53  4829.7  510.36
  4839.8  511.90  4850.0  510.53  4880.4  509.94  4900.7  510.54  4910.9  510.22
  4961.7  510.75  4970.6  510.17  4975.7  510.51  4992.1  509.90  5012.4  510.45
  5063.2  510.46  5185.1  511.60  5408.5  515.19  5479.6  516.75  5678.0  519.18
#Mann=3,-1,0
  4222.1    0.05       0  4799.0    0.03       0  4807.3    0.05       0
Bank Sta=4799,4807.3
Exp/Cntr=0.3,0.1

Type RM Length L Ch R = 1,25150,350,350,350
BEGIN DESCRIPTION:
Mapping XS 32325611
END DESCRIPTION:
XS GIS Cut Line= 2
      2009479.69     13503867.83      2009403.30     13505475.51
#Sta/Elev= 30
  4212.4  512.88  4239.6  512.19  4266.0  512.54  4289.7  512.78  4329.7  512.00
  4339.7  512.29  4369.8  511.38  4439.8  511.11  4590.0  509.35  4620.0  509.56
  4750.2  508.82  4870.3  509.37  4930.4  508.54  4940.4  508.03  5040.5  507.97
  5110.6  508.60  5126.4  507.73  5127.1  506.93  5134.1  506.93  5134.8  507.73
  5170.7  508.49  5210.7  508.20  5240.7  508.62  5257.6  509.22  5468.1  512.66
  5641.2  515.03  5651.2  515.97  5661.6  516.02  5762.2  517.13  5821.9  518.17
#Mann=6,-1,0
  4212.4     0.1       0  4266.0    0.05       0  5126.4    0.03       0
  5134.8    0.05       0  5661.6     0.1       0  5762.2    0.05       0
Bank Sta=5126.4,5134.8
Exp/Cntr=0.3,0.1

Type RM Length L Ch R = 1,24800,385,385,385
BEGIN DESCRIPTION:
Mapping XS 80301b74
END DESCRIPTION:
XS GIS Cut Line= 4
      2009063.59     13503812.31      2009063.59     13504124.85
      2009157.34     13505013.74      2009368.43     13505401.32
#Sta/Elev= 30
  4094.5  512.23  4190.6  511.30  4578.1  507.68  4618.4  508.30  4661.2  507.61
  4769.2  508.20  4889.9  506.80  4970.3  507.19  4990.4  505.82  4996.2  502.59
  4997.0  501.79  5004.0  501.79  5004.7  502.59  5010.5  504.49  5020.6  504.57
  5037.9  506.07  5043.0  505.15  5070.9  506.81  5091.0  506.56  5111.1  507.47
  5201.6  507.81  5272.0  509.51  5530.0  512.83  5630.9  514.99  5645.3  516.07
  5677.6  516.62  5689.5  516.08  5699.4  516.60  5726.9  516.40  5742.2  517.00
#Mann=5,-1,0
  4094.5     0.1       0  4190.6    0.05       0  4996.2    0.03       0
  5004.7    0.05       0  5630.9     0.1       0
Bank Sta=4996.2,5004.7
Exp/Cntr=0.3,0.1

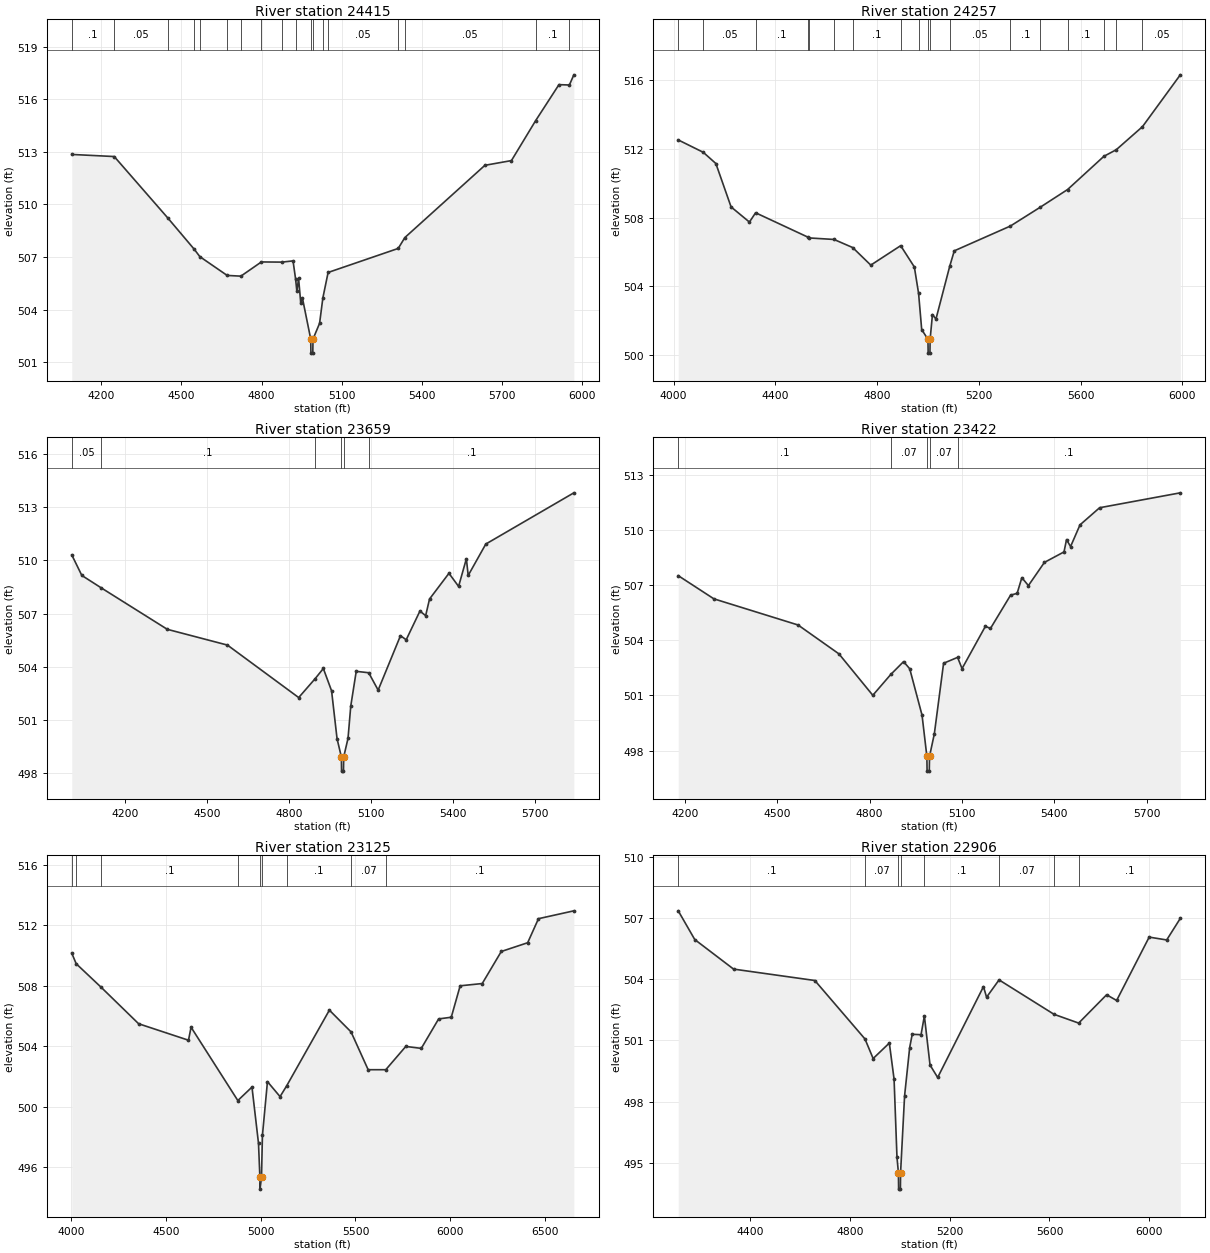
Type RM Length L Ch R = 1,24415,158,158,158
BEGIN DESCRIPTION:
UNT 003 in RCW 33.0
END DESCRIPTION:
XS GIS Cut Line= 3
      2008417.20     13503829.71      2008483.16     13504301.89
      2009347.75     13505409.53
#Sta/Elev= 30
  4088.8  512.85  4248.0  512.73  4448.0  509.24  4548.0  507.44  4569.0  507.02
  4671.3  505.95  4722.7  505.91  4799.5  506.72  4876.3  506.71  4918.2  506.78
  4927.8  505.74  4932.6  505.04  4939.0  505.78  4947.1  504.37  4953.5  504.65
  4984.5  502.32  4985.2  501.52  4992.2  501.52  4993.0  502.32  5017.7  503.22
  5030.0  504.67  5049.6  506.12  5312.4  507.49  5337.3  508.11  5637.3  512.23
  5736.8  512.50  5827.6  514.78  5914.9  516.83  5954.0  516.81  5970.7  517.39
#Mann=18,-1,0
  4088.8     0.1       0  4248.0    0.05       0  4448.0     0.1       0
  4548.0    0.08       0  4569.0     0.1       0  4671.3    0.05       0
  4722.7     0.1       0  4799.5    0.08       0  4876.3     0.1       0
  4927.8    0.05       0  4984.5    0.04       0  4993.0    0.05       0
  5030.0     0.1       0  5049.6    0.05       0  5312.4    0.08       0
  5337.3    0.05       0  5827.6     0.1       0  5954.0    0.05       0
Bank Sta=4984.5,4993
Exp/Cntr=0.3,0.1

Type RM Length L Ch R = 1,24257,598,598,598
BEGIN DESCRIPTION:
UNT 003 in RCW 32.0
END DESCRIPTION:
XS GIS Cut Line= 3
      2008354.70     13503892.15      2008222.75     13504222.03
      2009233.15     13505485.90
#Sta/Elev= 30
  4018.2  512.51  4116.7  511.79  4166.1  511.14  4225.9  508.62  4298.0  507.74
  4322.3  508.28  4528.6  506.86  4531.6  506.82  4630.6  506.73  4703.9  506.26
  4775.0  505.24  4892.5  506.37  4946.3  505.13  4962.9  503.60  4975.1  501.50
  4999.7  500.93  5000.5  500.13  5007.5  500.13  5008.2  500.93  5017.4  502.37
  5031.2  502.11  5085.2  505.17  5103.2  506.07  5323.8  507.51  5441.9  508.61
  5548.6  509.63  5691.4  511.56  5739.8  511.94  5842.9  513.28  5991.6  516.29
#Mann=18,-1,0
  4018.2     0.1       0  4116.7    0.05       0  4322.3     0.1       0
  4528.6    0.05       0  4531.6     0.1       0  4630.6    0.05       0
  4703.9     0.1       0  4892.5    0.08       0  4962.9    0.07       0
  4999.7    0.07       0  5008.2    0.07       0  5085.2    0.05       0
  5323.8     0.1       0  5441.9    0.05       0  5548.6     0.1       0
  5691.4    0.08       0  5739.8     0.1       0  5842.9    0.05       0
Bank Sta=4999.7,5008.2
Exp/Cntr=0.3,0.1

Type RM Length L Ch R = 1,23659,237,237,237
BEGIN DESCRIPTION:
Mapping XS e7f4a52b
END DESCRIPTION:
XS GIS Cut Line= 4
      2008254.58     13504003.29      2008056.65     13504395.68
      2008094.84     13505135.27      2008531.18     13505623.55
#Sta/Elev= 30
  4006.5  510.31  4043.2  509.15  4113.0  508.46  4355.6  506.11  4575.5  505.22
  4835.8  502.26  4896.2  503.33  4925.9  503.90  4956.0  502.64  4976.0  499.94
  4991.8  498.91  4992.5  498.11  4999.5  498.11  5000.3  498.91  5016.1  499.96
  5026.1  501.78  5046.1  503.74  5091.6  503.66  5126.2  502.68  5207.8  505.75
  5228.7  505.52  5278.9  507.14  5299.8  506.88  5314.0  507.82  5385.0  509.27
  5420.2  508.53  5448.6  510.09  5455.3  509.15  5519.6  510.92  5841.4  513.81
#Mann=6,-1,0
  4006.5    0.05       0  4113.0     0.1       0  4896.2    0.07       0
  4991.8    0.07       0  5000.3    0.07       0  5091.6     0.1       0
Bank Sta=4991.8,5000.3
Exp/Cntr=0.3,0.1

Type RM Length L Ch R = 1,23422,297,297,297
BEGIN DESCRIPTION:
Mapping XS cb24e8c1
END DESCRIPTION:
XS GIS Cut Line= 4
      2008133.01     13504141.69      2007872.60     13504532.30
      2007876.94     13505061.81      2008210.57     13505599.07
#Sta/Elev= 30
  4178.3  507.51  4294.2  506.25  4567.6  504.83  4700.5  503.26  4810.5  501.01
  4868.8  502.14  4910.5  502.84  4930.5  502.45  4970.5  499.93  4986.2  497.69
  4986.9  496.89  4994.0  496.89  4994.8  497.69  5010.5  498.92  5040.5  502.75
  5086.0  503.07  5100.5  502.46  5176.4  504.76  5192.8  504.64  5258.2  506.45
  5279.5  506.55  5294.8  507.40  5316.1  506.97  5368.1  508.23  5431.8  508.80
  5440.0  509.47  5453.1  509.09  5483.8  510.27  5547.5  511.20  5809.7  512.01
#Mann=5,-1,0
  4178.3     0.1       0  4868.8    0.07       0  4986.2    0.07       0
  4994.8    0.07       0  5086.0     0.1       0
Bank Sta=4986.2,4994.8
Exp/Cntr=0.3,0.1

Type RM Length L Ch R = 1,23125,219,219,219
BEGIN DESCRIPTION:
UNT 003 in RCW 31.0
END DESCRIPTION:
XS GIS Cut Line= 3
      2008215.81     13503958.14      2007667.19     13504597.03
      2007219.63     13506345.64
#Sta/Elev= 30
  4004.4  510.17  4027.7  509.47  4159.5  507.91  4356.9  505.50  4619.8  504.41
  4633.4  505.27  4879.9  500.42  4954.5  501.31  4988.9  497.59  4996.2  495.36
  4996.9  494.56  5004.8  495.36  5009.6  498.11  5036.1  501.67  5102.5  500.68
  5137.3  501.39  5362.6  506.40  5476.9  504.96  5567.0  502.46  5660.0  502.46
  5765.5  504.00  5847.1  503.87  5938.6  505.82  6005.2  505.93  6052.1  508.01
  6168.5  508.16  6268.9  510.28  6408.1  510.86  6465.0  512.45  6651.5  512.97
#Mann=9,-1,0
  4004.4     0.1       0  4027.7    0.08       0  4159.5     0.1       0
  4879.9    0.07       0  4996.2    0.07       0  5004.8    0.07       0
  5137.3     0.1       0  5476.9    0.07       0  5660.0     0.1       0
Bank Sta=4996.2,5004.8
Exp/Cntr=0.3,0.1

Type RM Length L Ch R = 1,22906,303,303,303
BEGIN DESCRIPTION:
Mapping XS 1c30e9ea
END DESCRIPTION:
XS GIS Cut Line= 4
      2008008.05     13503954.70      2007462.90     13504541.52
      2007358.73     13505072.77      2007313.59     13505739.41
#Sta/Elev= 30
  4113.4  507.36  4179.6  505.95  4335.0  504.50  4660.4  503.94  4861.2  501.07
  4893.9  500.11  4958.7  500.87  4977.7  499.10  4989.3  495.27  4995.1  494.50
  4995.9  493.70  5003.0  493.70  5003.7  494.50  5019.8  498.28  5040.2  500.65
  5050.4  501.30  5085.7  501.28  5099.0  502.20  5121.7  499.79  5152.3  499.18
  5335.7  503.64  5348.1  503.12  5398.1  503.97  5618.3  502.28  5716.9  501.85
  5828.8  503.24  5868.9  502.96  5999.2  506.07  6069.4  505.93  6123.9  506.99
#Mann=8,-1,0
  4113.4     0.1       0  4861.2    0.07       0  4995.1    0.07       0
  5003.7    0.07       0  5099.0     0.1       0  5398.1    0.07       0
  5618.3    0.12       0  5716.9     0.1       0
Bank Sta=4995.1,5003.7
Exp/Cntr=0.3,0.1

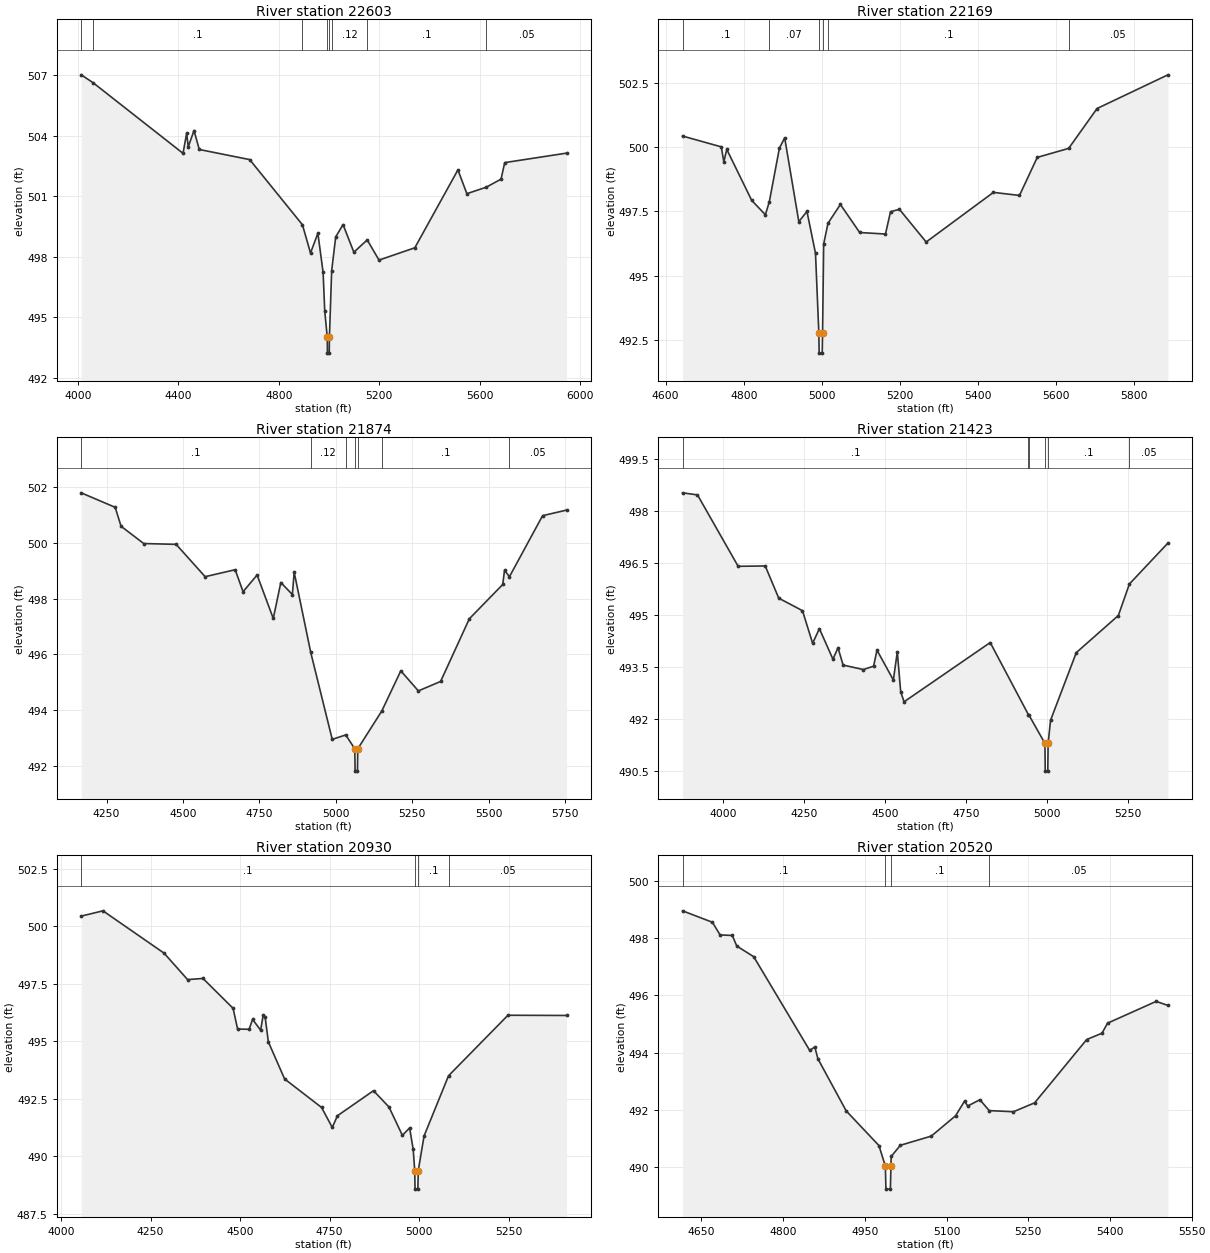
Type RM Length L Ch R = 1,22603,434,434,434
BEGIN DESCRIPTION:
UNT 003 in RCW 30.0
END DESCRIPTION:
XS GIS Cut Line= 3
      2008007.46     13503850.51      2007135.94     13504489.39
      2006636.07     13505180.19
#Sta/Elev= 30
  4012.4  507.02  4059.7  506.63  4418.0  503.13  4432.6  504.13  4438.8  503.45
  4461.8  504.26  4482.8  503.32  4683.5  502.82  4893.7  499.59  4925.8  498.19
  4955.2  499.17  4976.0  497.23  4982.6  495.30  4992.5  494.03  4993.3  493.23
  5000.4  493.23  5001.2  494.03  5010.1  497.32  5026.2  498.99  5055.5  499.60
  5098.5  498.23  5151.7  498.84  5198.7  497.84  5341.3  498.45  5513.0  502.31
  5548.6  501.13  5625.4  501.45  5684.7  501.85  5699.4  502.67  5945.7  503.14
#Mann=8,-1,0
  4012.4    0.05       0  4059.7     0.1       0  4893.7    0.07       0
  4992.5    0.07       0  5001.2    0.07       0  5010.1    0.12       0
  5151.7     0.1       0  5625.4    0.05       0
Bank Sta=4992.5,5001.2
Exp/Cntr=0.3,0.1

Type RM Length L Ch R = 1,22169,295,295,295
BEGIN DESCRIPTION:
Mapping XS 1ae94abf
END DESCRIPTION:
XS GIS Cut Line= 3
      2007126.39     13503886.96      2006806.08     13504259.36
      2006485.76     13504939.06
#Sta/Elev= 30
  4643.2  500.43  4742.3  500.01  4748.9  499.43  4756.5  499.91  4820.2  497.93
  4855.3  497.37  4865.3  497.87  4891.2  499.96  4904.7  500.36  4940.9  497.10
  4961.7  497.50  4983.6  495.87  4992.1  492.79  4993.0  491.99  5000.8  491.99
  5001.7  492.79  5004.5  496.23  5015.6  497.04  5047.3  497.77  5096.7  496.68
  5162.7  496.62  5175.7  497.49  5198.5  497.58  5266.9  496.31  5439.1  498.24
  5505.8  498.12  5551.3  499.60  5631.7  499.95  5704.4  501.50  5885.8  502.81
#Mann=6,-1,0
  4643.2     0.1       0  4865.3    0.07       0  4992.1    0.07       0
  5001.7    0.07       0  5015.6     0.1       0  5631.7    0.05       0
Bank Sta=4992.1,5001.7
Exp/Cntr=0.3,0.1

Type RM Length L Ch R = 1,21874,451,451,451
BEGIN DESCRIPTION:
Mapping XS 29c23342
END DESCRIPTION:
XS GIS Cut Line= 3
      2007358.12     13503634.37      2006740.98     13503850.50
      2006239.20     13504638.27
#Sta/Elev= 30
  4167.0  501.80  4278.2  501.28  4297.5  500.60  4371.6  499.98  4477.6  499.95
  4572.5  498.79  4670.8  499.04  4696.6  498.25  4742.5  498.85  4795.4  497.29
  4820.1  498.58  4857.9  498.15  4863.8  498.95  4918.0  496.07  4988.3  492.95
  5032.6  493.11  5062.1  492.61  5063.1  491.81  5070.9  491.81  5071.8  492.61
  5150.5  493.97  5212.6  495.41  5270.1  494.69  5342.9  495.03  5436.9  497.28
  5546.1  498.51  5552.0  499.02  5568.1  498.79  5676.5  500.98  5754.9  501.18
#Mann=7,-1,0
  4167.0     0.1       0  4918.0    0.12       0  5032.6    0.07       0
  5062.1    0.07       0  5071.8    0.07       0  5150.5     0.1       0
  5568.1    0.05       0
Bank Sta=5062.1,5071.8
Exp/Cntr=0.3,0.1

Type RM Length L Ch R = 1,21423,493,493,493
BEGIN DESCRIPTION:
Mapping XS bca2c03c
END DESCRIPTION:
XS GIS Cut Line= 3
      2007319.13     13503332.26      2006563.89     13503558.84
      2005993.61     13503978.08
#Sta/Elev= 30
  3876.2  498.52  3922.3  498.46  4047.6  496.40  4131.1  496.41  4172.8  495.48
  4245.9  495.12  4277.2  494.18  4298.1  494.60  4339.9  493.72  4355.5  494.05
  4371.2  493.55  4433.9  493.42  4465.2  493.52  4475.6  493.98  4526.1  493.12
  4538.3  493.93  4548.7  492.78  4559.1  492.49  4824.7  494.20  4942.4  492.12
  4943.3  492.12  4993.4  491.29  4994.3  490.49  5002.2  490.49  5003.2  491.29
  5010.8  491.96  5090.1  493.91  5219.7  494.98  5253.8  495.89  5372.5  497.07
#Mann=6,-1,0
  3876.2     0.1       0  4942.4    0.07       0  4943.3     0.1       0
  4993.4    0.07       0  5003.2     0.1       0  5253.8    0.05       0
Bank Sta=4993.4,5003.2
Exp/Cntr=0.3,0.1

Type RM Length L Ch R = 1,20930,410,410,410
BEGIN DESCRIPTION:
UNT 003 in RCW 29.0
END DESCRIPTION:
XS GIS Cut Line= 3
      2007131.60     13503004.15      2006472.75     13503261.96
      2005830.07     13503340.02
#Sta/Elev= 30
  4056.4  500.45  4117.2  500.68  4287.8  498.84  4353.4  497.69  4396.4  497.74
  4480.5  496.44  4493.0  495.54  4525.2  495.53  4534.8  495.96  4557.4  495.49
  4564.6  496.16  4570.0  496.05  4578.9  494.98  4624.3  493.37  4727.5  492.13
  4757.3  491.26  4771.7  491.77  4872.4  492.86  4915.6  492.15  4953.0  490.92
  4973.2  491.24  4983.2  490.31  4987.5  489.38  4988.4  488.58  4996.3  488.58
  4997.3  489.38  5013.5  490.89  5081.9  493.51  5247.7  496.14  5411.3  496.13
#Mann=4,-1,0
  4056.4     0.1       0  4987.5    0.07       0  4997.3     0.1       0
  5081.9    0.05       0
Bank Sta=4987.5,4997.3
Exp/Cntr=0.3,0.1

Type RM Length L Ch R = 1,20520,228,228,228
BEGIN DESCRIPTION:
Mapping XS e132e3dd
END DESCRIPTION:
XS GIS Cut Line= 2
      2006594.24     13502750.69      2005795.67     13503145.64
#Sta/Elev= 30
  4615.5  498.95  4670.4  498.55  4684.4  498.11  4706.8  498.09  4715.1  497.72
  4746.1  497.35  4848.9  494.08  4858.3  494.20  4863.9  493.79  4915.9  491.97
  4976.0  490.76  4987.8  490.04  4988.8  489.24  4997.0  489.24  4998.0  490.04
  4998.5  490.38  5015.3  490.77  5072.1  491.09  5116.7  491.80  5133.1  492.31
  5139.0  492.14  5161.3  492.36  5178.3  491.98  5222.8  491.94  5261.7  492.25
  5357.4  494.46  5385.4  494.68  5395.6  495.03  5484.8  495.79  5506.4  495.65
#Mann=4,-1,0
  4615.5     0.1       0  4987.8    0.07       0  4998.0     0.1       0
  5178.3    0.05       0
Bank Sta=4987.8,4998
Exp/Cntr=0.3,0.1

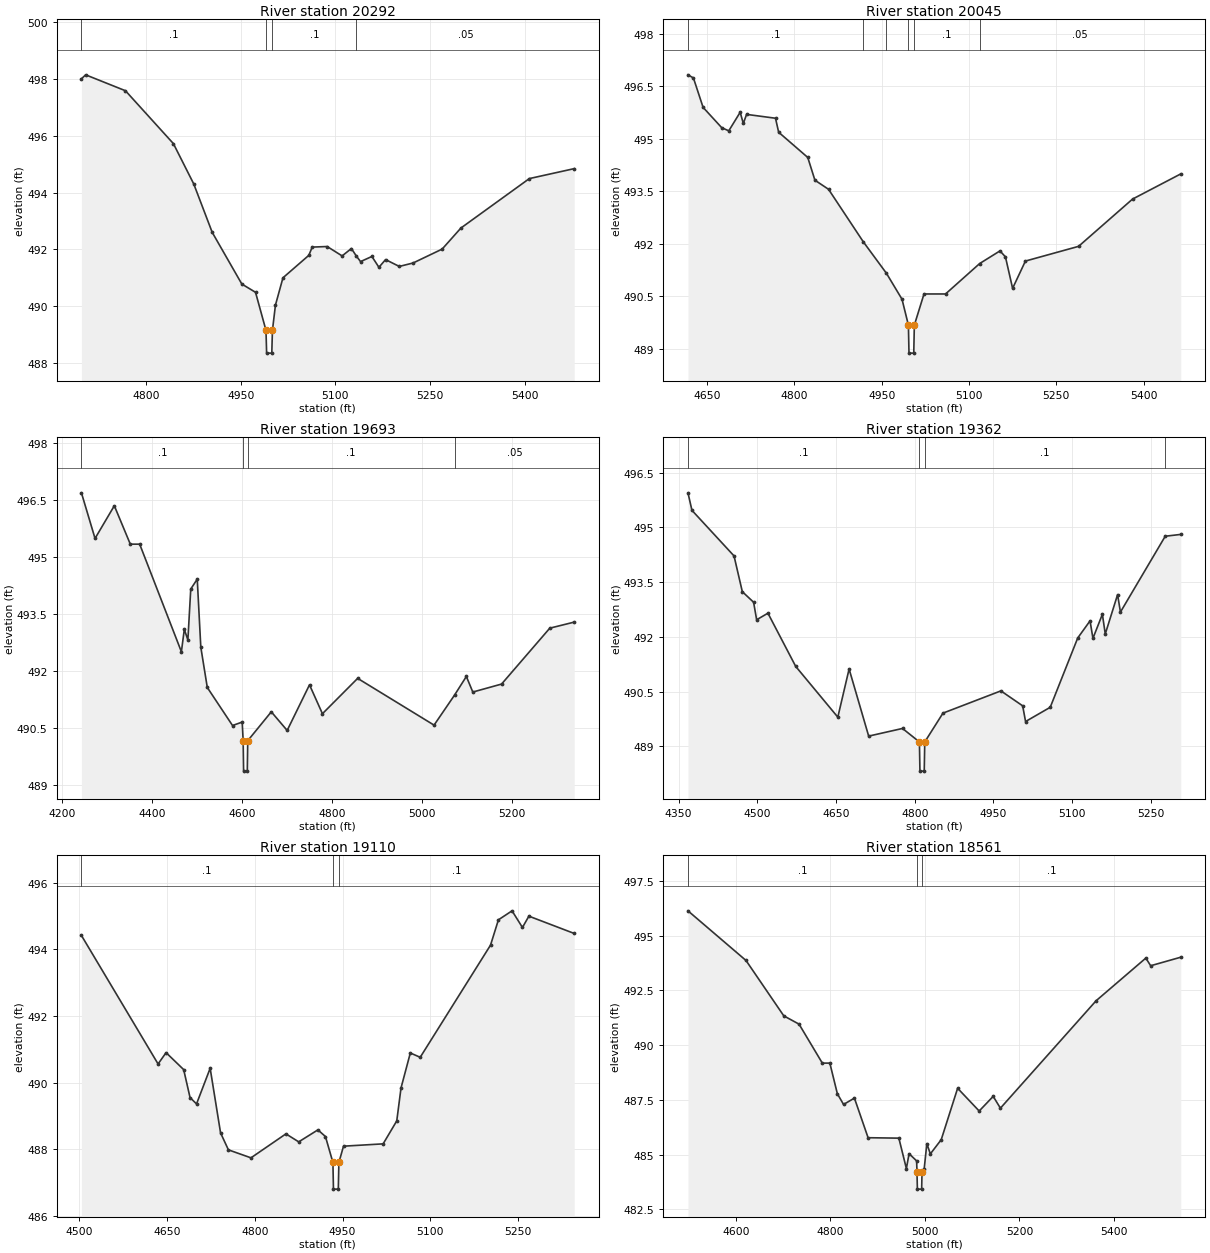
Type RM Length L Ch R = 1,20292,247,247,247
BEGIN DESCRIPTION:
Mapping XS 9fb47fb9
END DESCRIPTION:
XS GIS Cut Line= 2
      2006429.35     13502598.76      2005709.44     13502902.34
#Sta/Elev= 30
  4697.5  498.00  4704.2  498.14  4767.3  497.58  4843.3  495.72  4875.6  494.30
  4904.8  492.60  4951.8  490.78  4973.5  490.49  4990.1  489.15  4991.1  488.35
  4999.3  488.35  5000.3  489.15  5005.1  490.04  5017.0  491.00  5058.0  491.79
  5063.4  492.08  5087.1  492.10  5110.8  491.77  5125.5  492.03  5133.5  491.76
  5140.0  491.57  5158.0  491.75  5169.1  491.37  5179.7  491.64  5201.4  491.40
  5223.2  491.52  5269.4  492.01  5299.1  492.75  5407.6  494.49  5478.8  494.84
#Mann=4,-1,0
  4697.5     0.1       0  4990.1    0.07       0  5000.3     0.1       0
  5133.5    0.05       0
Bank Sta=4990.1,5000.3
Exp/Cntr=0.3,0.1

Type RM Length L Ch R = 1,20045,352,352,352
BEGIN DESCRIPTION:
Mapping XS c7deebf4
END DESCRIPTION:
XS GIS Cut Line= 3
      2006409.40     13502533.03      2006149.46     13502436.38
      2005651.61     13502712.46
#Sta/Elev= 30
  4617.3  496.83  4626.7  496.74  4643.3  495.90  4675.3  495.32  4687.4  495.23
  4707.0  495.76  4712.4  495.44  4718.0  495.70  4767.7  495.59  4773.1  495.19
  4823.1  494.47  4835.4  493.82  4858.8  493.56  4918.5  492.06  4958.3  491.16
  4985.0  490.42  4996.0  489.68  4997.0  488.88  5005.2  488.88  5006.2  489.68
  5022.8  490.57  5059.8  490.57  5118.5  491.44  5153.3  491.80  5162.7  491.63
  5175.0  490.73  5197.0  491.51  5288.3  491.93  5381.0  493.28  5463.9  494.00
#Mann=6,-1,0
  4617.3     0.1       0  4918.5    0.07       0  4958.3     0.1       0
  4996.0    0.07       0  5006.2     0.1       0  5118.5    0.05       0
Bank Sta=4996,5006.2
Exp/Cntr=0.3,0.1

Type RM Length L Ch R = 1,19693,331,331,331
BEGIN DESCRIPTION:
Mapping XS 8ffa0953
END DESCRIPTION:
XS GIS Cut Line= 2
      2006401.54     13501759.38      2005553.91     13502451.00
#Sta/Elev= 30
  4243.4  496.68  4273.6  495.48  4316.4  496.34  4351.9  495.33  4372.7  495.33
  4465.3  492.50  4471.8  493.09  4479.7  492.81  4486.1  494.15  4500.5  494.41
  4508.4  492.62  4522.8  491.56  4578.8  490.56  4600.3  490.65  4602.4  490.16
  4603.4  489.36  4611.6  489.36  4612.6  490.16  4664.9  490.92  4700.1  490.43
  4749.7  491.63  4778.4  490.87  4856.6  491.80  5026.2  490.57  5071.7  491.36
  5097.9  491.85  5112.2  491.44  5176.1  491.65  5283.1  493.12  5337.4  493.28
#Mann=4,-1,0
  4243.4     0.1       0  4602.4    0.07       0  4612.6     0.1       0
  5071.7    0.05       0
Bank Sta=4602.4,4612.6
Exp/Cntr=0.3,0.1

Type RM Length L Ch R = 1,19362,252,252,252
BEGIN DESCRIPTION:
Mapping XS b123f0c5
END DESCRIPTION:
XS GIS Cut Line= 3
      2006336.45     13501616.13      2005938.03     13501847.90
      2005498.97     13502037.55
#Sta/Elev= 30
  4367.8  495.95  4375.4  495.47  4455.6  494.22  4471.4  493.24  4492.9  492.95
  4498.7  492.47  4520.2  492.65  4573.2  491.19  4653.4  489.80  4674.9  491.12
  4712.2  489.28  4776.7  489.49  4808.9  489.12  4809.9  488.32  4818.1  488.32
  4819.1  489.12  4853.8  489.91  4964.2  490.52  5005.7  490.11  5011.2  489.68
  5058.2  490.07  5110.6  491.97  5134.1  492.44  5139.6  491.96  5157.6  492.62
  5163.1  492.08  5186.6  493.16  5192.0  492.68  5277.4  494.76  5307.0  494.81
#Mann=4,-1,0
  4367.8     0.1       0  4808.9    0.07       0  4819.1     0.1       0
  5277.4    0.05       0
Bank Sta=4808.9,4819.1
Exp/Cntr=0.3,0.1

Type RM Length L Ch R = 1,19110,549,549,549
BEGIN DESCRIPTION:
Mapping XS 7ae74eec
END DESCRIPTION:
XS GIS Cut Line= 2
      2006234.91     13501462.48      2005464.03     13501803.64
#Sta/Elev= 30
  4503.4  494.42  4634.5  490.56  4648.2  490.90  4678.3  490.39  4689.2  489.55
  4700.3  489.36  4723.6  490.43  4741.4  488.49  4754.8  487.98  4793.4  487.74
  4853.2  488.46  4875.1  488.22  4907.9  488.58  4920.8  488.38  4933.6  487.60
  4934.5  486.80  4942.8  486.80  4943.8  487.60  4951.7  488.09  5019.5  488.16
  5042.8  488.85  5050.1  489.84  5066.0  490.89  5082.9  490.76  5203.2  494.13
  5216.7  494.89  5240.0  495.16  5257.8  494.66  5268.8  495.00  5346.4  494.48
#Mann=3,-1,0
  4503.4     0.1       0  4933.6    0.07       0  4943.8     0.1       0
Bank Sta=4933.6,4943.8
Exp/Cntr=0.3,0.1

Type RM Length L Ch R = 1,18561,263,263,263
BEGIN DESCRIPTION:
Mapping XS 67f5367b
END DESCRIPTION:
XS GIS Cut Line= 4
      2005966.67     13500933.84      2005724.48     13501053.63
      2005536.98     13501386.96      2005451.06     13501767.13
#Sta/Elev= 30
  4498.8  496.14  4621.6  493.87  4701.5  491.34  4733.8  490.96  4783.0  489.18
  4798.9  489.18  4814.8  487.78  4827.9  487.29  4850.9  487.58  4879.8  485.77
  4944.9  485.75  4960.8  484.36  4966.5  485.04  4982.5  484.71  4983.2  484.22
  4984.1  483.42  4993.1  483.42  4993.9  484.22  4998.4  484.33  5004.1  485.50
  5011.5  485.03  5034.5  485.68  5069.2  488.03  5114.8  486.99  5144.4  487.66
  5159.7  487.12  5362.1  492.03  5467.3  493.98  5477.5  493.63  5541.2  494.02
#Mann=3,-1,0
  4498.8     0.1       0  4983.2    0.07       0  4993.9     0.1       0
Bank Sta=4983.2,4993.9
Exp/Cntr=0.3,0.1