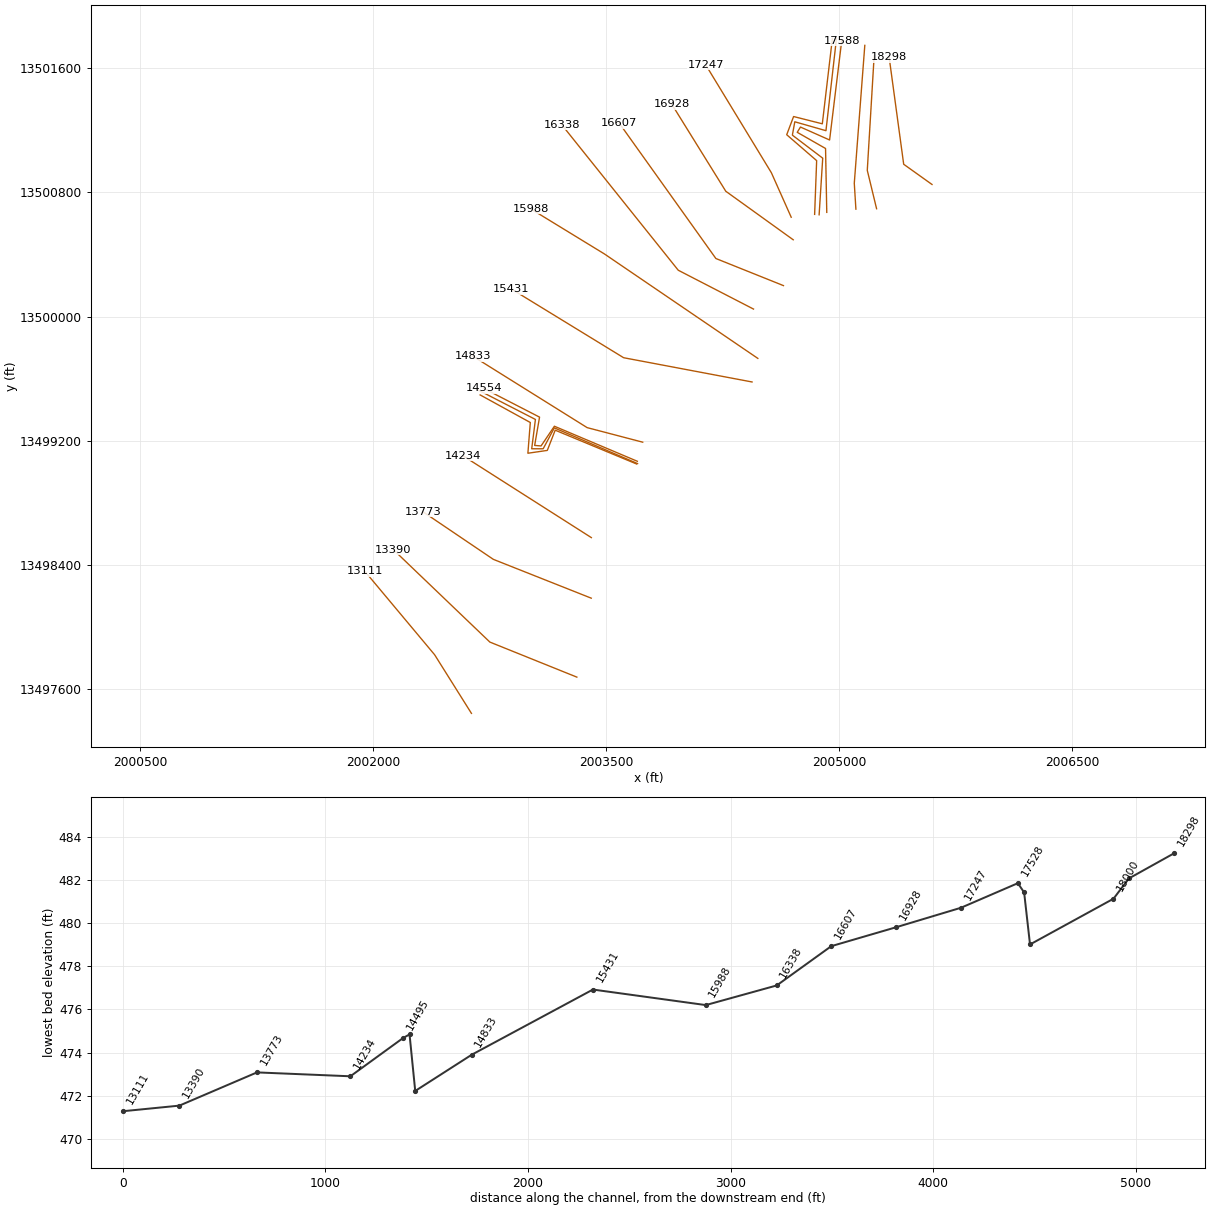
HEC-RAS study UNT 003 in RCW.prj: UNT 003 in RCW Base Level Engineering

--- UNT 003 in RCW.g01 (geometry) --- (continued)

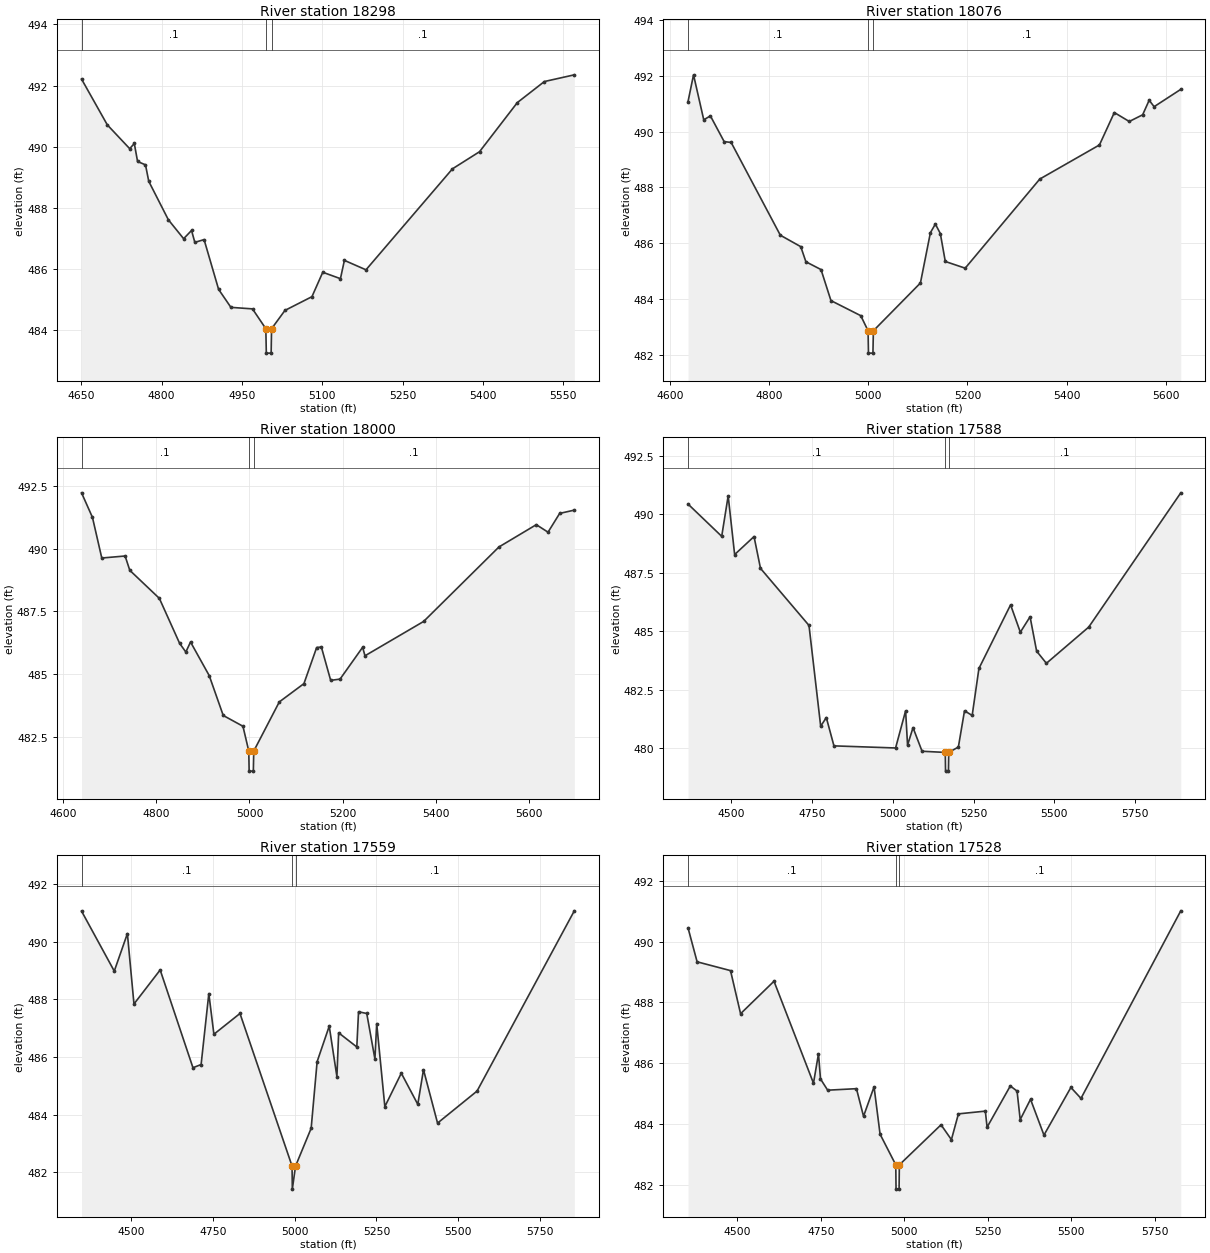
Type RM Length L Ch R = 1,18298,222,222,222
BEGIN DESCRIPTION:
Mapping XS 1396c364
END DESCRIPTION:
XS GIS Cut Line= 3
      2005596.92     13500850.48      2005414.59     13500980.71
      2005320.89     13501670.41
#Sta/Elev= 30
  4650.5  492.21  4698.6  490.71  4740.4  489.93  4749.0  490.10  4755.1  489.51
  4769.9  489.40  4776.0  488.86  4812.6  487.60  4841.1  486.98  4855.9  487.25
  4862.0  486.86  4879.3  486.95  4906.4  485.32  4929.4  484.73  4969.7  484.68
  4994.6  484.03  4995.5  483.23  5004.5  483.23  5005.3  484.03  5030.3  484.63
  5080.7  485.08  5100.9  485.88  5133.9  485.67  5141.3  486.27  5181.6  485.96
  5343.1  489.27  5393.6  489.83  5464.2  491.44  5514.7  492.13  5570.6  492.35
#Mann=3,-1,0
  4650.5     0.1       0  4994.6    0.07       0  5005.3     0.1       0
Bank Sta=4994.6,5005.3
Exp/Cntr=0.3,0.1

Type RM Length L Ch R = 1,18076,76,76,76
BEGIN DESCRIPTION:
Mapping XS aed7fdd7
END DESCRIPTION:
XS GIS Cut Line= 3
      2005240.12     13500694.21      2005180.21     13500941.65
      2005224.48     13501678.63
#Sta/Elev= 30
  4636.9  491.07  4648.0  492.03  4668.6  490.42  4682.0  490.56  4709.7  489.64
  4723.8  489.61  4822.9  486.29  4864.1  485.88  4874.4  485.34  4904.9  485.06
  4924.9  483.95  4985.0  483.41  4999.7  482.87  5000.5  482.07  5009.5  482.07
  5010.4  482.87  5105.2  484.58  5125.3  486.38  5135.3  486.69  5145.3  486.35
  5155.3  485.35  5195.4  485.11  5345.7  488.30  5465.9  489.52  5495.9  490.68
  5526.0  490.36  5553.0  490.60  5566.1  491.12  5576.1  490.89  5629.8  491.51
#Mann=3,-1,0
  4636.9     0.1       0  4999.7    0.07       0  5010.4     0.1       0
Bank Sta=4999.7,5010.4
Exp/Cntr=0.3,0.1

Type RM Length L Ch R = 1,18000,412,412,412
BEGIN DESCRIPTION:
Mapping XS 58b8191b
END DESCRIPTION:
XS GIS Cut Line= 3
      2005107.00     13500691.66      2005096.58     13500858.36
      2005164.28     13501746.36
#Sta/Elev= 30
  4639.6  492.23  4663.0  491.25  4683.0  489.63  4733.1  489.71  4743.1  489.14
  4806.6  488.02  4850.0  486.23  4863.4  485.88  4873.5  486.28  4913.6  484.94
  4943.7  483.35  4986.0  482.92  4998.5  481.93  4999.3  481.13  5008.3  481.13
  5009.2  481.93  5064.0  483.89  5116.9  484.62  5144.2  486.06  5154.3  486.08
  5174.3  484.75  5194.4  484.80  5242.9  486.07  5247.9  485.73  5373.8  487.10
  5535.4  490.07  5615.6  490.96  5640.8  490.66  5665.8  491.41  5697.2  491.54
#Mann=3,-1,0
  4639.6     0.1       0  4998.5    0.07       0  5009.2     0.1       0
Bank Sta=4998.5,5009.2
Exp/Cntr=0.3,0.1

Type RM Length L Ch R = 1,17588,29,29,29
BEGIN DESCRIPTION:
Mapping XS 5d4af674
END DESCRIPTION:
XS GIS Cut Line= 6
      2004919.49     13500670.83      2004911.68     13501082.31
      2004729.39     13501186.48      2004750.22     13501220.33
      2004937.72     13501137.00      2005015.84     13501777.60
#Sta/Elev= 30
  4366.6  490.43  4470.8  489.05  4490.8  490.78  4510.8  488.27  4570.8  489.04
  4590.8  487.68  4740.8  485.24  4777.0  480.93  4794.4  481.30  4818.0  480.09
  5008.7  480.00  5039.7  481.59  5045.7  480.12  5062.6  480.87  5090.6  479.86
  5162.4  479.81  5163.2  479.01  5172.2  479.01  5173.1  479.81  5202.9  480.04
  5221.9  481.59  5245.6  481.39  5266.5  483.40  5364.4  486.12  5394.6  484.95
  5424.7  485.61  5445.0  484.14  5475.2  483.62  5606.2  485.17  5890.9  490.91
#Mann=3,-1,0
  4366.6     0.1       0  5162.4    0.07       0  5173.1     0.1       0
Bank Sta=5162.4,5173.1
Exp/Cntr=0.3,0.1

Type RM Length L Ch R = 1,17559,31,31,31
BEGIN DESCRIPTION:
Mapping XS ddea1f04
END DESCRIPTION:
XS GIS Cut Line= 6
      2004870.32     13500655.17      2004893.45     13501019.81
      2004698.14     13501168.25      2004713.76     13501254.19
      2004914.29     13501196.90      2004981.96     13501790.35
#Sta/Elev= 30
  4348.6  491.06  4448.6  488.98  4488.7  490.28  4508.8  487.84  4588.9  489.02
  4689.1  485.63  4714.0  485.74  4737.6  488.20  4753.1  486.79  4832.8  487.51
  4992.0  482.22  4992.8  481.42  5002.7  482.22  5050.4  483.53  5068.6  485.84
  5105.6  487.07  5129.1  485.32  5134.4  486.84  5189.9  486.35  5195.2  487.57
  5220.3  487.51  5245.3  485.93  5250.7  487.16  5275.6  484.28  5325.9  485.44
  5376.3  484.36  5393.7  485.56  5436.7  483.71  5557.4  484.82  5854.7  491.07
#Mann=3,-1,0
  4348.6     0.1       0  4992.0    0.07       0  5002.7     0.1       0
Bank Sta=4992,5002.7
Exp/Cntr=0.3,0.1

Type RM Length L Ch R = 1,17528,281,281,281
BEGIN DESCRIPTION:
Mapping XS 721bc43b
END DESCRIPTION:
XS GIS Cut Line= 6
      2004841.37     13500657.85      2004854.39     13501004.19
      2004661.68     13501170.86      2004705.95     13501288.04
      2004890.85     13501241.17      2004955.76     13501791.65
#Sta/Elev= 30
  4352.8  490.46  4380.0  489.34  4480.0  489.05  4510.1  487.63  4610.1  488.70
  4728.3  485.34  4743.3  486.31  4749.3  485.48  4770.8  485.11  4856.9  485.16
  4878.1  484.25  4909.6  485.22  4927.6  483.66  4974.6  482.65  4975.4  481.85
  4984.5  481.85  4985.3  482.65  5110.1  483.97  5141.1  483.48  5162.1  484.33
  5242.7  484.42  5247.9  483.89  5317.4  485.25  5337.6  485.08  5347.0  484.14
  5377.9  484.81  5418.1  483.63  5498.7  485.20  5528.9  484.84  5827.6  491.02
#Mann=3,-1,0
  4352.8     0.1       0  4974.6    0.07       0  4985.3     0.1       0
Bank Sta=4974.6,4985.3
Exp/Cntr=0.3,0.1

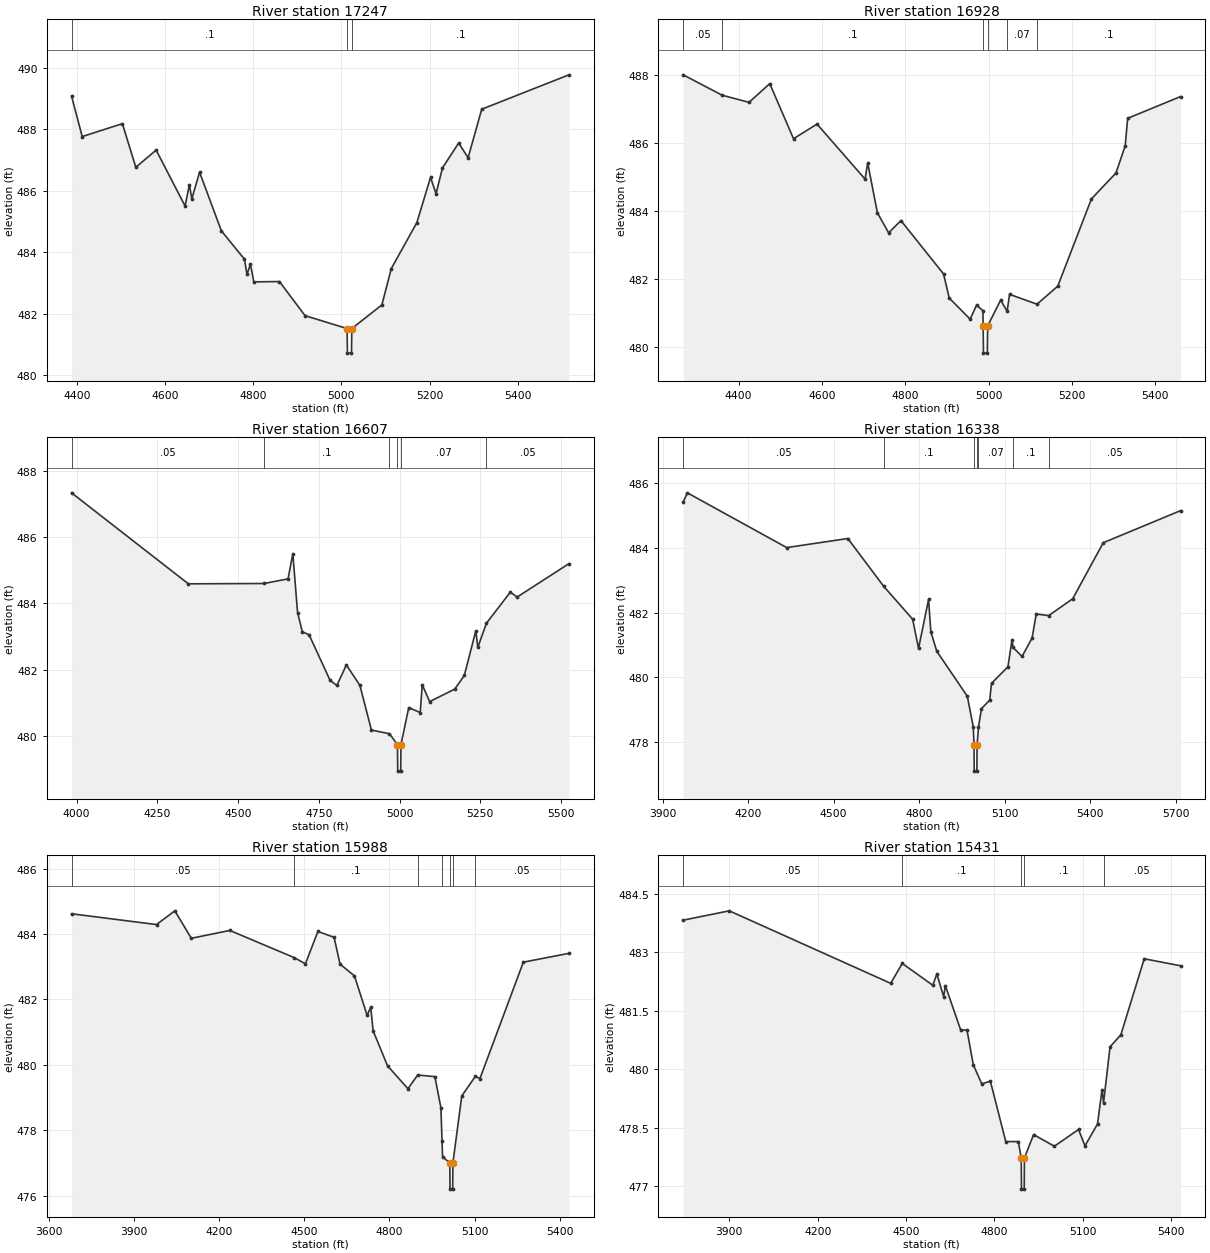
Type RM Length L Ch R = 1,17247,319,319,319
BEGIN DESCRIPTION:
Mapping XS 39881a9b
END DESCRIPTION:
XS GIS Cut Line= 3
      2004690.62     13500639.59      2004563.03     13500926.02
      2004139.29     13501622.72
#Sta/Elev= 30
  4387.5  489.08  4411.7  487.76  4502.9  488.18  4533.4  486.76  4579.5  487.32
  4645.2  485.50  4655.0  486.19  4660.5  485.73  4678.1  486.60  4727.6  484.69
  4779.9  483.77  4785.8  483.27  4793.5  483.61  4801.2  483.03  4859.4  483.04
  4917.5  481.93  5012.9  481.51  5013.7  480.71  5022.9  480.71  5023.7  481.51
  5091.9  482.28  5113.2  483.46  5171.3  484.96  5202.3  486.43  5214.9  485.90
  5229.4  486.74  5266.2  487.55  5287.6  487.07  5318.5  488.65  5516.5  489.77
#Mann=3,-1,0
  4387.5     0.1       0  5012.9    0.07       0  5023.7     0.1       0
Bank Sta=5012.9,5023.7
Exp/Cntr=0.3,0.1

Type RM Length L Ch R = 1,16928,321,321,321
BEGIN DESCRIPTION:
Mapping XS 0c3b0ad7
END DESCRIPTION:
XS GIS Cut Line= 3
      2004703.69     13500494.28      2004269.62     13500806.81
      2003922.40     13501366.71
#Sta/Elev= 30
  4266.9  488.00  4360.6  487.40  4425.0  487.19  4474.8  487.74  4531.8  486.12
  4588.3  486.55  4703.6  484.93  4709.8  485.41  4733.1  483.94  4760.1  483.35
  4789.6  483.71  4891.9  482.14  4905.5  481.43  4955.7  480.81  4971.0  481.22
  4986.4  481.06  4986.9  480.61  4987.7  479.81  4996.9  479.81  4997.7  480.61
  5028.9  481.37  5044.5  481.04  5050.2  481.54  5116.2  481.25  5165.9  481.78
  5246.8  484.35  5305.6  485.11  5327.8  485.91  5333.7  486.72  5460.6  487.36
#Mann=6,-1,0
  4266.9    0.05       0  4360.6     0.1       0  4986.9    0.07       0
  4997.7     0.1       0  5044.5    0.07       0  5116.2     0.1       0
Bank Sta=4986.9,4997.7
Exp/Cntr=0.3,0.1

Type RM Length L Ch R = 1,16607,269,269,269
BEGIN DESCRIPTION:
Mapping XS bcd45504
END DESCRIPTION:
XS GIS Cut Line= 3
      2004640.69     13500199.18      2004205.82     13500373.65
      2003583.43     13501246.03
#Sta/Elev= 30
  3984.2  487.34  4345.9  484.59  4580.3  484.60  4654.6  484.74  4669.4  485.50
  4684.1  483.72  4698.9  483.14  4719.8  483.05  4784.9  481.67  4805.8  481.52
  4835.2  482.14  4877.1  481.52  4912.8  480.17  4968.7  480.06  4993.4  479.73
  4994.2  478.93  5003.4  478.93  5004.2  479.73  5028.3  480.85  5063.9  480.70
  5070.1  481.54  5093.2  481.03  5170.9  481.41  5200.4  481.82  5236.0  483.17
  5242.2  482.67  5268.9  483.40  5343.0  484.34  5363.9  484.19  5524.4  485.20
#Mann=6,-1,0
  3984.2    0.05       0  4580.3     0.1       0  4968.7    0.07       0
  4993.4    0.07       0  5004.2    0.07       0  5268.9    0.05       0
Bank Sta=4993.4,5004.2
Exp/Cntr=0.3,0.1

Type RM Length L Ch R = 1,16338,350,350,350
BEGIN DESCRIPTION:
Mapping XS fde30c75
END DESCRIPTION:
XS GIS Cut Line= 3
      2004448.04     13500048.11      2003963.63     13500298.13
      2003213.64     13501235.62
#Sta/Elev= 30
  3971.9  485.41  3986.6  485.70  4335.4  484.01  4549.9  484.29  4676.2  482.81
  4777.3  481.80  4798.1  480.90  4833.3  482.41  4841.3  481.41  4862.1  480.81
  4969.3  479.42  4990.2  478.47  4992.8  477.91  4993.5  477.11  5002.8  477.11
  5003.6  477.91  5008.3  478.46  5019.0  479.04  5047.8  479.30  5054.2  479.82
  5111.8  480.33  5126.2  481.17  5129.4  480.93  5161.4  480.65  5196.7  481.22
  5211.1  481.96  5254.7  481.91  5339.1  482.43  5446.4  484.16  5717.6  485.15
#Mann=7,-1,0
  3971.9    0.05       0  4676.2     0.1       0  4992.8    0.07       0
  5003.6     0.1       0  5008.3    0.07       0  5129.4     0.1       0
  5254.7    0.05       0
Bank Sta=4992.8,5003.6
Exp/Cntr=0.3,0.1

Type RM Length L Ch R = 1,15988,557,557,557
BEGIN DESCRIPTION:
UNT 003 in RCW 23.0
END DESCRIPTION:
XS GIS Cut Line= 3
      2004475.76     13499730.44      2003488.37     13500403.16
      2003013.07     13500693.99
#Sta/Elev= 30
  3680.4  484.62  3979.7  484.29  4044.3  484.71  4102.3  483.87  4237.9  484.11
  4464.5  483.28  4504.2  483.09  4548.2  484.08  4605.1  483.90  4626.1  483.08
  4676.9  482.72  4721.7  481.51  4734.1  481.77  4742.7  481.04  4793.5  479.97
  4865.3  479.27  4899.7  479.69  4960.1  479.64  4981.4  478.69  4985.4  477.67
  4987.3  477.19  5012.8  477.00  5013.5  476.20  5022.8  476.20  5023.6  477.00
  5054.9  479.05  5102.9  479.65  5118.8  479.58  5271.7  483.14  5432.4  483.41
#Mann=7,-1,0
  3680.4    0.05       0  4464.5     0.1       0  4899.7    0.07       0
  4985.4     0.1       0  5012.8    0.07       0  5023.6     0.1       0
  5102.9    0.05       0
Bank Sta=5012.8,5023.6
Exp/Cntr=0.3,0.1

Type RM Length L Ch R = 1,15431,598,598,598
BEGIN DESCRIPTION:
UNT 003 in RCW 22.0
END DESCRIPTION:
XS GIS Cut Line= 3
      2004438.86     13499578.52      2003612.07     13499734.76
      2002889.67     13500177.31
#Sta/Elev= 30
  3743.3  483.82  3899.9  484.06  4447.9  482.20  4487.3  482.71  4590.9  482.15
  4604.7  482.44  4627.7  481.86  4633.5  482.14  4685.7  481.00  4707.0  481.00
  4728.3  480.11  4757.2  479.62  4786.3  479.69  4838.5  478.14  4881.1  478.14
  4891.1  477.72  4891.9  476.92  4901.2  476.92  4901.9  477.72  4933.1  478.32
  5003.5  478.02  5085.6  478.45  5107.4  478.03  5150.0  478.59  5165.4  479.47
  5170.6  479.14  5192.6  480.57  5229.3  480.88  5308.6  482.83  5431.9  482.65
#Mann=5,-1,0
  3743.3    0.05       0  4487.3     0.1       0  4891.1    0.07       0
  4901.9     0.1       0  5170.6    0.05       0
Bank Sta=4891.1,4901.9
Exp/Cntr=0.3,0.1

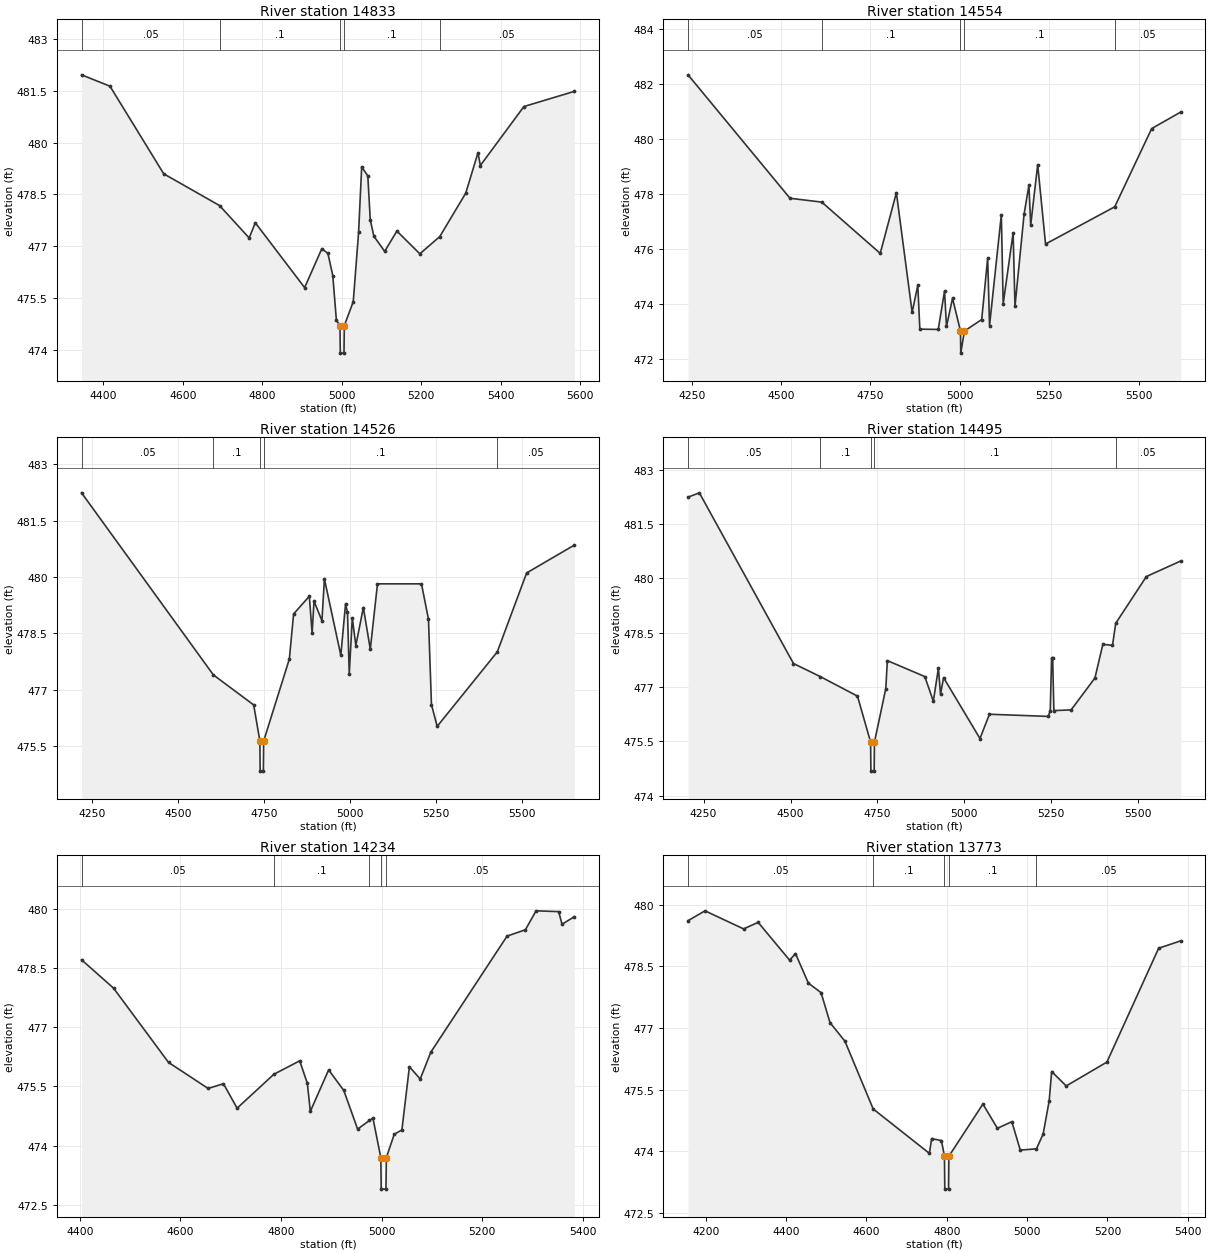
Type RM Length L Ch R = 1,14833,279,279,279
BEGIN DESCRIPTION:
UNT 003 in RCW 21.0
END DESCRIPTION:
XS GIS Cut Line= 3
      2003734.93     13499190.77      2003377.26     13499284.53
      2002639.89     13499745.58
#Sta/Elev= 30
  4345.4  481.97  4416.9  481.64  4552.1  479.10  4692.4  478.18  4767.0  477.24
  4782.4  477.68  4906.5  475.80  4949.8  476.93  4965.1  476.79  4977.3  476.15
  4986.4  474.85  4995.4  474.70  4996.2  473.90  5005.5  473.90  5006.3  474.70
  5028.8  475.39  5042.2  477.40  5050.0  479.30  5065.4  479.04  5071.6  477.76
  5080.7  477.29  5107.8  476.85  5138.5  477.44  5196.3  476.78  5246.4  477.28
  5311.8  478.54  5342.5  479.71  5348.4  479.34  5458.0  481.05  5584.8  481.49
#Mann=5,-1,0
  4345.4    0.05       0  4692.4     0.1       0  4995.4    0.07       0
  5006.3     0.1       0  5246.4    0.05       0
Bank Sta=4995.4,5006.3
Exp/Cntr=0.3,0.1

Type RM Length L Ch R = 1,14554,28,28,28
BEGIN DESCRIPTION:
Mapping XS 8433bb85
END DESCRIPTION:
XS GIS Cut Line= 6
      2003700.28     13499067.83      2003166.43     13499293.52
      2003080.71     13499166.57      2003039.48     13499169.82
      2003070.95     13499352.11      2002710.71     13499537.66
#Sta/Elev= 30
  4239.7  482.32  4525.0  477.84  4614.0  477.70  4777.4  475.84  4822.6  478.04
  4866.7  473.70  4882.5  474.68  4888.2  473.09  4939.7  473.08  4957.3  474.47
  4962.8  473.19  4979.7  474.21  5001.9  473.02  5002.7  472.22  5012.9  473.02
  5061.3  473.44  5078.0  475.67  5083.2  473.22  5116.2  477.24  5121.4  474.01
  5149.2  476.59  5154.4  473.92  5180.0  477.28  5193.4  478.31  5198.4  476.87
  5217.9  479.06  5239.9  476.18  5433.4  477.53  5536.8  480.37  5618.2  480.97
#Mann=5,-1,0
  4239.7    0.05       0  4614.0     0.1       0  5001.9    0.07       0
  5012.9     0.1       0  5433.4    0.05       0
Bank Sta=5001.9,5012.9
Exp/Cntr=0.3,0.1

Type RM Length L Ch R = 1,14526,31,31,31
BEGIN DESCRIPTION:
Mapping XS 557e2d6b
END DESCRIPTION:
XS GIS Cut Line= 6
      2003701.88     13499052.92      2003165.89     13499282.94
      2003094.28     13499148.39      2003020.49     13499148.39
      2003044.36     13499337.19      2002664.63     13499532.49
#Sta/Elev= 30
  4218.6  482.24  4602.3  477.40  4719.8  476.60  4737.8  475.64  4738.6  474.84
  4748.0  474.84  4748.8  475.64  4823.6  477.82  4836.0  479.02  4881.8  479.49
  4889.9  478.50  4895.4  479.36  4918.5  478.84  4925.7  479.95  4973.5  477.92
  4987.3  479.29  4992.9  479.06  4998.0  477.43  5006.9  478.91  5017.2  478.18
  5039.1  479.19  5059.3  478.08  5080.2  479.82  5208.3  479.82  5228.7  478.88
  5237.4  476.61  5254.0  476.03  5429.0  478.01  5514.5  480.11  5653.3  480.85
#Mann=5,-1,0
  4218.6    0.05       0  4602.3     0.1       0  4737.8    0.07       0
  4748.8     0.1       0  5429.0    0.05       0
Bank Sta=4737.8,4748.8
Exp/Cntr=0.3,0.1

Type RM Length L Ch R = 1,14495,261,261,261
BEGIN DESCRIPTION:
Mapping XS dd654a63
END DESCRIPTION:
XS GIS Cut Line= 6
      2003695.11     13499050.56      2003171.64     13499268.02
      2003120.86     13499137.81      2002995.86     13499119.58
      2003011.49     13499317.50      2002688.65     13499495.12
#Sta/Elev= 30
  4205.2  482.24  4237.8  482.36  4508.5  477.65  4585.4  477.29  4692.6  476.75
  4730.4  475.48  4731.2  474.68  4740.6  474.68  4741.4  475.48  4774.1  476.96
  4778.5  477.73  4886.2  477.29  4910.8  476.61  4925.4  477.52  4931.5  476.80
  4940.2  477.26  5044.9  475.58  5072.2  476.25  5241.2  476.19  5247.1  476.35
  5250.9  477.79  5254.0  477.79  5257.5  476.35  5307.1  476.37  5375.6  477.25
  5398.4  478.18  5426.1  478.15  5435.4  478.76  5523.6  480.05  5622.5  480.48
#Mann=5,-1,0
  4205.2    0.05       0  4585.4     0.1       0  4730.4    0.07       0
  4741.4     0.1       0  5435.4    0.05       0
Bank Sta=4730.4,4741.4
Exp/Cntr=0.3,0.1

Type RM Length L Ch R = 1,14234,461,461,461
BEGIN DESCRIPTION:
Mapping XS 30d9c76d
END DESCRIPTION:
XS GIS Cut Line= 2
      2003404.32     13498576.16      2002578.74     13499102.71
#Sta/Elev= 30
  4403.5  478.71  4467.2  477.99  4576.3  476.11  4655.1  475.45  4685.5  475.57
  4712.6  474.95  4785.7  475.81  4837.0  476.15  4852.2  475.58  4858.1  474.87
  4894.5  475.92  4924.6  475.40  4952.1  474.42  4975.6  474.64  4982.5  474.70
  4998.2  473.70  4999.0  472.90  5008.4  472.90  5009.2  473.70  5024.9  474.29
  5040.1  474.40  5055.0  476.00  5076.5  475.69  5097.6  476.37  5249.1  479.31
  5285.5  479.47  5306.7  479.95  5351.6  479.93  5358.3  479.61  5382.7  479.80
#Mann=5,-1,0
  4403.5    0.05       0  4785.7     0.1       0  4975.6    0.05       0
  4998.2   0.035       0  5009.2    0.05       0
Bank Sta=4998.2,5009.2
Exp/Cntr=0.3,0.1

Type RM Length L Ch R = 1,13773,383,383,383
BEGIN DESCRIPTION:
UNT 003 in RCW 20.0
END DESCRIPTION:
XS GIS Cut Line= 3
      2003403.72     13498186.16      2002773.53     13498436.15
      2002318.69     13498743.85
#Sta/Elev= 30
  4155.6  479.61  4197.9  479.85  4294.1  479.41  4330.2  479.57  4408.6  478.65
  4423.2  478.81  4455.4  478.09  4486.9  477.86  4509.2  477.13  4546.3  476.68
  4616.7  475.03  4756.7  473.95  4762.3  474.31  4786.7  474.26  4794.2  473.88
  4795.0  473.08  4804.5  473.08  4805.2  473.88  4890.0  475.15  4926.0  474.56
  4962.0  474.72  4983.0  474.03  5023.3  474.06  5039.9  474.42  5054.9  475.22
  5061.2  475.94  5097.4  475.59  5198.7  476.17  5327.6  478.94  5382.7  479.12
#Mann=5,-1,0
  4155.6    0.05       0  4616.7     0.1       0  4794.2    0.07       0
  4805.2     0.1       0  5023.3    0.05       0
Bank Sta=4794.2,4805.2
Exp/Cntr=0.3,0.1

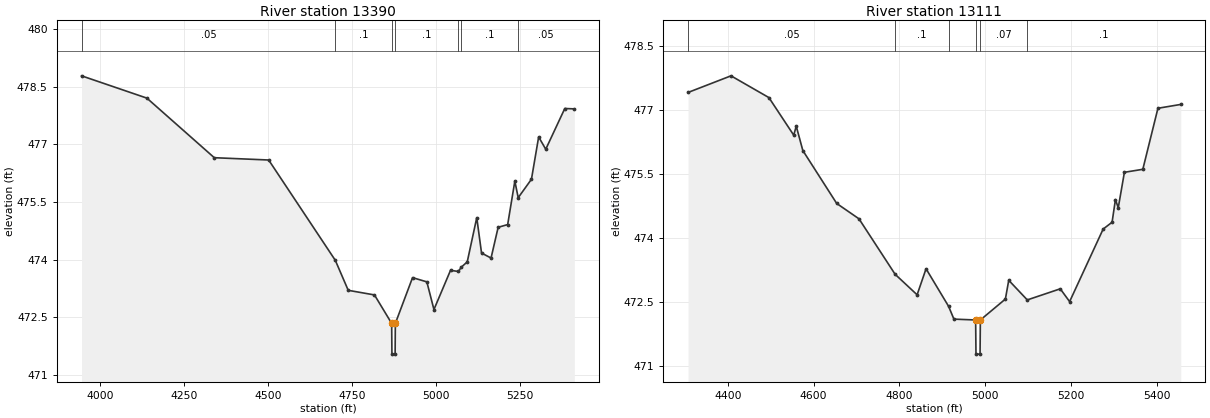
Type RM Length L Ch R = 1,13390,279,279,279
BEGIN DESCRIPTION:
Mapping XS c08ca611
END DESCRIPTION:
XS GIS Cut Line= 3
      2003310.97     13497677.74      2002751.07     13497903.44
      2002129.23     13498499.27
#Sta/Elev= 30
  3946.0  478.78  4140.2  478.20  4340.6  476.65  4502.3  476.59  4700.4  473.98
  4738.8  473.20  4816.8  473.08  4867.9  472.34  4868.7  471.54  4878.2  471.54
  4878.9  472.34  4930.0  473.53  4972.5  473.42  4993.6  472.70  5042.9  473.72
  5066.4  473.69  5074.7  473.80  5092.6  473.94  5120.9  475.09  5135.1  474.17
  5163.4  474.04  5184.5  474.84  5212.8  474.91  5234.1  476.04  5244.1  475.61
  5283.5  476.09  5304.9  477.19  5326.0  476.87  5382.6  477.93  5410.9  477.92
#Mann=7,-1,0
  3946.0    0.05       0  4700.4     0.1       0  4867.9    0.07       0
  4878.9     0.1       0  5066.4    0.07       0  5074.7     0.1       0
  5244.1    0.05       0
Bank Sta=4867.9,4878.9
Exp/Cntr=0.3,0.1

Type RM Length L Ch R = 1,13111,324,324,324
BEGIN DESCRIPTION:
Mapping XS c5ad9ce9
END DESCRIPTION:
XS GIS Cut Line= 3
      2002632.57     13497444.24      2002395.60     13497821.84
      2001945.49     13498360.41
#Sta/Elev= 30
  4307.5  477.41  4407.6  477.80  4495.9  477.29  4553.7  476.41  4559.6  476.62
  4574.9  476.05  4653.8  474.81  4705.7  474.45  4789.9  473.15  4841.1  472.67
  4861.9  473.28  4914.4  472.40  4926.8  472.10  4977.4  472.08  4978.2  471.28
  4987.7  471.28  4988.4  472.08  5046.7  472.57  5054.5  473.01  5097.7  472.55
  5174.5  472.81  5196.3  472.51  5274.4  474.21  5295.2  474.37  5303.0  474.90
  5309.6  474.71  5323.9  475.54  5366.8  475.61  5402.0  477.04  5455.2  477.13
#Mann=6,-1,0
  4307.5    0.05       0  4789.9     0.1       0  4914.4    0.07       0
  4977.4    0.07       0  4988.4    0.07       0  5097.7     0.1       0
Bank Sta=4977.4,4988.4
Exp/Cntr=0.3,0.1