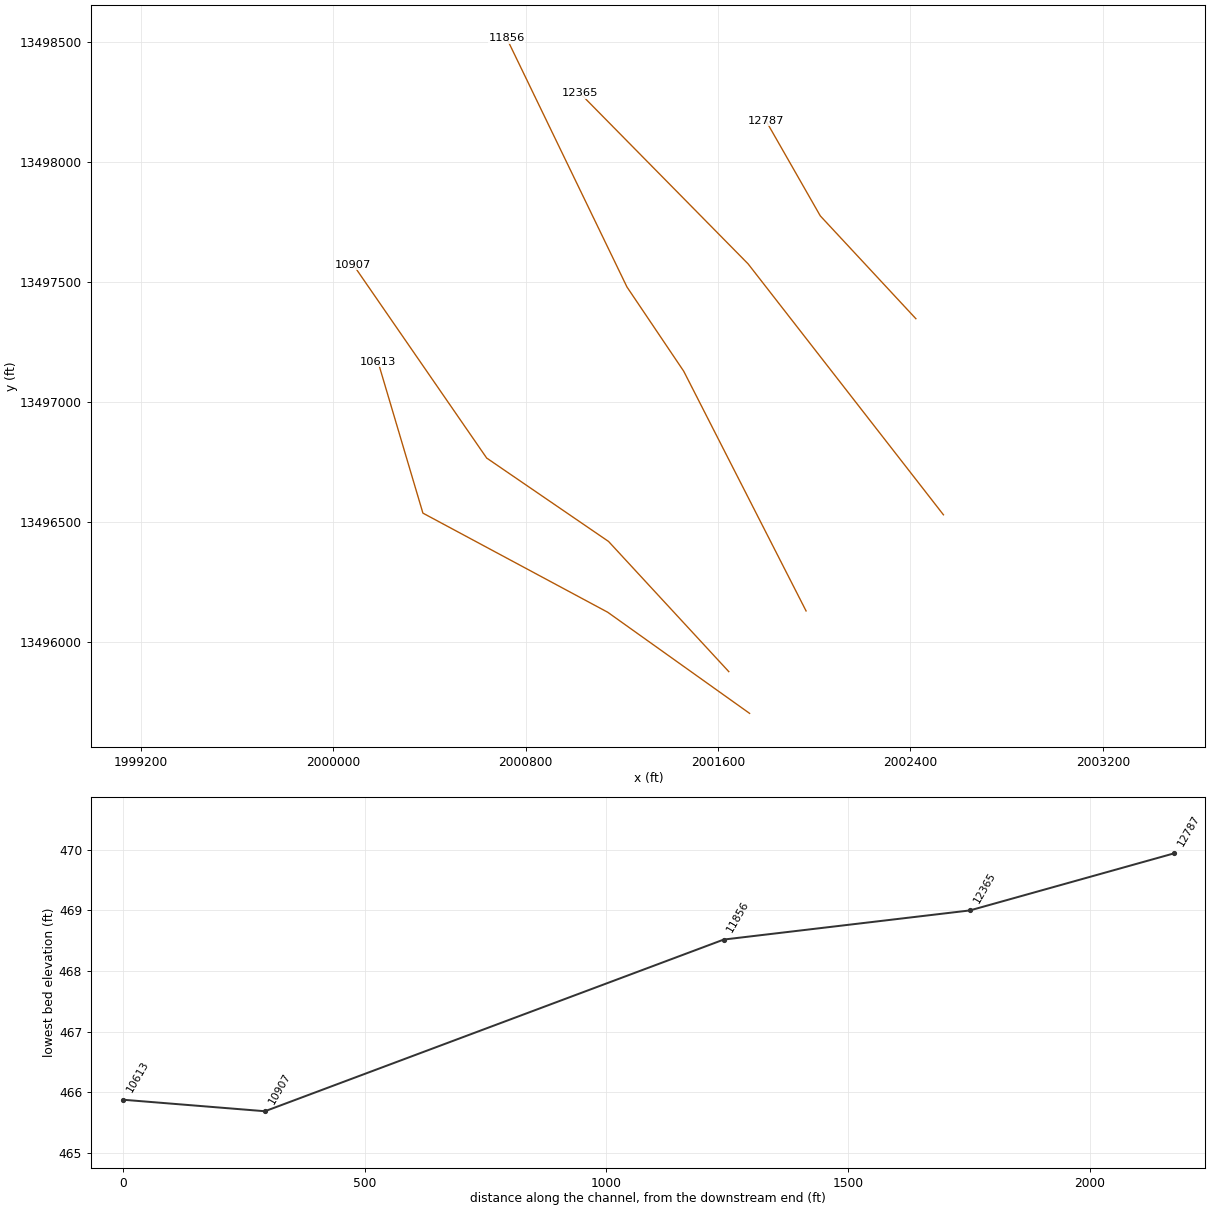
HEC-RAS study UNT 003 in RCW.prj: UNT 003 in RCW Base Level Engineering

--- UNT 003 in RCW.g01 (geometry) --- (continued)

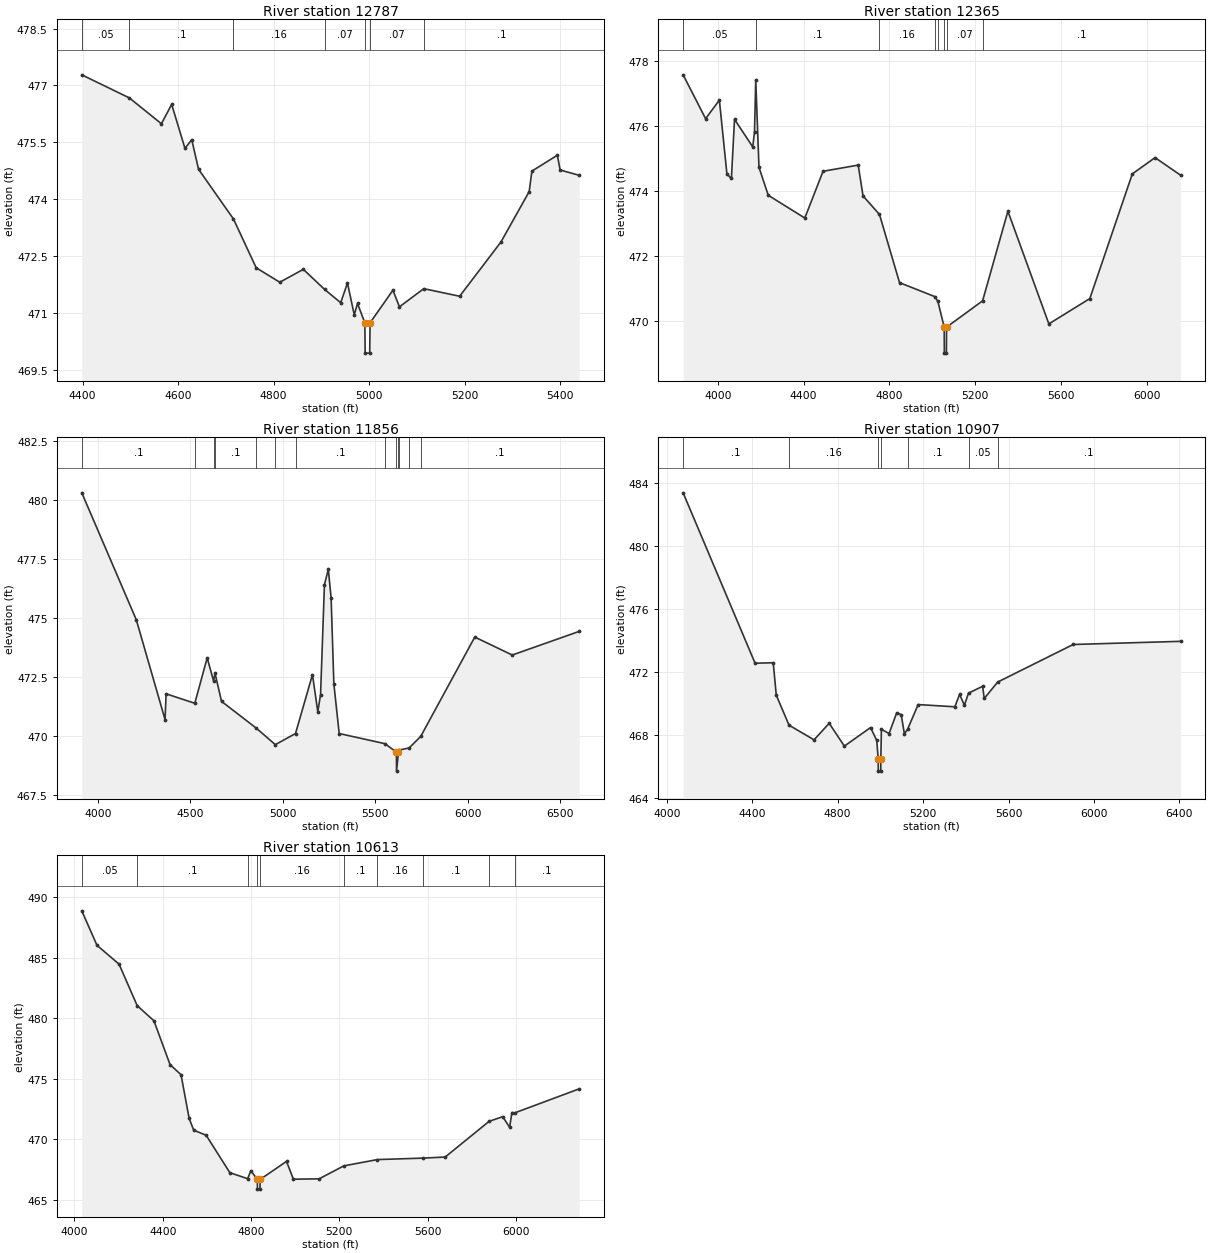
Type RM Length L Ch R = 1,12787,422,422,422
BEGIN DESCRIPTION:
UNT 003 in RCW 19.0
END DESCRIPTION:
XS GIS Cut Line= 3
      2002422.50     13497347.02      2002025.00     13497775.00
      2001798.49     13498171.69
#Sta/Elev= 30
  4398.5  477.28  4498.2  476.67  4565.1  475.99  4586.6  476.50  4614.4  475.34
  4628.6  475.57  4642.8  474.79  4715.8  473.48  4763.5  472.19  4812.8  471.81
  4862.1  472.15  4906.6  471.62  4940.3  471.27  4954.5  471.79  4968.7  470.95
  4975.5  471.25  4990.8  470.74  4991.5  469.94  5001.0  469.94  5001.8  470.74
  5049.6  471.60  5063.2  471.16  5114.1  471.64  5189.2  471.44  5275.6  472.87
  5334.7  474.20  5340.4  474.74  5393.7  475.16  5399.5  474.77  5439.4  474.63
#Mann=7,-1,0
  4398.5    0.05       0  4498.2     0.1       0  4715.8    0.16       0
  4906.6    0.07       0  4990.8    0.07       0  5001.8    0.07       0
  5114.1     0.1       0
Bank Sta=4990.8,5001.8
Exp/Cntr=0.3,0.1

Type RM Length L Ch R = 1,12365,509,509,509
BEGIN DESCRIPTION:
UNT 003 in RCW 18.0
END DESCRIPTION:
XS GIS Cut Line= 3
      2002537.10     13496531.04      2001725.00     13497575.00
      2001026.65     13498284.54
#Sta/Elev= 30
  3838.6  477.57  3943.3  476.22  4007.5  476.79  4042.8  474.51  4063.6  474.38
  4078.1  476.20  4163.1  475.35  4171.3  475.82  4177.0  477.42  4192.1  474.72
  4235.5  473.86  4405.7  473.16  4490.7  474.60  4654.5  474.79  4677.1  473.84
  4753.7  473.27  4847.2  471.17  5011.7  470.74  5026.0  470.59  5055.3  469.80
  5056.0  469.00  5065.5  469.00  5066.3  469.80  5234.3  470.61  5352.2  473.37
  5543.1  469.90  5734.0  470.68  5932.1  474.52  6038.1  475.02  6156.8  474.48
#Mann=8,-1,0
  3838.6    0.05       0  4177.0     0.1       0  4753.7    0.16       0
  5011.7    0.12       0  5026.0    0.07       0  5055.3    0.07       0
  5066.3    0.07       0  5234.3     0.1       0
Bank Sta=5055.3,5066.3
Exp/Cntr=0.3,0.1

Type RM Length L Ch R = 1,11856,949,949,949
BEGIN DESCRIPTION:
UNT 003 in RCW 17.0
END DESCRIPTION:
XS GIS Cut Line= 4
      2001965.90     13496130.89      2001457.23     13497128.26
      2001221.12     13497478.96      2000721.10     13498513.72
#Sta/Elev= 30
  3912.0  480.29  4207.0  474.92  4362.6  470.70  4368.2  471.79  4523.5  471.39
  4590.5  473.31  4625.4  472.33  4632.9  472.66  4668.2  471.47  4855.9  470.34
  4959.3  469.64  5068.5  470.11  5160.3  472.60  5189.1  471.03  5204.1  471.76
  5225.1  476.41  5246.1  477.05  5261.1  475.85  5276.1  472.20  5304.9  470.11
  5553.1  469.68  5614.5  469.32  5615.2  468.52  5625.5  469.32  5628.7  469.41
  5683.5  469.50  5746.1  469.99  6038.6  474.19  6241.2  473.43  6603.6  474.43
#Mann=13,-1,0
  3912.0     0.1       0  4523.5    0.08       0  4625.4    0.05       0
  4632.9     0.1       0  4855.9    0.08       0  4959.3    0.16       0
  5068.5     0.1       0  5553.1    0.07       0  5614.5    0.07       0
  5625.5    0.07       0  5628.7     0.1       0  5683.5    0.07       0
  5746.1     0.1       0
Bank Sta=5614.5,5625.5
Exp/Cntr=0.3,0.1

Type RM Length L Ch R = 1,10907,294,294,294
BEGIN DESCRIPTION:
Mapping XS 234754c9
END DESCRIPTION:
XS GIS Cut Line= 4
      2001644.54     13495878.33      2001144.55     13496419.98
      2000637.61     13496767.20      2000082.99     13497571.40
#Sta/Elev= 30
  4076.5  483.38  4413.3  472.55  4498.3  472.58  4512.5  470.52  4572.2  468.61
  4689.4  467.68  4760.3  468.73  4831.3  467.28  4953.9  468.46  4982.8  467.64
  4989.6  466.49  4990.1  465.69  5001.5  465.69  5002.0  466.49  5004.7  468.35
  5040.5  468.08  5076.4  469.40  5097.4  469.28  5112.3  468.06  5127.5  468.36
  5176.7  469.92  5348.5  469.78  5370.7  470.57  5393.2  469.88  5412.5  470.65
  5478.4  471.08  5486.2  470.31  5548.8  471.35  5902.4  473.74  6405.0  473.94
#Mann=7,-1,0
  4076.5     0.1       0  4572.2    0.16       0  4989.6    0.07       0
  5002.0    0.16       0  5127.5     0.1       0  5412.5    0.05       0
  5548.8     0.1       0
Bank Sta=4989.6,5002
Exp/Cntr=0.3,0.1

Type RM Length L Ch R = 1,10613,0,0,0
BEGIN DESCRIPTION:
Mapping XS fc509f2c
END DESCRIPTION:
XS GIS Cut Line= 4
      2001731.07     13495704.57      2001140.75     13496125.60
      2000372.52     13496537.93      2000185.89     13497167.27
#Sta/Elev= 30
  4033.4  488.86  4102.3  486.01  4202.2  484.46  4284.4  481.03  4360.2  479.78
  4433.3  476.16  4483.0  475.33  4519.4  471.75  4540.2  470.75  4596.8  470.33
  4704.1  467.24  4784.9  466.74  4799.1  467.40  4828.8  466.68  4829.3  465.88
  4840.7  465.88  4841.2  466.68  4960.9  468.17  4992.0  466.70  5108.6  466.73
  5220.4  467.80  5372.6  468.32  5578.3  468.44  5679.6  468.53  5878.9  471.48
  5940.2  471.86  5971.5  470.99  5982.0  472.20  5995.3  472.18  6286.8  474.16
#Mann=10,-1,0
  4033.4    0.05       0  4284.4     0.1       0  4784.9    0.16       0
  4828.8    0.07       0  4841.2    0.16       0  5220.4     0.1       0
  5372.6    0.16       0  5578.3     0.1       0  5878.9    0.05       0
  5995.3     0.1       0
Bank Sta=4828.8,4841.2
Exp/Cntr=0.3,0.1

Chan Stop Cuts=-1