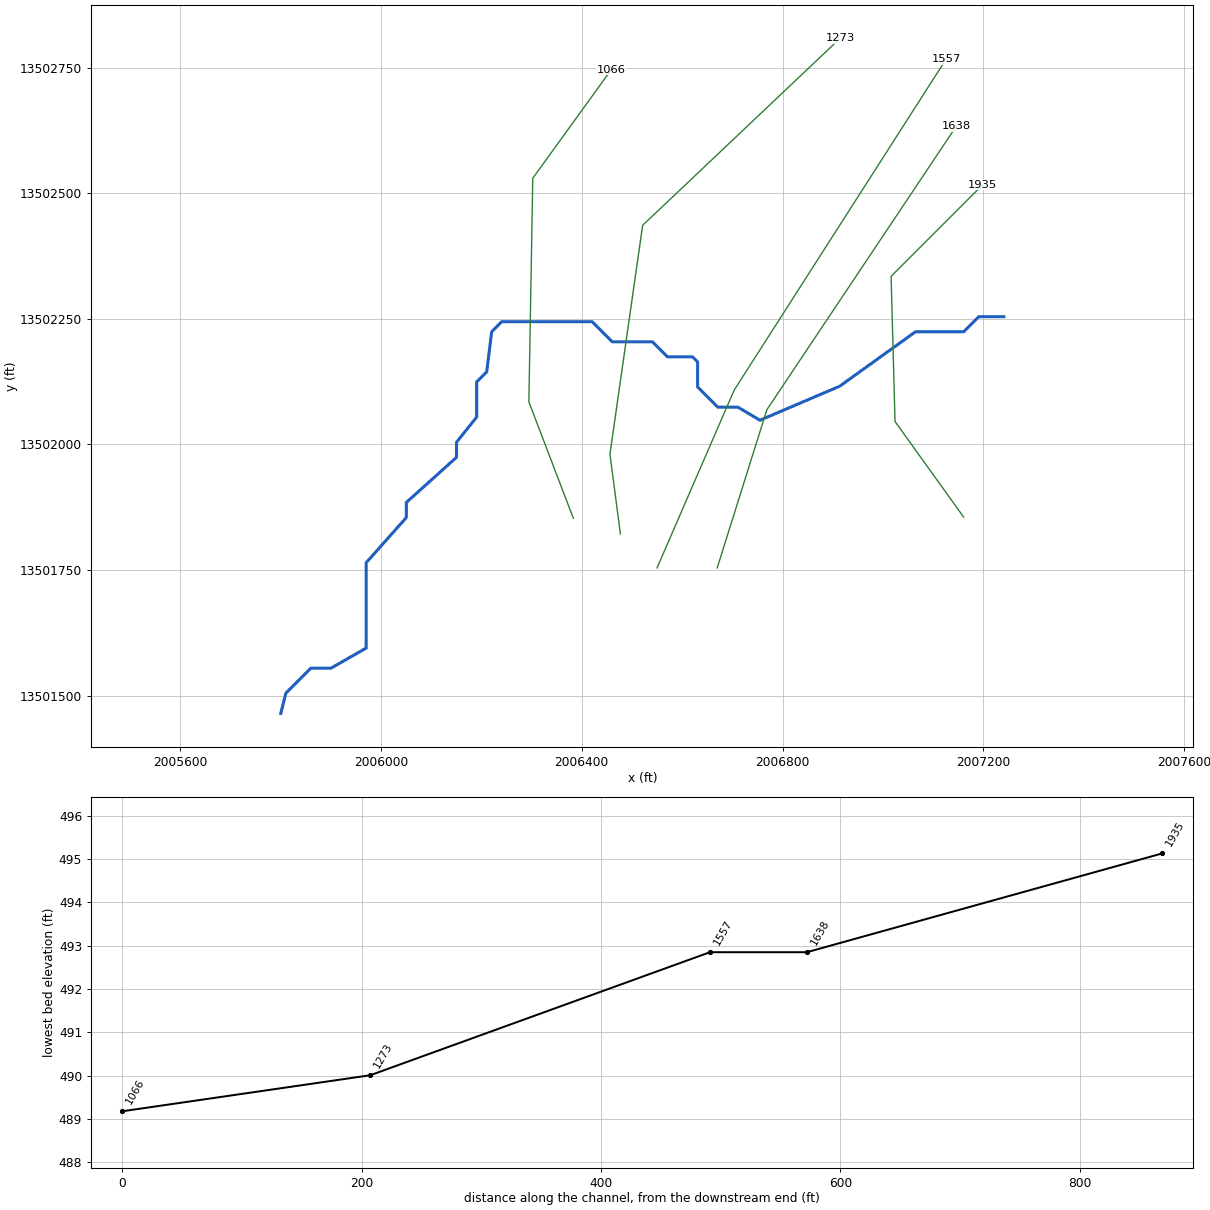
--- UNT 005 in RCW.prj (project) ---

Proj Title=UNT 005 in RCW Base Level Engineering
Current Plan=p01
Default Exp/Contr=0.3,0.1
English Units
Geom File=g01
Flow File=f01
Plan File=p01
BEGIN DESCRIPTION:
UNT 005 in RCW
END DESCRIPTION:

--- UNT 005 in RCW.p01 (plan) ---

Plan Title=Multiple Run
Short Identifier=Multiple
Geom File=g01
Flow File=f01
Subcritical Flow
K Sum by GR= 0
Std Step Tol= 0.01
Critical Tol= 0.01
Num of Std Step Trials= 20
Max Error Tol= 0.3
Flow Tol Ratio= 0.001
Split Flow NTrial= 30
Split Flow Tol= 0.02
Split Flow Ratio= 0.02
Log Output Level= 0
Friction Slope Method= 1
Unsteady Friction Slope Method= 2
Unsteady Bridges Friction Slope Method= 1
Parabolic Critical Depth
Global Vel Dist=  1 , 1 , 1
Global Log Level= 0
CheckData=True
Encroach Param= -1, 0, 0, 0
BEGIN DESCRIPTION:
Multiple Run
END DESCRIPTION:

--- UNT 005 in RCW.f01 (steady flow) ---

Flow Title=Multiple
Number of Profiles=7
Profile Names=10-year,25-year,50-year,1pct_min,100-year,1pct_plu,500-year
River Rch & RM= UNT 005 in RCW,Reach-1,1935
     175     237     287     174     347     693     514
Boundary for River Rch & Prof#=UNT 005 in RCW,Reach-1,1
Up Type=0
Dn Type=3
Dn Slope=0.005
Boundary for River Rch & Prof#=UNT 005 in RCW,Reach-1,2
Up Type=0
Dn Type=3
Dn Slope=0.005
Boundary for River Rch & Prof#=UNT 005 in RCW,Reach-1,3
Up Type=0
Dn Type=3
Dn Slope=0.005
Boundary for River Rch & Prof#=UNT 005 in RCW,Reach-1,4
Up Type=0
Dn Type=3
Dn Slope=0.005
Boundary for River Rch & Prof#=UNT 005 in RCW,Reach-1,5
Up Type=0
Dn Type=3
Dn Slope=0.005
Boundary for River Rch & Prof#=UNT 005 in RCW,Reach-1,6
Up Type=0
Dn Type=3
Dn Slope=0.005
Boundary for River Rch & Prof#=UNT 005 in RCW,Reach-1,7
Up Type=0
Dn Type=3
Dn Slope=0.005

--- UNT 005 in RCW.g01 (geometry) ---

Geom Title=Existing Conditions

River Reach=UNT 005 in RCW,Reach-1
Reach XY= 30
      2007240.80     13502254.54      2007190.80     13502254.54
      2007160.80     13502224.54      2007064.80     13502224.54
      2006913.75     13502116.00      2006754.90     13502048.29
      2006710.80     13502074.54      2006670.80     13502074.54
      2006630.80     13502114.54      2006630.80     13502164.54
      2006620.80     13502174.54      2006570.80     13502174.54
      2006540.80     13502204.54      2006460.80     13502204.54
      2006420.80     13502244.54      2006240.80     13502244.54
      2006220.80     13502224.54      2006210.80     13502144.54
      2006190.80     13502124.54      2006190.80     13502054.54
      2006150.80     13502004.54      2006150.80     13501974.54
      2006050.80     13501884.54      2006050.80     13501854.54
      2005970.80     13501764.54      2005970.80     13501594.54
      2005900.80     13501554.54      2005860.80     13501554.54
      2005810.80     13501504.54      2005800.80     13501464.54

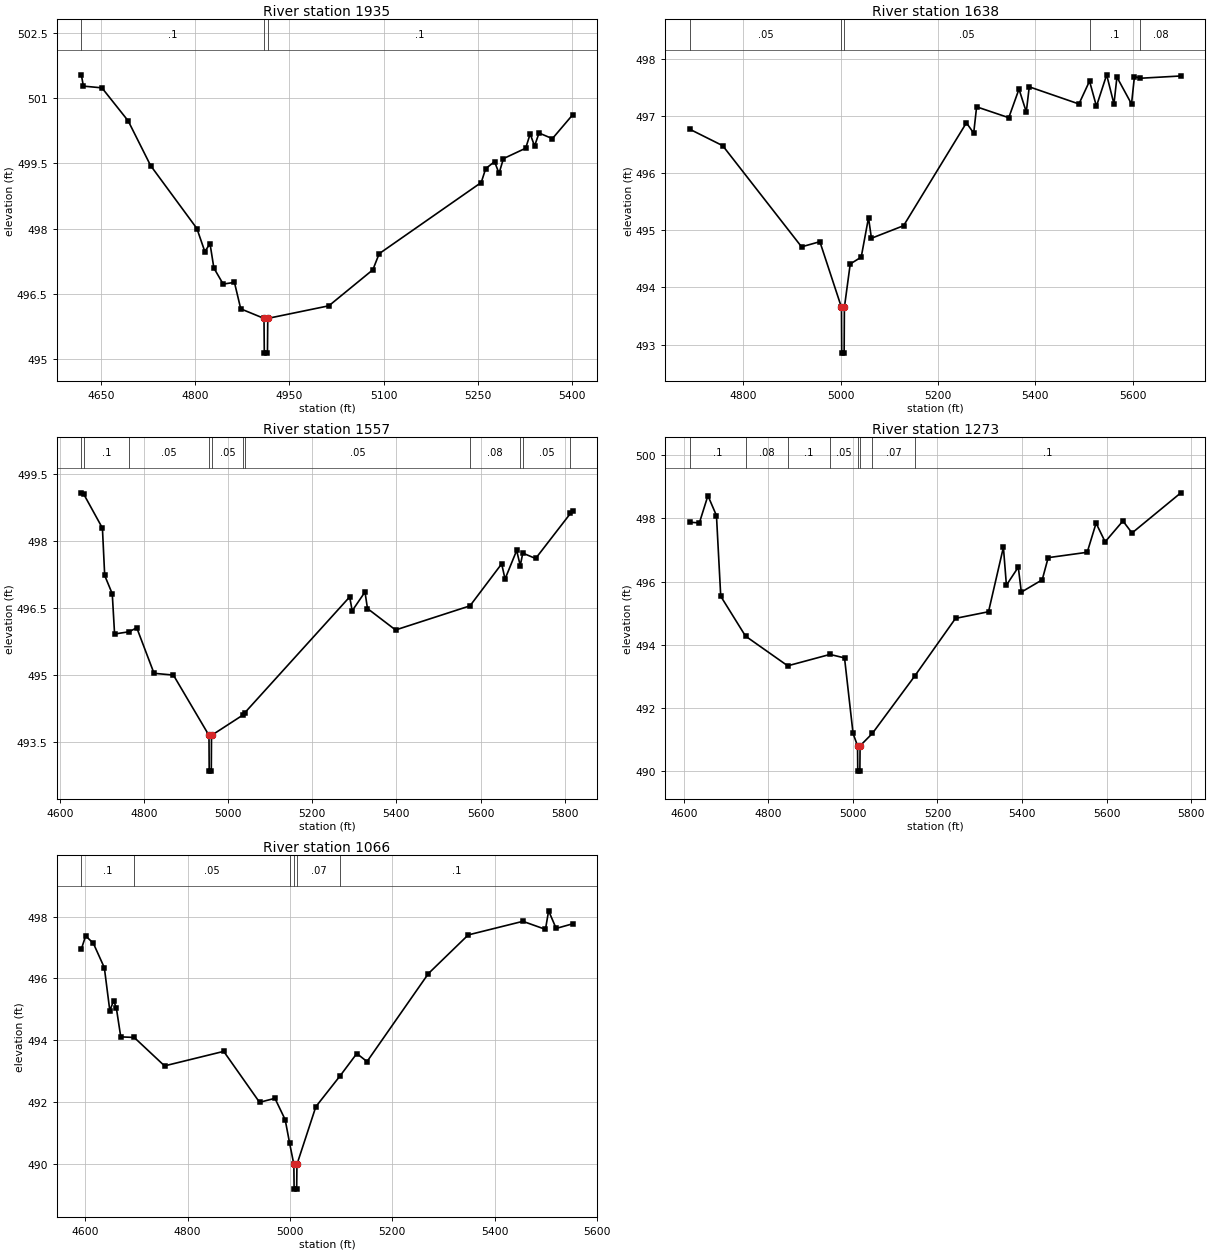
Type RM Length L Ch R = 1,1935,297,297,297
BEGIN DESCRIPTION:
UNT 005 in RCW 1.0
END DESCRIPTION:
XS GIS Cut Line= 4
      2007160.53     13501855.54      2007023.96     13502045.81
      2007016.15     13502334.88      2007198.46     13502517.18
#Sta/Elev= 30
  4619.2  501.54  4622.4  501.28  4651.9  501.24  4693.6  500.48  4729.3  499.45
  4802.9  498.00  4815.5  497.47  4823.8  497.65  4829.9  497.09  4844.7  496.72
  4862.6  496.76  4872.6  496.15  4909.6  495.93  4910.1  495.13  4915.1  495.13
  4915.6  495.93  5012.7  496.22  5082.7  497.05  5092.7  497.42  5255.0  499.06
  5262.1  499.38  5276.2  499.54  5283.3  499.27  5290.3  499.61  5325.7  499.85
  5332.8  500.18  5339.8  499.90  5346.9  500.20  5368.1  500.07  5400.4  500.62
#Mann=3,-1,0
  4619.2     0.1       0  4909.6    0.07       0  4915.6     0.1       0
Bank Sta=4909.6,4915.6
Exp/Cntr=0.3,0.1

Type RM Length L Ch R = 1,1638,81,81,81
BEGIN DESCRIPTION:
UNT 005 in RCW 2.0
END DESCRIPTION:
XS GIS Cut Line= 3
      2006669.80     13501754.15      2006768.76     13502069.25
      2007146.34     13502634.33
#Sta/Elev= 30
  4689.3  496.77  4757.5  496.48  4919.6  494.71  4957.2  494.80  5001.6  493.65
  5002.1  492.85  5007.1  492.85  5007.6  493.65  5019.6  494.41  5042.2  494.53
  5057.2  495.22  5063.2  494.86  5129.3  495.08  5258.4  496.88  5273.4  496.70
  5279.4  497.16  5345.5  496.97  5366.5  497.47  5381.5  497.07  5387.6  497.51
  5489.7  497.21  5511.5  497.61  5525.7  497.17  5546.7  497.72  5561.7  497.21
  5567.8  497.68  5597.8  497.21  5603.8  497.69  5615.7  497.66  5699.2  497.70
#Mann=5,-1,0
  4689.3    0.05       0  5001.6    0.04       0  5007.6    0.05       0
  5511.5     0.1       0  5615.7    0.08       0
Bank Sta=5001.6,5007.6
Exp/Cntr=0.3,0.1

Type RM Length L Ch R = 1,1557,284,284,284
BEGIN DESCRIPTION:
UNT 005 in RCW 3.0
END DESCRIPTION:
XS GIS Cut Line= 3
      2006550.02     13501754.18      2006703.65     13502108.31
      2007125.54     13502767.20
#Sta/Elev= 30
  4650.8  499.08  4655.9  499.06  4700.9  498.29  4706.3  497.23  4724.3  496.82
  4729.8  495.92  4764.5  495.97  4782.5  496.06  4823.6  495.04  4869.7  495.00
  4954.3  493.65  4954.8  492.85  4959.8  492.85  4960.3  493.65  5035.7  494.11
  5039.8  494.16  5288.9  496.75  5294.9  496.44  5325.3  496.86  5331.2  496.49
  5398.0  496.01  5575.0  496.55  5650.3  497.49  5658.4  497.15  5686.0  497.79
  5694.5  497.45  5700.6  497.73  5731.1  497.61  5814.0  498.62  5819.2  498.67
#Mann=11,-1,0
  4650.8    0.08       0  4655.9     0.1       0  4764.5    0.05       0
  4954.3    0.04       0  4960.3    0.05       0  5035.7     0.1       0
  5039.8    0.05       0  5575.0    0.08       0  5694.5     0.1       0
  5700.6    0.05       0  5814.0     0.1       0
Bank Sta=4954.3,4960.3
Exp/Cntr=0.3,0.1

Type RM Length L Ch R = 1,1273,207,207,207
BEGIN DESCRIPTION:
UNT 005 in RCW 4.0
END DESCRIPTION:
XS GIS Cut Line= 4
      2006477.09     13501821.87      2006456.26     13501980.71
      2006521.36     13502436.44      2006914.56     13502808.81
#Sta/Elev= 30
  4613.7  497.88  4637.0  497.86  4657.2  498.72  4677.4  498.09  4687.5  495.54
  4746.1  494.28  4845.9  493.34  4945.9  493.70  4980.3  493.59  5000.5  491.20
  5011.1  490.81  5011.6  490.01  5016.6  490.01  5017.1  490.81  5046.0  491.20
  5146.0  493.01  5242.8  494.84  5320.9  495.05  5356.1  497.09  5363.2  495.89
  5391.3  496.46  5398.5  495.67  5447.9  496.06  5462.0  496.76  5554.3  496.93
  5575.3  497.85  5596.7  497.26  5638.8  497.92  5660.3  497.54  5775.8  498.81
#Mann=8,-1,0
  4613.7     0.1       0  4746.1    0.08       0  4845.9     0.1       0
  4945.9    0.05       0  5011.1    0.04       0  5017.1    0.05       0
  5046.0    0.07       0  5146.0     0.1       0
Bank Sta=5011.1,5017.1
Exp/Cntr=0.3,0.1

Type RM Length L Ch R = 1,1066,0,0,0
BEGIN DESCRIPTION:
UNT 005 in RCW 5.0
END DESCRIPTION:
XS GIS Cut Line= 4
      2006383.34     13501853.10      2006294.80     13502084.88
      2006302.61     13502530.19      2006458.86     13502746.33
#Sta/Elev= 30
  4592.2  496.95  4600.6  497.38  4615.6  497.14  4637.1  496.35  4647.8  494.96
  4655.4  495.28  4660.7  495.03  4669.2  494.11  4695.5  494.09  4754.8  493.17
  4870.4  493.64  4940.5  491.99  4970.5  492.12  4990.5  491.43  4999.3  490.66
  5007.5  489.98  5008.0  489.18  5013.0  489.18  5013.5  489.98  5050.5  491.85
  5098.0  492.85  5130.5  493.57  5150.5  493.31  5270.5  496.16  5348.3  497.41
  5455.1  497.85  5499.2  497.59  5505.4  498.19  5520.1  497.62  5552.4  497.77
#Mann=6,-1,0
  4592.2     0.1       0  4695.5    0.05       0  4999.3    0.07       0
  5007.5    0.07       0  5013.5    0.07       0  5098.0     0.1       0
Bank Sta=5007.5,5013.5
Exp/Cntr=0.3,0.1

Chan Stop Cuts=-1