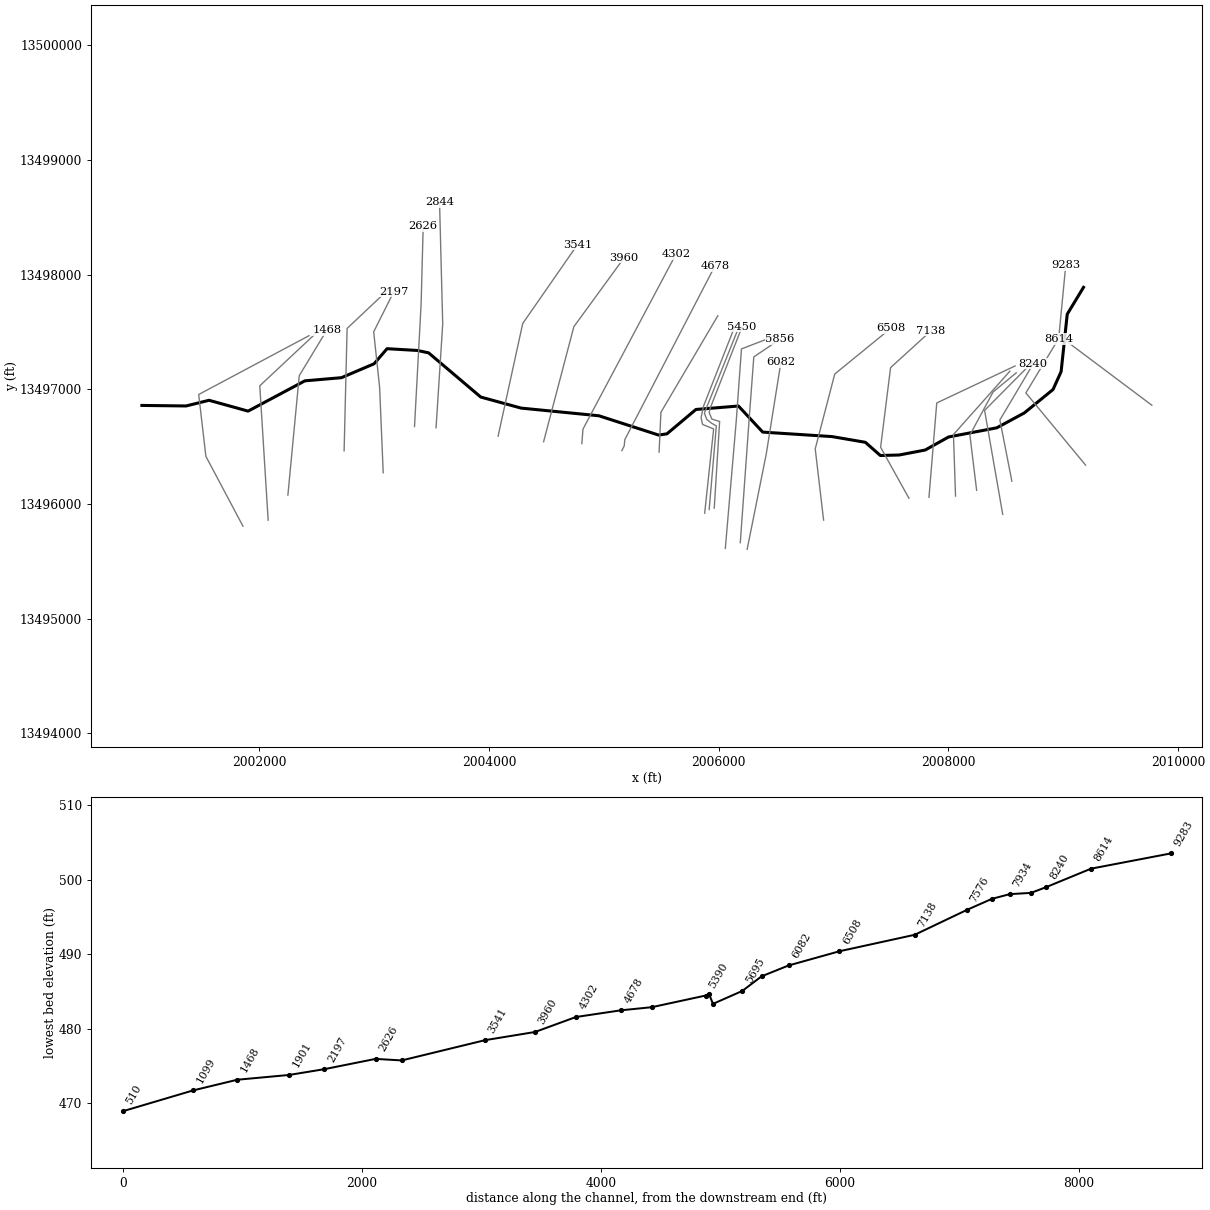
--- UNT 006 in RCW.prj (project) ---

Proj Title=UNT 006 in RCW Base Level Engineering
Current Plan=p01
Default Exp/Contr=0.3,0.1
English Units
Geom File=g01
Flow File=f01
Plan File=p01
Y Axis Title=Elevation
X Axis Title(PF)=Main Channel Distance
X Axis Title(XS)=Station
BEGIN DESCRIPTION:
UNT 006 in RCW
END DESCRIPTION:
DSS Export Rating Curves= 0
DSS Export Rating Curve Sorted= 0
DSS Export Volume Flow Curves= 0
DXF OffsetX= 0
DXF OffsetY= 0
DXF ScaleX= 1
DXF ScaleY= 10

--- UNT 006 in RCW.p01 (plan) ---

Plan Title=Multiple Run
Short Identifier=Multiple
Geom File=g01
Flow File=f01
Subcritical Flow
K Sum by GR= 0
Std Step Tol= 0.01
Critical Tol= 0.01
Num of Std Step Trials= 20
Max Error Tol= 0.3
Flow Tol Ratio= 0.001
Split Flow NTrial= 30
Split Flow Tol= 0.02
Split Flow Ratio= 0.02
Log Output Level= 0
Friction Slope Method= 1
Unsteady Friction Slope Method= 2
Unsteady Bridges Friction Slope Method= 1
Parabolic Critical Depth
Global Vel Dist=  1 , 1 , 1
Global Log Level= 0
CheckData=True
Encroach Param= -1, 0, 0, 0
BEGIN DESCRIPTION:
Multiple Run
END DESCRIPTION:

--- UNT 006 in RCW.f01 (steady flow) ---

Flow Title=Multiple
Number of Profiles=7
Profile Names=10-year,25-year,50-year,1pct_min,100-year,1pct_plu,500-year
River Rch & RM= UNT 006 in RCW,Reach-1,9283
     243     335     409     249     498     993     748
River Rch & RM= UNT 006 in RCW,Reach-1,510
     747    1075    1356     849    1694    3380    2688
Boundary for River Rch & Prof#=UNT 006 in RCW,Reach-1,1
Up Type=0
Dn Type=3
Dn Slope=0.005
Boundary for River Rch & Prof#=UNT 006 in RCW,Reach-1,2
Up Type=0
Dn Type=3
Dn Slope=0.005
Boundary for River Rch & Prof#=UNT 006 in RCW,Reach-1,3
Up Type=0
Dn Type=3
Dn Slope=0.005
Boundary for River Rch & Prof#=UNT 006 in RCW,Reach-1,4
Up Type=0
Dn Type=3
Dn Slope=0.005
Boundary for River Rch & Prof#=UNT 006 in RCW,Reach-1,5
Up Type=0
Dn Type=3
Dn Slope=0.005
Boundary for River Rch & Prof#=UNT 006 in RCW,Reach-1,6
Up Type=0
Dn Type=3
Dn Slope=0.005
Boundary for River Rch & Prof#=UNT 006 in RCW,Reach-1,7
Up Type=0
Dn Type=3
Dn Slope=0.005

--- UNT 006 in RCW.g01 (geometry) ---

Geom Title=Existing Conditions
Program Version=5.05

River Reach=UNT 006 in RCW  ,Reach-1
Reach XY= 30
       2009175.8     13497889.54      2009034.16     13497655.54
       2008980.8     13497154.54      2008910.51     13496998.44
       2008660.8     13496794.54       2008420.8     13496664.54
       2008000.8     13496584.54      2007797.18     13496470.77
       2007570.4     13496427.37      2007406.56     13496423.03
      2007276.35     13496538.04      2006985.55     13496587.96
      2006382.25     13496627.02       2006170.8     13496854.54
       2005800.8     13496824.54      2005548.09     13496611.87
      2005475.18     13496601.45      2004955.39     13496769.59
       2004278.3     13496836.43      2003926.74     13496932.79
      2003472.75      13497318.2      2003374.66     13497339.04
       2003110.8     13497354.54      2002998.06     13497223.03
      2002713.69     13497101.67      2002394.94     13497074.07
      2001900.67     13496810.01       2001560.8     13496904.54
      2001360.86     13496855.07       2000976.1     13496859.66

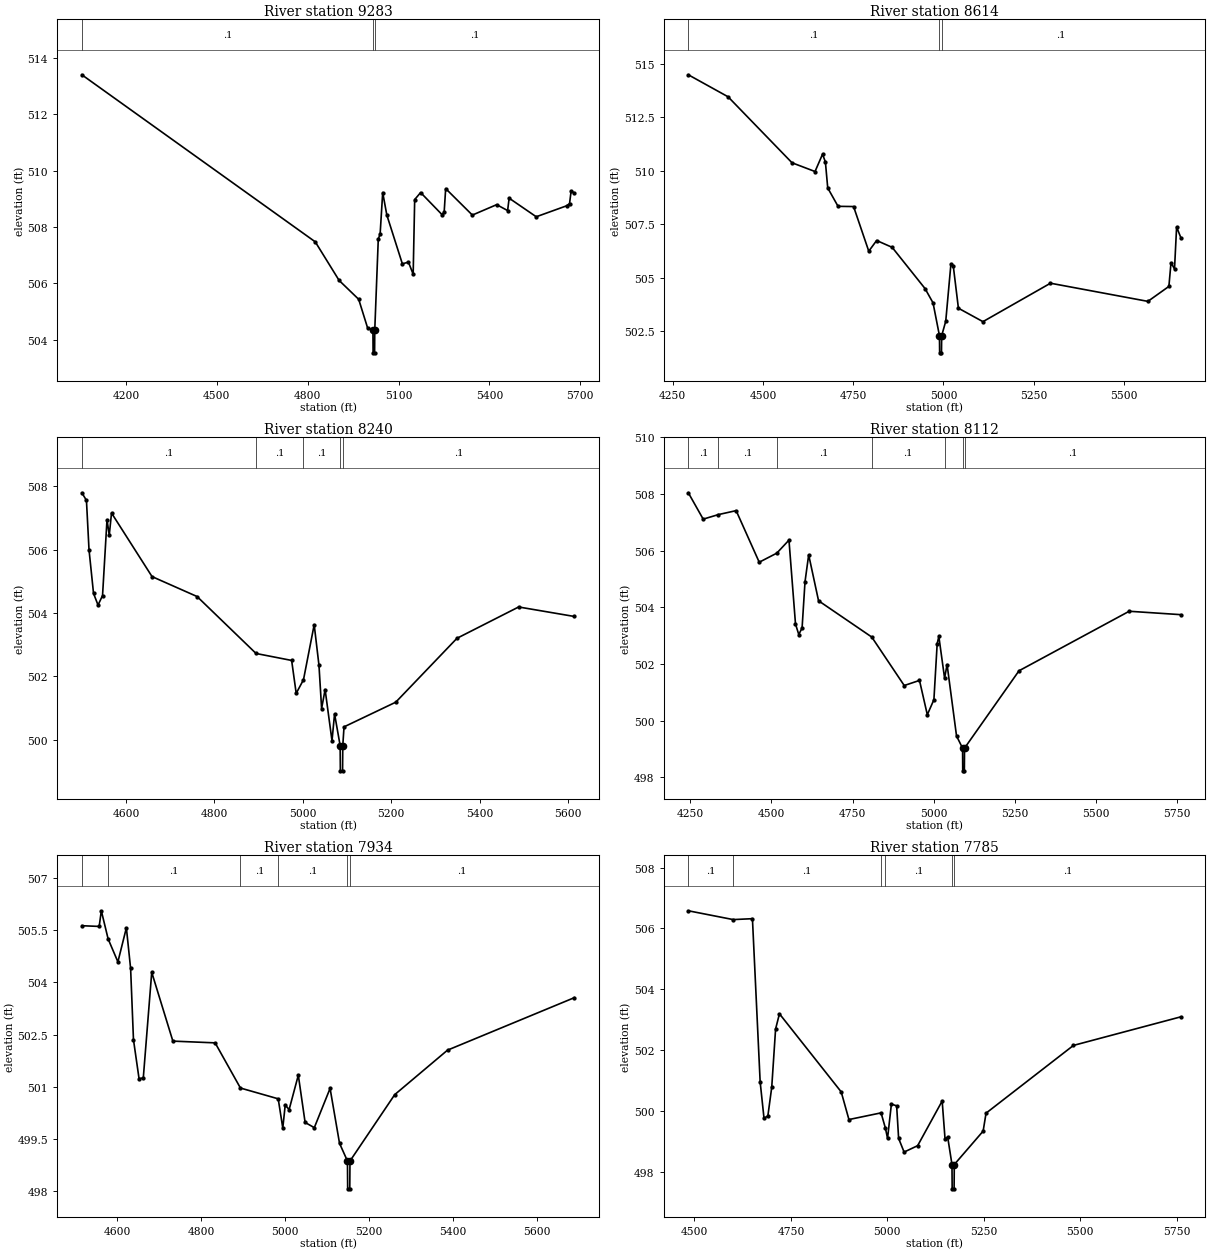
Type RM Length L Ch R = 1 ,9283    ,669,669,669
BEGIN DESCRIPTION:
UNT 006 in RCW 9.0
END DESCRIPTION:
XS GIS Cut Line= 3
      2009771.06     13496861.38      2008962.07     13497468.99
      2009021.09     13498080.08
#Sta/Elev= 30
  4054.7   513.4  4825.2  507.47    4904   506.1  4968.6  505.43  4997.8  504.42
  5015.6  504.33  5016.1  503.53  5021.1  503.53  5021.6  504.33  5033.2  507.56
  5039.4  507.76  5047.8  509.22  5061.5  508.42  5112.7  506.69  5132.8  506.75
  5148.4  506.32  5153.4  508.97    5173  509.22  5243.3  508.44  5250.7  508.52
  5255.7  509.36  5343.8  508.42  5424.1  508.79  5460.2  508.58  5465.2  509.02
  5554.7  508.36  5655.2  508.75  5664.6  508.83  5669.7  509.26  5680.4  509.21
#Mann= 3 ,-1 , 0
  4054.7      .1       0  5015.6    .035       0  5021.6      .1       0
Bank Sta=5015.6,5021.6
XS Rating Curve= 0 ,0
Exp/Cntr=0.3,0.1

Type RM Length L Ch R = 1 ,8614    ,374,374,374
BEGIN DESCRIPTION:
Mapping XS 95720d08
END DESCRIPTION:
XS GIS Cut Line= 3
      2009193.72     13496339.47      2008673.87     13496968.99
      2008956.88     13497438.46
#Sta/Elev= 30
  4293.1   514.5  4403.2  513.47  4580.4  510.38  4644.2  509.97    4665  510.78
  4672.9  510.42  4679.4   509.2    4708  508.34    4751  508.33  4793.1  506.24
  4814.9  506.74  4857.9  506.42    4949  504.49  4971.2  503.82    4989  502.28
  4989.5  501.48  4994.6  501.48  4995.1  502.28  5006.4  502.96  5020.7  505.63
  5027.2  505.56  5041.5  503.57  5109.5  502.94  5296.6  504.74  5566.5  503.89
  5624.7  504.59  5630.6   505.7  5640.3  505.41  5646.1  507.37  5657.7  506.88
#Mann= 3 ,-1 , 0
  4293.1      .1       0    4989    .035       0  4995.1      .1       0
Bank Sta=4989,4995.1
XS Rating Curve= 0 ,0
Exp/Cntr=0.3,0.1

Type RM Length L Ch R = 1 ,8240    ,128,128,128
BEGIN DESCRIPTION:
Mapping XS 6a2bfec5
END DESCRIPTION:
XS GIS Cut Line= 3
      2008551.87      13496199.1      2008447.69     13496732.99
      2008738.47     13497223.41
#Sta/Elev= 30
    4500   507.8  4510.4  507.56  4516.2     506  4526.4  504.62  4536.6  504.25
  4546.8  504.55  4556.9  506.95    4562  506.46  4567.1  507.16  4658.8  505.15
  4760.7  504.52  4894.1  502.72  4974.6   502.5  4984.9  501.46  5001.4  501.89
  5025.6  503.63  5036.4  502.35  5042.4  500.98  5050.3  501.58  5065.9  499.96
  5071.7  500.81  5084.3  499.81  5084.8  499.01  5089.8  499.01  5090.3  499.81
  5093.1   500.4  5210.1  501.18  5348.6   503.2  5488.1  504.19  5614.1  503.89
#Mann= 5 ,-1 , 0
    4500      .1       0  4894.1      .1       0  5001.4      .1       0
  5084.3     .07       0  5090.3      .1       0
Bank Sta=5084.3,5090.3
XS Rating Curve= 0 ,0
Exp/Cntr=0.3,0.1

Type RM Length L Ch R = 1 ,8112    ,178,178,178
BEGIN DESCRIPTION:
Mapping XS f593a4be
END DESCRIPTION:
XS GIS Cut Line= 3
      2008472.34     13495909.84      2008314.52     13496816.33
      2008734.39     13497240.27
#Sta/Elev= 30
  4244.1  508.04  4289.9  507.11  4336.6  507.27  4391.4  507.41  4462.5  505.59
  4516.6  505.91  4554.1  506.37  4574.2  503.41  4584.3  503.04  4594.5  503.27
  4603.5   504.9  4614.8  505.85  4645.2  504.23  4809.1  502.95  4909.1  501.24
  4956.1  501.42  4980.2  500.21  5000.5  500.74  5010.6  502.72  5015.7  502.97
  5033.4   501.5  5041.1  501.98  5070.2  499.46  5088.8  499.03  5089.3  498.23
  5094.3  498.23  5094.8  499.03  5262.6  501.76    5602  503.86  5760.9  503.74
#Mann= 7 ,-1 , 0
  4244.1      .1       0  4336.6      .1       0  4516.6      .1       0
  4809.1      .1       0  5033.4      .1       0  5088.8     .07       0
  5094.8      .1       0
Bank Sta=5088.8,5094.8
XS Rating Curve= 0 ,0
Exp/Cntr=0.3,0.1

Type RM Length L Ch R = 1 ,7934    ,149,149,149
BEGIN DESCRIPTION:
Mapping XS 351906bb
END DESCRIPTION:
XS GIS Cut Line= 4
      2008245.08      13496119.7      2008186.48     13496601.48
       2008388.3     13496976.92      2008590.05     13497143.95
#Sta/Elev= 30
  4515.8  505.63  4557.1  505.61  4562.2  506.06  4578.4  505.25  4601.7  504.59
  4621.9  505.57    4632   504.4  4638.8  502.35  4652.1  501.23  4662.2  501.25
  4682.3  504.29  4732.7  502.31  4833.4  502.26  4893.7  500.96  4983.7  500.65
  4994.6  499.81  5000.4  500.47  5009.7  500.34  5031.6  501.33  5047.8  499.97
  5069.7  499.82  5107.3  500.95  5129.8  499.37  5148.7  498.86  5149.2  498.06
  5154.2  498.06  5154.7  498.86  5261.3  500.77  5387.1  502.05  5689.3  503.56
#Mann= 6 ,-1 , 0
  4515.8      .1       0  4578.4      .1       0  4893.7      .1       0
  4983.7      .1       0  5148.7    .035       0  5154.7      .1       0
Bank Sta=5148.7,5154.7
XS Rating Curve= 0 ,0
Exp/Cntr=0.3,0.1

Type RM Length L Ch R = 1 ,7785    ,209,209,209
BEGIN DESCRIPTION:
Mapping XS d0580c1e
END DESCRIPTION:
XS GIS Cut Line= 3
      2008061.41     13496068.93      2008043.25     13496605.82
      2008534.48     13497158.32
#Sta/Elev= 30
  4484.1  506.58  4600.5  506.29  4650.3  506.32  4670.3  500.95  4680.3  499.75
  4690.3  499.83  4700.3  500.77  4710.3  502.69  4720.3  503.19  4880.4  500.62
  4900.4  499.71  4983.7  499.93  4995.1  499.42  5000.5  499.09  5010.5  500.22
  5024.1  500.16  5029.2  499.09  5043.4  498.64  5078.5  498.85  5142.1  500.32
  5149.6  499.06  5156.3  499.14  5167.5  498.23    5168  497.43    5173  497.43
  5173.5  498.23  5248.3  499.33  5255.8  499.92  5482.4  502.15  5760.6  503.09
#Mann= 6 ,-1 , 0
  4484.1      .1       0  4600.5      .1       0  4983.7      .1       0
  4995.1      .1       0  5167.5    .035       0  5173.5      .1       0
Bank Sta=5167.5,5173.5
XS Rating Curve= 0 ,0
Exp/Cntr=0.3,0.1

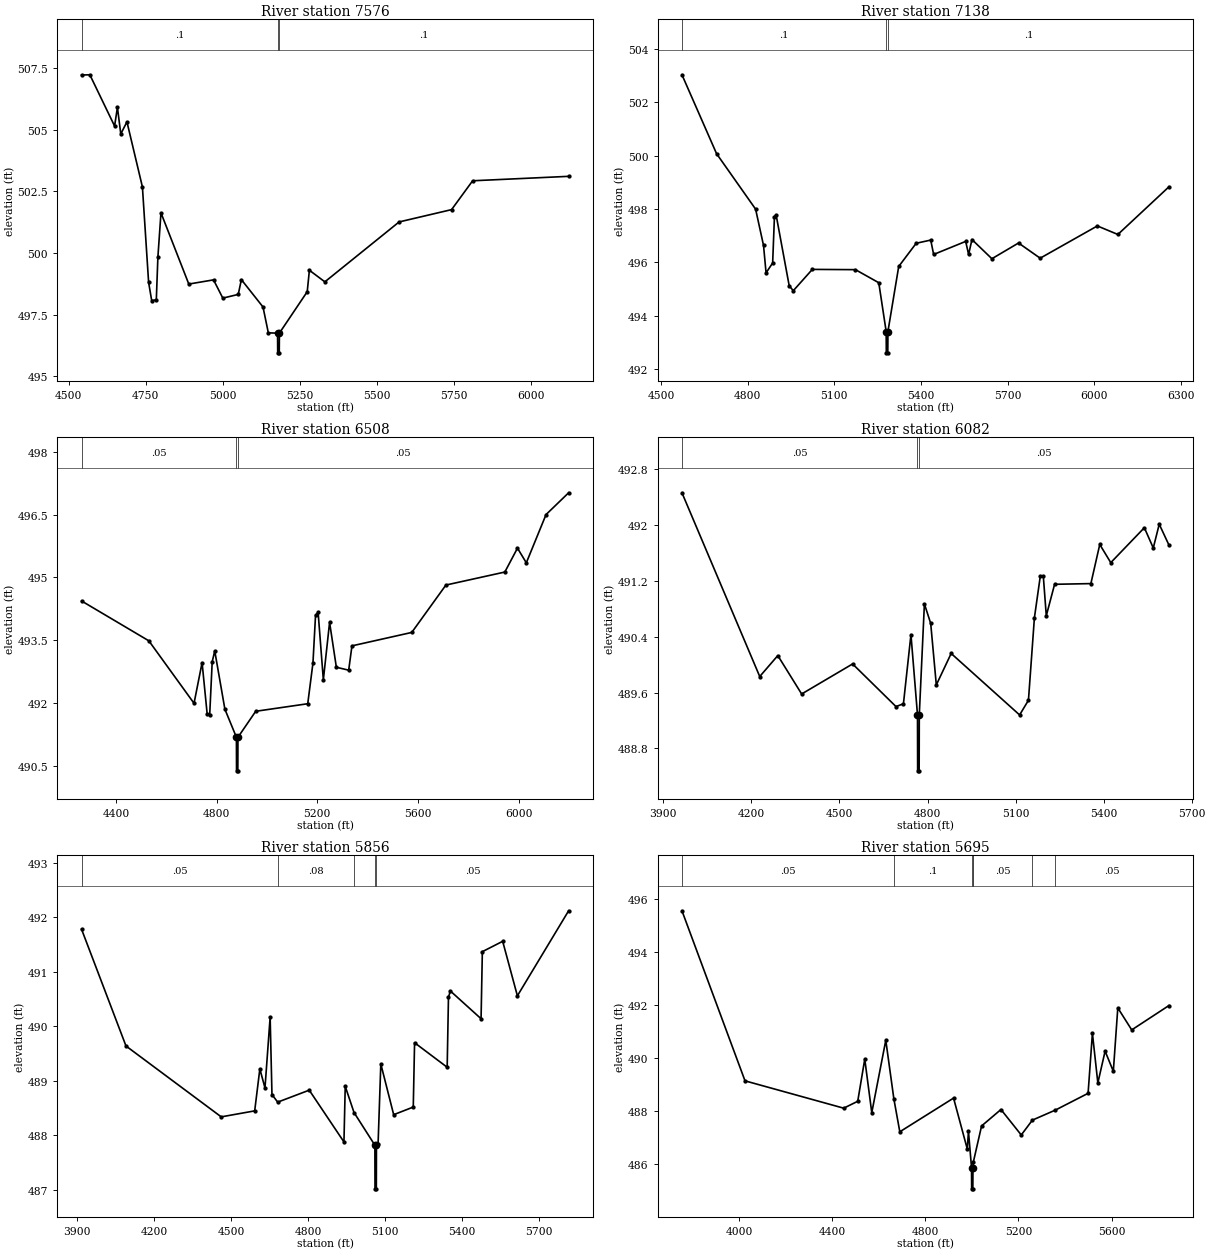
Type RM Length L Ch R = 1 ,7576    ,438,438,438
BEGIN DESCRIPTION:
Mapping XS 899d51ea
END DESCRIPTION:
XS GIS Cut Line= 3
      2007830.13     13496058.27      2007897.83     13496881.14
      2008580.03     13497204.01
#Sta/Elev= 30
  4541.5  507.22  4568.3  507.23  4648.6  505.15  4657.8  505.91  4668.7  504.83
  4688.7  505.32  4738.9  502.68    4759  498.81    4769  498.07    4784   498.1
  4789.1  499.83  4799.1  501.63  4889.4  498.74  4969.7  498.91  4999.8  498.17
  5049.9  498.32    5060  498.92  5130.2  497.81  5147.5  496.76  5177.4  496.75
  5177.9  495.95  5182.9  495.95  5183.4  496.75  5273.7  498.43  5280.7   499.3
  5330.9  498.83  5571.8  501.26  5742.1  501.76  5810.4  502.93  6121.9  503.11
#Mann= 3 ,-1 , 0
  4541.5      .1       0  5177.4     .05       0  5183.4      .1       0
Bank Sta=5177.4,5183.4
XS Rating Curve= 0 ,0
Exp/Cntr=0.3,0.1

Type RM Length L Ch R = 1 ,7138    ,630,630,630
BEGIN DESCRIPTION:
Mapping XS cb3eab16
END DESCRIPTION:
XS GIS Cut Line= 4
      2007655.49     13496050.46      2007408.98     13496494.87
      2007495.79     13497189.32      2007848.75     13497511.14
#Sta/Elev= 30
  4572.7  503.03  4692.5  500.07  4827.6  497.99    4855  496.63  4863.8   495.6
  4886.6  495.97  4892.8  497.71  4898.5  497.78  4943.8  495.12    4958  494.93
  5023.9  495.73  5173.2  495.72  5253.9  495.23  5279.5   493.4    5280   492.6
  5285.1   492.6  5285.6   493.4  5322.9  495.84  5383.4  496.71  5433.7  496.83
  5443.8  496.29  5554.7  496.78  5564.8  496.29  5576.4  496.85  5645.4  496.13
  5737.6  496.72  5812.5  496.15  6010.4  497.36  6081.4  497.04  6258.4  498.83
#Mann= 3 ,-1 , 0
  4572.7      .1       0  5279.5     .05       0  5285.6      .1       0
Bank Sta=5279.5,5285.6
XS Rating Curve= 0 ,0
Exp/Cntr=0.3,0.1

Type RM Length L Ch R = 1 ,6508    ,426,426,426
BEGIN DESCRIPTION:
Mapping XS cf6763ea
END DESCRIPTION:
XS GIS Cut Line= 4
      2006912.45     13495859.49      2006839.54     13496480.98
      2007009.68     13497133.76      2007501.34      13497535.4
#Sta/Elev= 30
  4263.4  494.44  4530.7  493.49  4710.2     492  4742.2  492.97  4762.3  491.75
  4772.4  491.72  4782.4  492.99  4792.5  493.25  4832.8  491.86  4878.6  491.19
  4879.1  490.39  4884.2  490.39  4884.7  491.19  4955.3  491.81    5162  491.99
  5182.7  492.96    5193   494.1  5203.2  494.17    5224  492.56  5248.8  493.93
  5275.7  492.86  5324.7  492.79  5337.7  493.37  5575.3  493.69    5711  494.82
  5945.1  495.13  5995.3   495.7  6030.5  495.35  6108.8   496.5  6198.6  497.02
#Mann= 3 ,-1 , 0
  4263.4     .05       0  4878.6    .035       0  4884.7     .05       0
Bank Sta=4878.6,4884.7
XS Rating Curve= 0 ,0
Exp/Cntr=0.3,0.1

Type RM Length L Ch R = 1 ,6082    ,226,226,226
BEGIN DESCRIPTION:
Mapping XS fa549b18
END DESCRIPTION:
XS GIS Cut Line= 3
      2006246.79     13495605.12      2006412.45     13496432.37
      2006540.93     13497237.92
#Sta/Elev= 30
  3963.4  492.46  4228.4  489.83    4290  490.13  4371.2  489.58  4544.8  490.01
  4692.6   489.4    4718  489.44  4743.6  490.43  4765.9  489.28  4766.4  488.48
  4771.5  488.48    4772  489.28  4789.4  490.87  4810.9  490.59    4830  489.71
  4880.6  490.16  5113.8  489.28  5143.9  489.49  5164.2  490.67  5184.4  491.27
  5194.5  491.27  5204.7   490.7    5233  491.15  5356.6  491.16  5386.9  491.72
  5424.4  491.46  5538.8  491.96  5569.2  491.67  5589.5  492.01  5622.8  491.71
#Mann= 3 ,-1 , 0
  3963.4     .05       0  4765.9    .035       0    4772     .05       0
Bank Sta=4765.9,4772
XS Rating Curve= 0 ,0
Exp/Cntr=0.3,0.1

Type RM Length L Ch R = 1 ,5856    ,161,161,161
BEGIN DESCRIPTION:
Mapping XS dc0a59d5
END DESCRIPTION:
XS GIS Cut Line= 4
      2006186.89     13495662.41      2006263.15     13496727.51
      2006304.82     13497283.07      2006530.28     13497435.69
#Sta/Elev= 30
  3917.2  491.78  4090.2  489.64  4461.2  488.34  4591.5  488.45  4611.6  489.22
  4631.6  488.87  4651.7  490.17  4658.8  488.75  4681.1  488.61    4804  488.83
  4939.2  487.88  4944.2   488.9  4978.4  488.42  5059.7  487.82  5060.2  487.02
  5065.3  487.02  5065.8  487.82  5072.2  487.85  5082.8  489.31  5132.9  488.38
  5209.2  488.52  5214.3   489.7  5341.3  489.25  5346.3  490.53  5353.5  490.65
  5473.3  490.14  5478.3  491.37  5557.5  491.56  5614.8  490.56  5814.4  492.12
#Mann= 5 ,-1 , 0
  3917.2     .05       0  4681.1     .08       0  4978.4     .05       0
  5059.7     .04       0  5065.8     .05       0
Bank Sta=5059.7,5065.8
XS Rating Curve= 0 ,0
Exp/Cntr=0.3,0.1

Type RM Length L Ch R = 1 ,5695    ,245,245,245
BEGIN DESCRIPTION:
Mapping XS 617998fa
END DESCRIPTION:
XS GIS Cut Line= 4
      2006056.68      13495612.9      2006152.04     13496727.51
      2006197.18     13497352.51      2006520.02     13497477.48
#Sta/Elev= 30
  3755.3  495.54  4026.1  489.13  4449.9   488.1  4510.1  488.36  4540.3  489.95
  4570.4  487.93  4630.6  490.66  4665.3  488.45  4690.8  487.21  4921.6  488.48
  4980.6  486.56  4985.6  487.23  4998.8  485.86  4999.3  485.06  5004.4  485.06
  5004.9  485.86  5006.6  486.07  5041.9  487.43  5125.2  488.05  5212.3  487.09
  5260.2  487.65  5359.3  488.03  5499.3  488.66  5517.9  490.92  5541.2  489.05
  5572.4  490.25  5607.7  489.49  5626.9  491.88  5686.7  491.05  5846.8  491.97
#Mann= 7 ,-1 , 0
  3755.3     .05       0  4665.3      .1       0  4998.8     .07       0
  5004.9      .1       0  5006.6     .05       0  5260.2      .1       0
  5359.3     .05       0
Bank Sta=4998.8,5004.9
XS Rating Curve= 0 ,0
Exp/Cntr=0.3,0.1

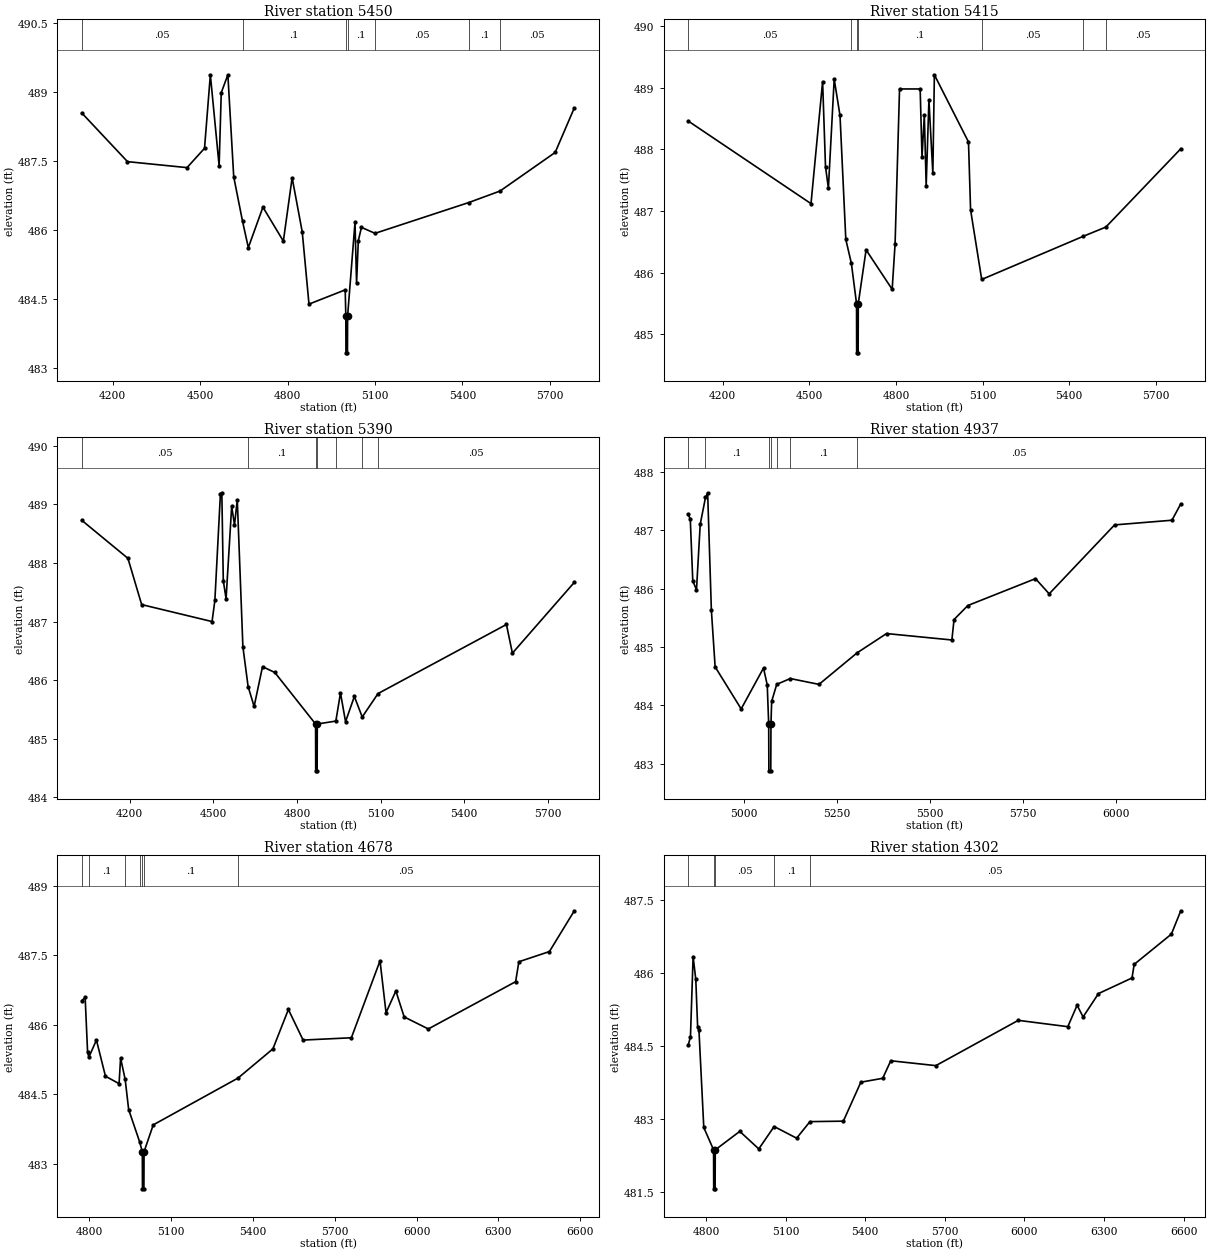
Type RM Length L Ch R = 1 ,5450    ,35,35,35
BEGIN DESCRIPTION:
Mapping XS 357d4959
END DESCRIPTION:
XS GIS Cut Line= 6
       2005960.2     13495964.53      2006007.07      13496719.7
      2005939.36     13496740.53      2005915.93     13496797.82
      2005926.34     13496839.49      2006202.38     13497545.21
#Sta/Elev= 30
  4093.6  488.55  4250.6  487.49  4454.8  487.36  4514.9  487.78  4534.9  489.38
    4565   487.4  4572.3  488.99    4595  489.38  4615.1  487.16  4645.4  486.19
  4665.2  485.62  4715.3   486.5  4785.4  485.76  4815.5  487.14  4850.2  485.96
  4873.3  484.39  4997.6   484.7  4999.7  484.13  5000.2  483.33  5005.3  483.33
  5005.8  484.13  5031.2  486.17  5036.6  484.85  5042.6  485.77  5053.3  486.06
  5099.9  485.93  5421.5   486.6  5528.7  486.85    5718  487.69  5783.7  488.66
#Mann= 7 ,-1 , 0
  4093.6     .05       0  4645.4      .1       0  4999.7     .07       0
  5005.8      .1       0  5099.9     .05       0  5421.5      .1       0
  5528.7     .05       0
Bank Sta=4999.7,5005.8
XS Rating Curve= 0 ,0
Exp/Cntr=0.3,0.1

Type RM Length L Ch R = 1 ,5415    ,25,25,25
BEGIN DESCRIPTION:
Mapping XS db437de8
END DESCRIPTION:
XS GIS Cut Line= 6
      2005915.92     13495951.44      2005978.43     13496680.63
      2005934.16     13496706.68      2005895.09     13496737.93
      2005874.26     13496792.61      2006176.35     13497547.84
#Sta/Elev= 30
  4080.9  488.46    4506  487.12  4546.2   489.1  4556.2  487.72  4566.2  487.37
  4586.3  489.14  4606.4  488.55  4626.5  486.54  4645.8  486.15  4663.6   485.5
  4664.1   484.7  4669.2   484.7  4669.7   485.5  4696.7  486.37    4787  485.73
  4797.1  486.47  4812.5  488.98  4883.9  488.98  4890.3  487.87  4898.3  488.56
  4904.7  487.41  4914.2   488.8  4927.8  487.61  4933.1  489.21  5051.2  488.12
  5058.4  487.02  5096.9  485.89  5448.4  486.59  5526.7  486.74  5786.1  488.01
#Mann= 7 ,-1 , 0
  4080.9     .05       0  4645.8      .1       0  4663.6     .07       0
  4669.7      .1       0  5096.9     .05       0  5448.4      .1       0
  5526.7     .05       0
Bank Sta=4663.6,4669.7
XS Rating Curve= 0 ,0
Exp/Cntr=0.3,0.1

Type RM Length L Ch R = 1 ,5390    ,453,453,453
BEGIN DESCRIPTION:
Mapping XS 94e9fe7c
END DESCRIPTION:
XS GIS Cut Line= 6
      2005876.86     13495920.19      2005954.99     13496654.59
      2005858.64     13496693.66      2005845.61     13496753.55
      2005866.45     13496852.51      2006144.43     13497561.74
#Sta/Elev= 30
    4028  488.73  4193.7  488.08  4242.9  487.29  4495.4     487  4505.5  487.36
  4525.4  489.18  4530.5   489.2  4535.7   487.7  4545.7  487.39  4565.8  488.97
  4575.9  488.65  4585.9  489.08    4606  486.57  4624.7  485.89  4646.3  485.55
  4676.4  486.23  4720.5  486.13  4866.7  485.25  4867.2  484.45  4872.3  484.45
  4872.8  485.25  4939.4   485.3    4956  485.78  4974.2  485.29  5005.8  485.72
    5034  485.37  5090.7  485.77  5551.2  486.95  5572.6  486.46  5794.7  487.67
#Mann= 7 ,-1 , 0
    4028     .05       0  4624.7      .1       0  4866.7     .03       0
  4872.8      .1       0  4939.4     .05       0    5034      .1       0
  5090.7     .05       0
Bank Sta=4866.7,4872.8
XS Rating Curve= 0 ,0
Exp/Cntr=0.3,0.1

Type RM Length L Ch R = 1 ,4937    ,259,259,259
BEGIN DESCRIPTION:
Mapping XS 7511c476
END DESCRIPTION:
XS GIS Cut Line= 3
      2005479.82     13496452.72      2005495.79     13496799.56
      2005991.35     13497641.66
#Sta/Elev= 30
  4849.4  487.27    4855  487.19  4861.7  486.13  4871.7  485.98  4881.7   487.1
  4895.9  487.56  4901.7  487.64  4911.7  485.63  4921.8  484.66  4991.8  483.94
  5051.9  484.64  5061.9  484.35  5065.8  483.68  5066.3  482.88  5071.4  482.88
  5071.9  483.68  5073.8  484.07  5087.4  484.36  5123.8  484.46    5201  484.36
  5303.5   484.9  5382.6  485.23  5558.3  485.12  5564.1  485.47  5601.2  485.71
  5783.1  486.17  5819.9  485.91  5995.7  487.09  6149.9  487.17  6173.7  487.45
#Mann= 7 ,-1 , 0
  4849.4     .05       0  4895.9      .1       0  5065.8     .07       0
  5071.9      .1       0  5087.4     .05       0  5123.8      .1       0
  5303.5     .05       0
Bank Sta=5065.8,5071.9
XS Rating Curve= 0 ,0
Exp/Cntr=0.3,0.1

Type RM Length L Ch R = 1 ,4678    ,376,376,376
BEGIN DESCRIPTION:
Mapping XS 99d69aab
END DESCRIPTION:
XS GIS Cut Line= 4
      2005155.94     13496465.85      2005176.17     13496506.56
      2005181.55     13496561.71      2005965.95     13498076.05
#Sta/Elev= 30
  4771.9  486.52  4784.4  486.59  4793.3  485.42    4798   485.3  4825.8  485.67
  4858.9  484.89  4908.8  484.73  4914.4  485.28  4931.2  484.82    4944  484.17
  4983.9  483.48  4994.1  483.26  4994.6  482.46  4999.9  482.46  5000.4  483.26
  5034.1  483.84    5345  484.85  5472.9  485.48  5529.7  486.33  5583.6  485.67
  5760.7  485.72  5865.7  487.38  5887.8  486.26  5923.8  486.73  5954.2  486.17
  6042.8  485.91    6363  486.93  6374.8  487.36  6486.9  487.58  6578.2  488.46
#Mann= 7 ,-1 , 0
  4771.9     .08       0    4798      .1       0  4931.2     .05       0
  4983.9      .1       0  4994.1     .07       0  5000.4      .1       0
    5345     .05       0
Bank Sta=4994.1,5000.4
XS Rating Curve= 0 ,0
Exp/Cntr=0.3,0.1

Type RM Length L Ch R = 1 ,4302    ,342,342,342
BEGIN DESCRIPTION:
Mapping XS 15c8a333
END DESCRIPTION:
XS GIS Cut Line= 3
      2004807.08     13496526.53      2004816.97     13496652.86
      2005627.33     13498180.06
#Sta/Elev= 30
  4733.4  484.51  4741.9  484.68  4751.9  486.33    4762  485.86  4768.9  484.89
  4773.9  484.82  4792.1  482.82    4829  482.36  4829.5  481.56  4834.8  481.56
  4835.3  482.36  4927.7  482.74  4999.3  482.38  5057.1  482.84  5141.9   482.6
    5192  482.94  5317.8  482.95  5383.8  483.75  5466.1  483.83  5496.5  484.19
  5666.3  484.09  5976.8  485.02  6163.4  484.89  6198.4  485.33    6221  485.09
    6279  485.57  6405.2  485.89  6413.5  486.17  6553.5  486.79    6589  487.27
#Mann= 5 ,-1 , 0
  4733.4     .05       0    4829     .03       0  4835.3     .05       0
  5057.1      .1       0    5192     .05       0
Bank Sta=4829,4835.3
XS Rating Curve= 0 ,0
Exp/Cntr=0.3,0.1

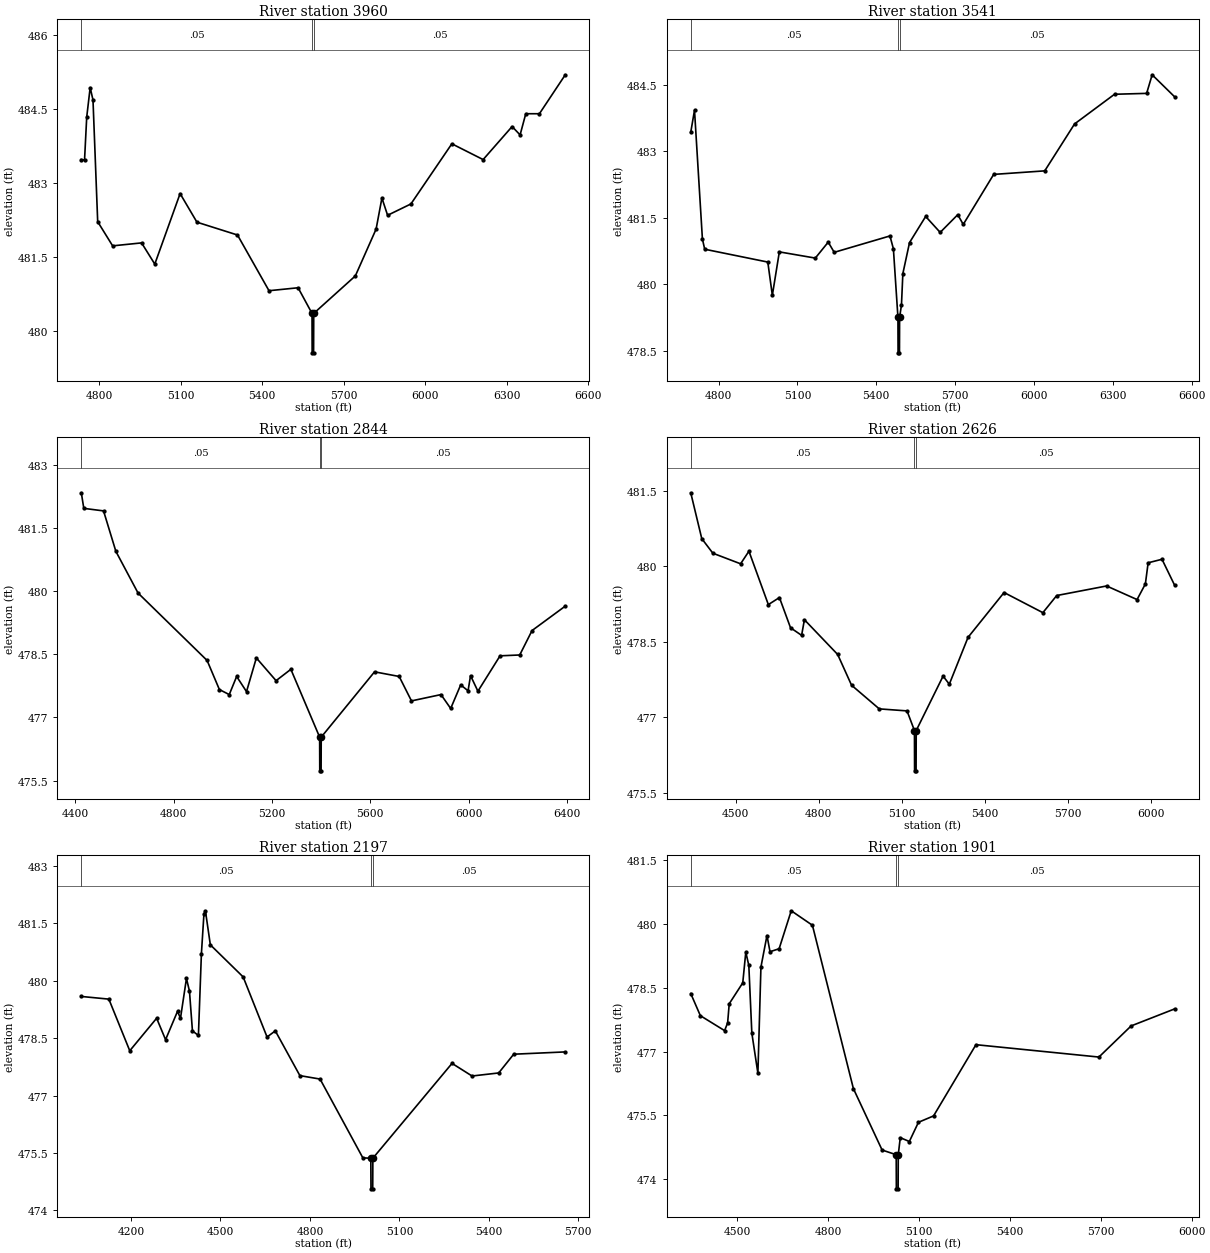
Type RM Length L Ch R = 1 ,3960    ,419,419,419
BEGIN DESCRIPTION:
Mapping XS 8f19349f
END DESCRIPTION:
XS GIS Cut Line= 3
      2004474.21     13496543.45      2004737.64     13497546.51
      2005175.59     13498147.61
#Sta/Elev= 30
    4735  483.47  4746.9  483.46  4754.9  484.33  4767.6  484.93    4778  484.68
  4795.3  482.21  4850.3  481.72  4956.8  481.78  5005.4  481.35  5098.5  482.78
  5160.5   482.2  5309.7  481.94  5425.6  480.81  5532.7  480.87  5583.9  480.35
  5584.4  479.55  5589.7  479.55  5590.2  480.35  5743.3  481.11  5819.7  482.06
  5841.1  482.69    5862  482.34  5947.8  482.57  6098.4  483.79  6213.5  483.47
  6320.1  484.14  6349.5  483.97  6370.4   484.4  6420.6   484.4  6515.8  485.19
#Mann= 3 ,-1 , 0
    4735     .05       0  5583.9     .03       0  5590.2     .05       0
Bank Sta=5583.9,5590.2
XS Rating Curve= 0 ,0
Exp/Cntr=0.3,0.1

Type RM Length L Ch R = 1 ,3541    ,697,697,697
BEGIN DESCRIPTION:
Mapping XS 113bf417
END DESCRIPTION:
XS GIS Cut Line= 3
      2004077.91     13496591.62      2004292.32     13497574.22
       2004768.6     13498261.13
#Sta/Elev= 30
    4694  483.43  4708.3  483.93  4738.4  481.02  4747.1  480.79  4987.2   480.5
  5004.5  479.75  5031.1  480.73    5168  480.59  5217.1  480.95  5239.9  480.72
    5452  481.09  5465.1   480.8  5482.4  479.25  5482.9  478.45  5488.2  478.45
  5488.7  479.25  5495.8  479.53  5501.1  480.24  5526.5  480.94  5587.9  481.53
  5643.1  481.17    5710  481.57  5730.9  481.35  5846.7  482.48    6041  482.56
  6154.5  483.62  6306.5  484.29  6428.7  484.31  6449.7  484.73  6535.6  484.23
#Mann= 3 ,-1 , 0
    4694     .05       0  5482.4     .03       0  5488.7     .05       0
Bank Sta=5482.4,5488.7
XS Rating Curve= 0 ,0
Exp/Cntr=0.3,0.1

Type RM Length L Ch R = 1 ,2844    ,218,218,218
BEGIN DESCRIPTION:
Mapping XS d453ebb1
END DESCRIPTION:
XS GIS Cut Line= 3
      2003537.55     13496664.82      2003595.61     13497569.52
      2003567.97      13498630.1
#Sta/Elev= 30
    4425  482.33  4435.2  481.96  4515.4   481.9  4565.5  480.94  4655.7  479.95
  4936.4  478.35  4986.3  477.66  5026.4  477.54  5056.5  477.97  5096.6  477.61
  5136.6  478.41  5216.8  477.87  5276.9  478.14  5393.9  476.53  5394.4  475.73
  5399.8  475.73  5400.3  476.53  5617.1  478.08  5717.2  477.97  5767.2  477.39
  5887.2  477.54  5926.6  477.21  5967.3  477.77  5997.3  477.63  6007.3  477.99
  6037.3  477.62  6127.3  478.46  6207.3  478.48  6257.4  479.06  6392.5  479.64
#Mann= 3 ,-1 , 0
    4425     .05       0  5393.9     .03       0  5400.3     .05       0
Bank Sta=5393.9,5400.3
XS Rating Curve= 0 ,0
Exp/Cntr=0.3,0.1

Type RM Length L Ch R = 1 ,2626    ,429,429,429
BEGIN DESCRIPTION:
Mapping XS df226d2c
END DESCRIPTION:
XS GIS Cut Line= 3
      2003350.05     13496675.24      2003407.38     13497742.25
      2003425.58     13498420.96
#Sta/Elev= 30
  4337.5  481.46  4377.3  480.55  4417.4  480.26  4517.5  480.05  4547.6   480.3
  4617.7  479.24  4657.7  479.38  4697.8  478.78  4737.8  478.63  4747.9  478.94
    4868  478.25  4918.1  477.64  5018.2  477.17  5118.4  477.13  5145.2  476.74
  5145.7  475.94  5151.1  475.94  5151.6  476.74  5248.6  477.82  5271.1  477.66
  5338.7  478.59  5468.8  479.48  5608.9  479.08  5658.9  479.42    5839  479.61
    5949  479.34    5979  479.65    5989  480.07    6039  480.14    6085  479.62
#Mann= 3 ,-1 , 0
  4337.5     .05       0  5145.2     .03       0  5151.6     .05       0
Bank Sta=5145.2,5151.6
XS Rating Curve= 0 ,0
Exp/Cntr=0.3,0.1

Type RM Length L Ch R = 1 ,2197    ,296,296,296
BEGIN DESCRIPTION:
Mapping XS 6e899b56
END DESCRIPTION:
XS GIS Cut Line= 4
      2003077.38     13496272.67      2003046.14     13497017.44
      2002994.44     13497501.49      2003169.36     13497850.93
#Sta/Elev= 30
  4033.3  479.59  4125.7  479.52  4195.8  478.17  4285.9  479.02  4315.9  478.46
  4355.9   479.2  4365.9  479.02  4385.9  480.06    4396  479.73    4406  478.69
    4426  478.57    4436   480.7  4444.5  481.74  4449.5  481.83    4466  480.94
  4576.1   480.1  4656.2  478.53  4683.9  478.69  4766.3  477.52    4834  477.43
  4977.4  475.37  5004.2  475.36  5004.7  474.56  5010.5  474.56    5011  475.36
  5276.5  477.84  5343.6  477.51    5433  477.59  5483.3  478.08  5656.3  478.14
#Mann= 3 ,-1 , 0
  4033.3     .05       0  5004.2     .03       0    5011     .05       0
Bank Sta=5004.2,5011
XS Rating Curve= 0 ,0
Exp/Cntr=0.3,0.1

Type RM Length L Ch R = 1 ,1901    ,433,433,433
BEGIN DESCRIPTION:
Mapping XS 392bd12d
END DESCRIPTION:
XS GIS Cut Line= 3
      2002736.89     13496463.23      2002762.93     13497530.92
      2003148.32     13497895.48
#Sta/Elev= 30
  4345.9  478.36  4377.7  477.84  4457.7  477.49  4467.7  477.67    4473  478.12
  4517.7  478.61  4527.7  479.33  4537.7  479.02  4547.7  477.43  4567.7  476.49
  4577.7  478.98  4597.7  479.72  4607.7  479.34  4637.8  479.41  4677.8   480.3
  4747.8  479.96  4883.1  476.13  4977.9  474.69  5024.5  474.58    5025  473.78
  5030.8  473.78  5031.3  474.58  5037.9  474.98  5067.9  474.89  5097.9  475.34
  5147.9  475.49  5287.9  477.16    5694  476.87  5800.4   477.6  5944.4     478
#Mann= 3 ,-1 , 0
  4345.9     .05       0  5024.5     .03       0  5031.3     .05       0
Bank Sta=5024.5,5031.3
XS Rating Curve= 0 ,0
Exp/Cntr=0.3,0.1

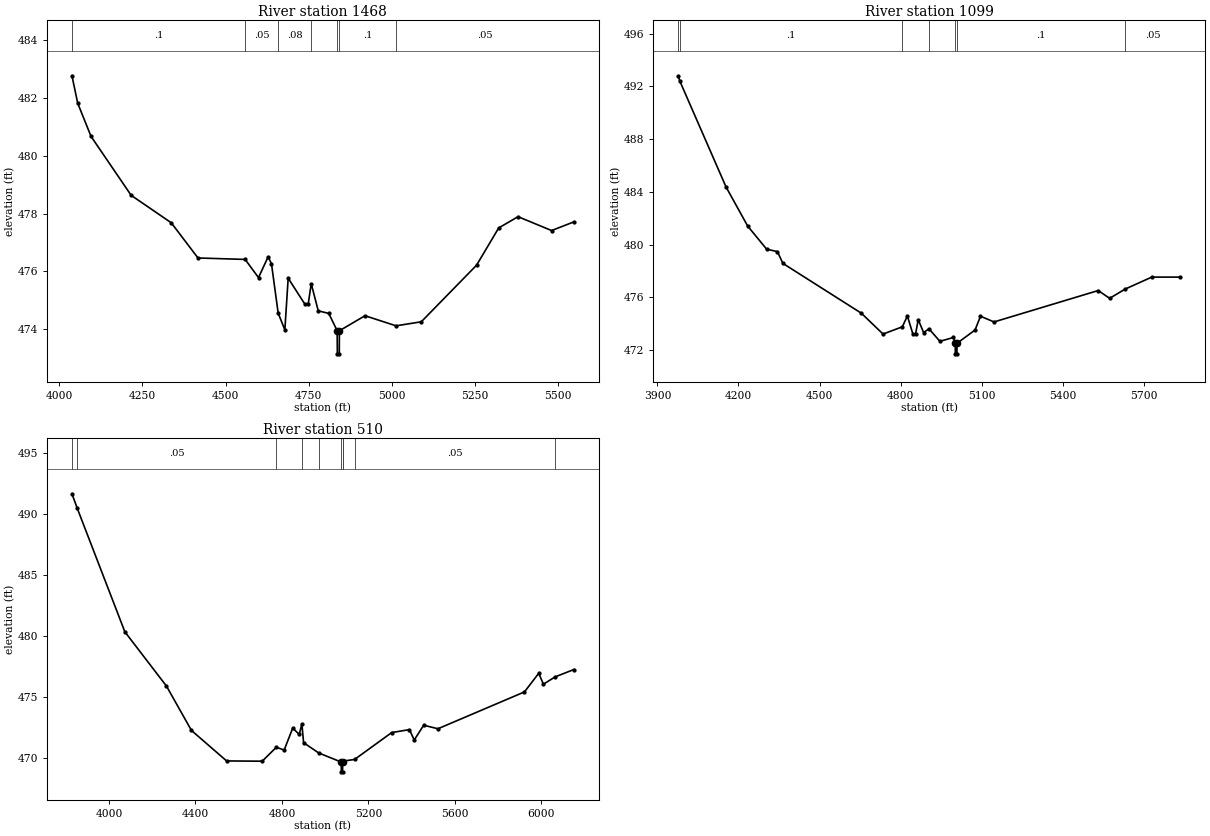
Type RM Length L Ch R = 1 ,1468    ,369,369,369
BEGIN DESCRIPTION:
Mapping XS 6ed19df6
END DESCRIPTION:
XS GIS Cut Line= 3
      2002247.31     13496077.81      2002346.27     13497119.46
      2002585.83     13497515.27
#Sta/Elev= 30
    4038  482.77  4055.3  481.82  4095.4  480.67    4216  478.63  4336.5  477.68
  4416.9  476.46  4558.7  476.41  4598.9  475.78  4627.8   476.5  4637.9  476.26
    4658  474.55  4678.1  473.97  4688.1  475.76  4738.3  474.86  4748.4  474.87
  4757.4  475.57  4778.5  474.63  4810.1  474.54  4835.4  473.94  4835.9  473.14
  4841.7  473.14  4842.2  473.94  4919.1  474.46  5012.5  474.11  5088.3  474.25
  5254.5  476.21    5321   477.5  5379.2  477.89  5480.1  477.41    5547  477.71
#Mann= 7 ,-1 , 0
    4038      .1       0  4558.7     .05       0    4658     .08       0
  4757.4      .1       0  4835.4     .07       0  4842.2      .1       0
  5012.5     .05       0
Bank Sta=4835.4,4842.2
XS Rating Curve= 0 ,0
Exp/Cntr=0.3,0.1

Type RM Length L Ch R = 1 ,1099    ,589,589,589
BEGIN DESCRIPTION:
Mapping XS 6cae3e2b
END DESCRIPTION:
XS GIS Cut Line= 3
      2002075.43     13495859.09      2002002.52     13497030.92
      2002501.23     13497498.47
#Sta/Elev= 30
  3977.7   492.8    3982  492.44  4153.9  484.37  4234.1   481.4  4304.2  479.65
  4344.3  479.46  4364.4  478.57  4654.9  474.79  4735.1  473.21  4806.4  473.76
  4825.2  474.58  4845.3  473.23  4855.3   473.2  4865.3   474.3  4885.4  473.32
    4905  473.61  4945.5  472.66  4995.6  472.95  5002.2  472.51  5002.7  471.71
  5008.5  471.71    5009  472.51  5075.7  473.52  5095.8  474.56  5145.9  474.13
  5531.4  476.51  5573.9  475.92    5631  476.62  5729.7  477.53  5835.4  477.53
#Mann= 7 ,-1 , 0
  3977.7     .05       0    3982      .1       0  4806.4     .05       0
    4905      .1       0  5002.2     .07       0    5009      .1       0
    5631     .05       0
Bank Sta=5002.2,5009
XS Rating Curve= 0 ,0
Exp/Cntr=0.3,0.1

Type RM Length L Ch R = 1 ,510     ,0,0,0
BEGIN DESCRIPTION:
UNT 006 in RCW 1.0
END DESCRIPTION:
XS GIS Cut Line= 4
      2001856.02     13495806.52      2001533.11     13496415.88
      2001470.61     13496954.94      2002431.14     13497467.86
#Sta/Elev= 30
  3829.1  491.63  3852.6  490.49  4073.8  480.35  4266.1  475.92  4381.9  472.29
  4544.4   469.8  4709.1  469.78  4774.4  470.92  4810.5  470.69  4850.1  472.48
  4880.3  471.97  4892.5  472.82  4900.4  471.29  4970.6  470.45  5074.4  469.71
  5074.9  468.91  5080.7  468.91  5081.2  469.71  5083.2  469.79  5136.1  469.92
  5307.9  472.12    5390  472.36    5412  471.51  5455.9  472.72  5521.7  472.43
  5921.8  475.44  5987.7  476.96  6009.6  476.07  6063.9  476.67  6150.3  477.27
#Mann= 10 ,-1 , 0
  3829.1     .05       0  3852.6     .05       0  4774.4     .05       0
  4892.5     .05       0  4970.6     .05       0  5074.4     .03       0
  5081.2     .05       0  5083.2     .05       0  5136.1     .05       0
  6063.9     .05       0
Bank Sta=5074.4,5081.2
XS Rating Curve= 0 ,0
Exp/Cntr=0.3,0.1
LCMann Table=0

Chan Stop Cuts=-1
Use User Specified Reach Order=0
Composite Channel Slope=5