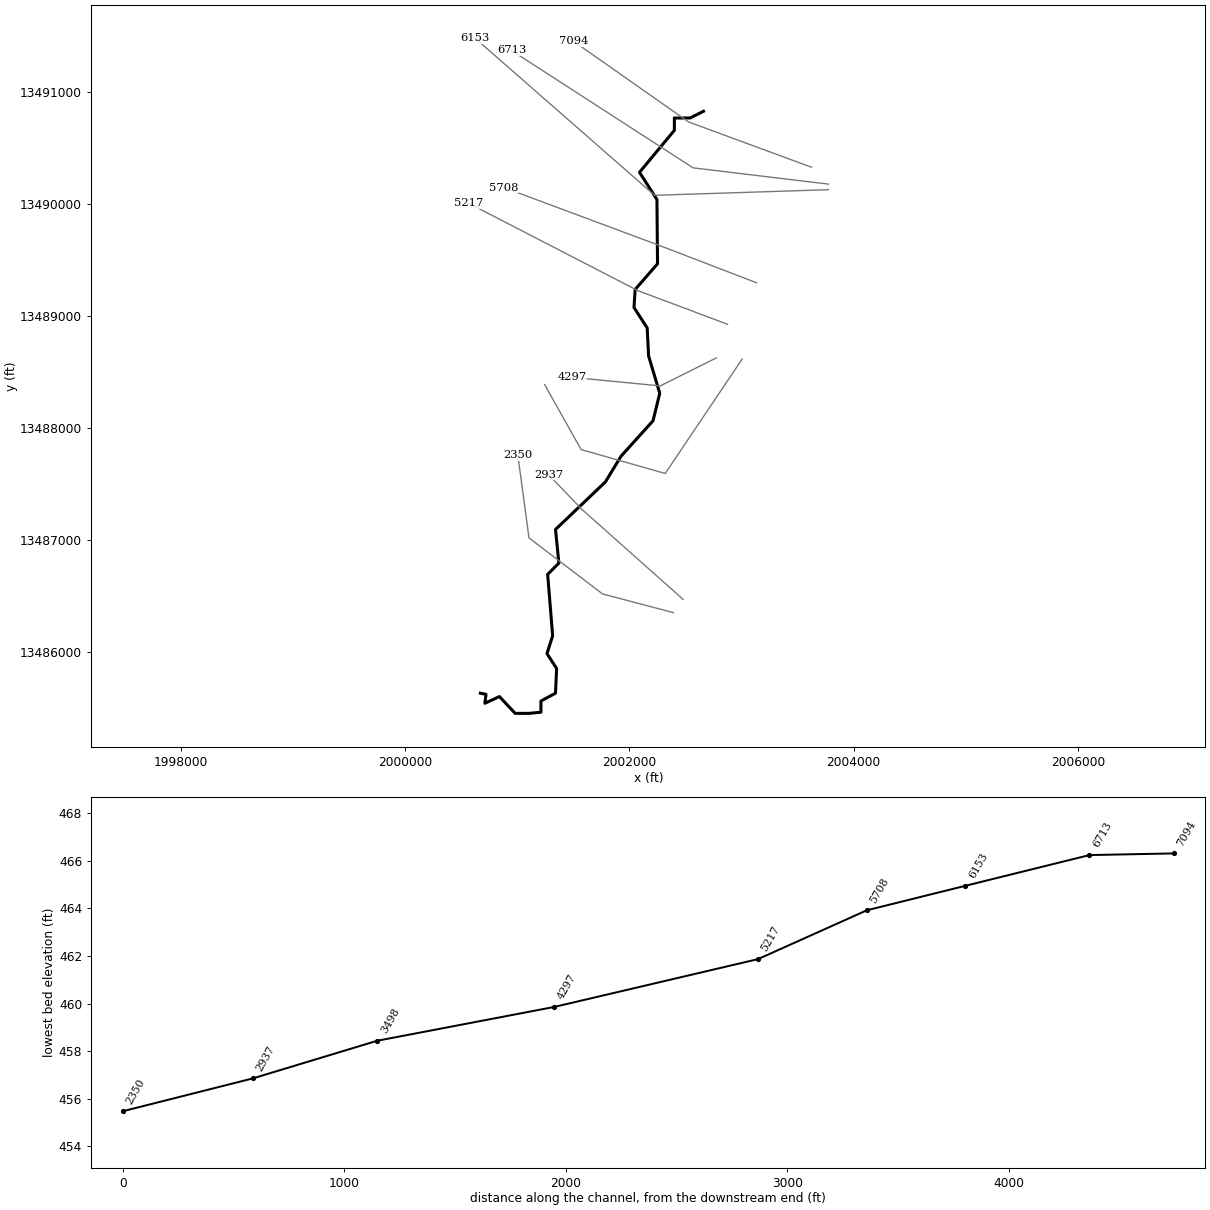
--- UNT 008 in RCW.prj (project) ---

Proj Title=UNT 008 in RCW Base Level Engineering
Current Plan=p01
Default Exp/Contr=0.3,0.1
English Units
Geom File=g01
Flow File=f01
Plan File=p01
BEGIN DESCRIPTION:
UNT 008 in RCW
END DESCRIPTION:

--- UNT 008 in RCW.p01 (plan) ---

Plan Title=Multiple Run
Short Identifier=Multiple
Geom File=g01
Flow File=f01
Subcritical Flow
K Sum by GR= 0
Std Step Tol= 0.01
Critical Tol= 0.01
Num of Std Step Trials= 20
Max Error Tol= 0.3
Flow Tol Ratio= 0.001
Split Flow NTrial= 30
Split Flow Tol= 0.02
Split Flow Ratio= 0.02
Log Output Level= 0
Friction Slope Method= 1
Unsteady Friction Slope Method= 2
Unsteady Bridges Friction Slope Method= 1
Parabolic Critical Depth
Global Vel Dist=  1 , 1 , 1
Global Log Level= 0
CheckData=True
Encroach Param= -1, 0, 0, 0
BEGIN DESCRIPTION:
Multiple Run
END DESCRIPTION:

--- UNT 008 in RCW.f01 (steady flow) ---

Flow Title=Multiple
Number of Profiles=7
Profile Names=10-year,25-year,50-year,1pct_min,100-year,1pct_plu,500-year
River Rch & RM= UNT 008 in RCW,Reach-1,7094
     255     353     435     267     532    1062     811
River Rch & RM= UNT 008 in RCW,Reach-1,5217
     280     389     479     294     587    1171     894
Boundary for River Rch & Prof#=UNT 008 in RCW,Reach-1,1
Up Type=0
Dn Type=3
Dn Slope=0.005
Boundary for River Rch & Prof#=UNT 008 in RCW,Reach-1,2
Up Type=0
Dn Type=3
Dn Slope=0.005
Boundary for River Rch & Prof#=UNT 008 in RCW,Reach-1,3
Up Type=0
Dn Type=3
Dn Slope=0.005
Boundary for River Rch & Prof#=UNT 008 in RCW,Reach-1,4
Up Type=0
Dn Type=3
Dn Slope=0.005
Boundary for River Rch & Prof#=UNT 008 in RCW,Reach-1,5
Up Type=0
Dn Type=3
Dn Slope=0.005
Boundary for River Rch & Prof#=UNT 008 in RCW,Reach-1,6
Up Type=0
Dn Type=3
Dn Slope=0.005
Boundary for River Rch & Prof#=UNT 008 in RCW,Reach-1,7
Up Type=0
Dn Type=3
Dn Slope=0.005

--- UNT 008 in RCW.g01 (geometry) ---

Geom Title=Existing Conditions

River Reach=UNT 008 in RCW,Reach-1
Reach XY= 30
      2002660.80     13490824.54      2002540.80     13490764.54
      2002400.80     13490764.54      2002400.80     13490654.54
      2002089.91     13490280.08      2002245.29     13490037.89
      2002250.80     13489464.54      2002050.80     13489234.54
      2002040.80     13489074.54      2002158.49     13488892.06
      2002170.80     13488642.93      2002270.46     13488309.59
      2002210.80     13488064.54      2001925.08     13487747.96
      2001785.76     13487518.80      2001340.80     13487094.54
      2001370.80     13486794.54      2001270.80     13486694.54
      2001315.34     13486146.04      2001264.65     13485987.70
      2001350.80     13485854.54      2001340.80     13485634.54
      2001210.80     13485564.54      2001210.80     13485464.54
      2001100.80     13485454.54      2000980.80     13485454.54
      2000840.80     13485604.54      2000710.80     13485544.54
      2000720.80     13485624.54      2000670.80     13485634.54

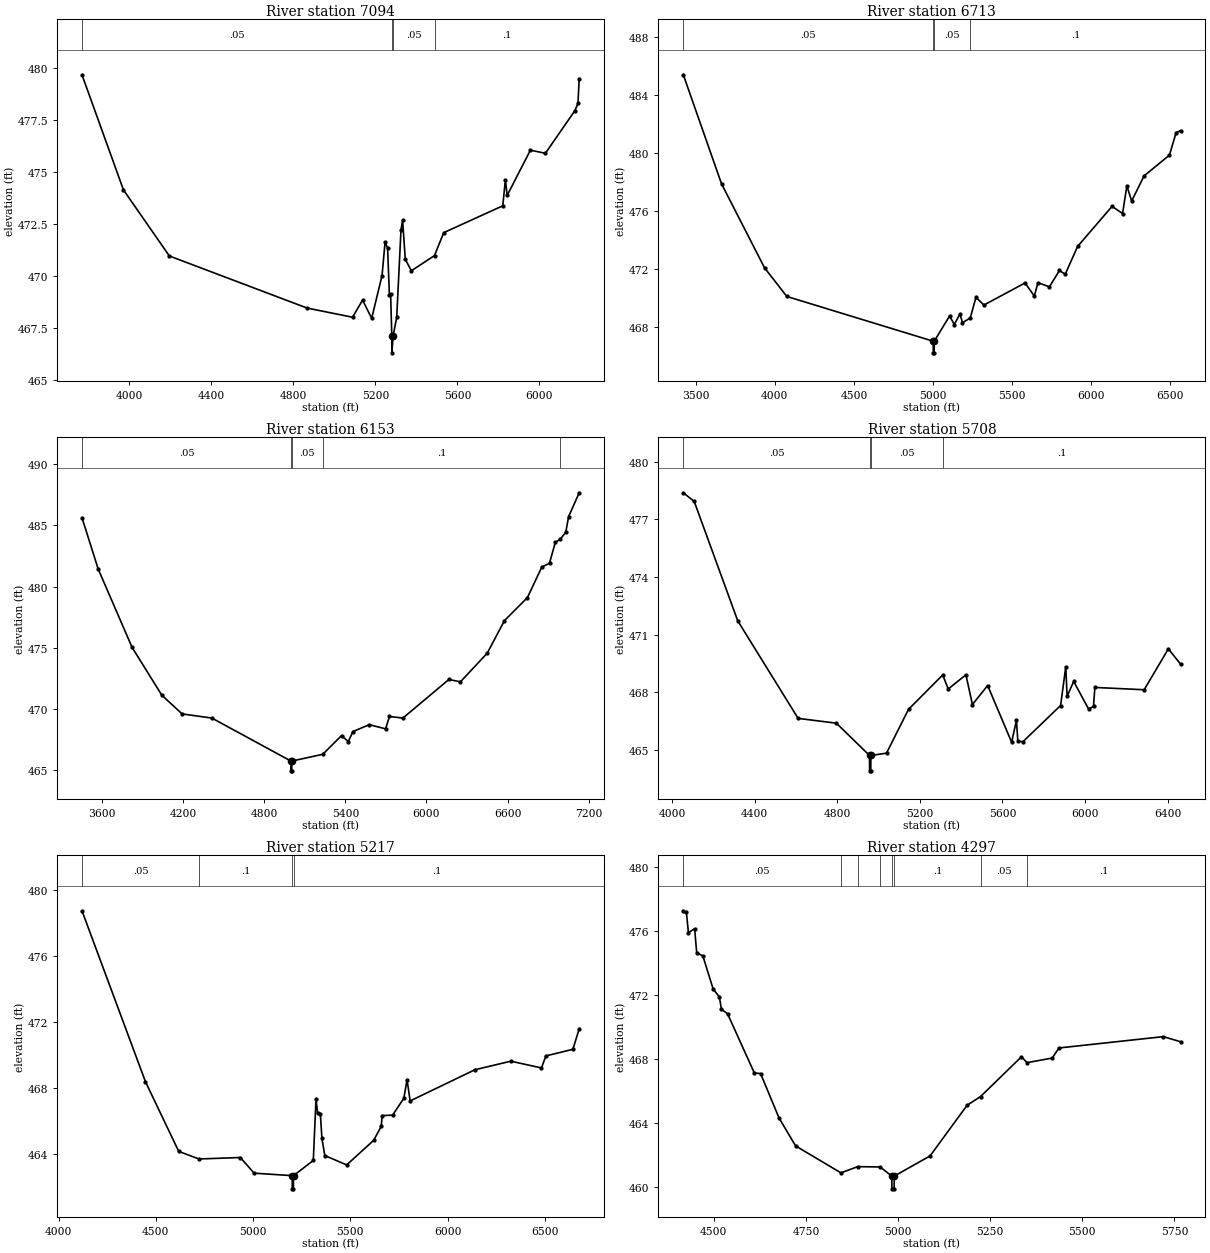
Type RM Length L Ch R = 1,7094,381,381,381
BEGIN DESCRIPTION:
UNT 008 in RCW 12.0
END DESCRIPTION:
XS GIS Cut Line= 3
      2003624.95     13490325.02      2002527.04     13490729.62
      2001499.99     13491450.01
#Sta/Elev= 30
  3769.1  479.66  3971.5  474.13  4195.3  470.96  4866.8  468.46  5088.3  468.02
  5137.3  468.84  5181.8  467.97  5232.3  470.02  5247.1  471.63  5259.3  471.34
  5268.1  469.11  5274.2  469.12  5279.9  467.11  5280.4  466.31  5285.9  467.11
  5303.8  468.01  5324.7  472.21  5332.6  472.67  5345.6  470.80  5375.3  470.25
  5488.1  470.98  5533.0  472.08  5821.1  473.37  5833.7  474.62  5842.4  473.87
  5955.7  476.04  6028.8  475.89  6172.8  477.94  6187.6  478.29  6193.7  479.48
#Mann=4,-1,0
  3769.1    0.05       0  5279.9   0.035       0  5285.9    0.05       0
  5488.1     0.1       0
Bank Sta=5279.9,5285.9
Exp/Cntr=0.3,0.1

Type RM Length L Ch R = 1,6713,560,560,560
BEGIN DESCRIPTION:
UNT 008 in RCW 11.0
END DESCRIPTION:
XS GIS Cut Line= 3
      2003775.05     13490174.99      2002567.84     13490319.90
      2000948.62     13491366.71
#Sta/Elev= 30
  3421.3  485.38  3663.1  477.87  3935.0  472.09  4076.0  470.12  5001.4  467.04
  5001.9  466.24  5007.5  466.24  5008.0  467.04  5105.0  468.78  5134.7  468.19
  5171.0  468.93  5186.1  468.31  5235.7  468.64  5271.7  470.06  5322.1  469.53
  5582.0  471.05  5640.8  470.15  5663.8  471.07  5736.1  470.78  5799.7  471.91
  5835.9  471.65  5914.7  473.57  6132.1  476.32  6198.8  475.83  6225.8  477.73
  6256.1  476.69  6334.7  478.42  6495.0  479.85  6537.2  481.40  6565.3  481.53
#Mann=4,-1,0
  3421.3    0.05       0  5001.4    0.03       0  5008.0    0.05       0
  5235.7     0.1       0
Bank Sta=5001.4,5008
Exp/Cntr=0.3,0.1

Type RM Length L Ch R = 1,6153,445,445,445
BEGIN DESCRIPTION:
UNT 008 in RCW 10.0
END DESCRIPTION:
XS GIS Cut Line= 3
      2003774.98     13490125.00      2002225.00     13490075.00
      2000625.01     13491474.99
#Sta/Elev= 30
  3452.5  485.63  3572.5  481.43  3822.7  475.04  4042.8  471.13  4192.9  469.60
  4413.0  469.26  4997.5  465.75  4998.0  464.95  5003.6  464.95  5004.1  465.75
  5233.0  466.30  5372.0  467.83  5421.4  467.34  5456.5  468.16  5577.0  468.72
  5697.6  468.38  5726.0  469.39  5825.7  469.26  6165.5  472.41  6250.9  472.22
  6449.3  474.56  6576.5  477.22  6746.3  479.10  6852.6  481.59  6909.6  481.91
  6952.3  483.60  6990.6  483.88  7030.1  484.45  7051.0  485.72  7129.3  487.66
#Mann=5,-1,0
  3452.5    0.05       0  4997.5   0.035       0  5004.1    0.05       0
  5233.0     0.1       0  6990.6    0.05       0
Bank Sta=4997.5,5004.1
Exp/Cntr=0.3,0.1

Type RM Length L Ch R = 1,5708,491,491,491
BEGIN DESCRIPTION:
UNT 008 in RCW 9.0
END DESCRIPTION:
XS GIS Cut Line= 3
      2003134.28     13489294.71      2002275.00     13489625.00
      2000879.73     13490144.45
#Sta/Elev= 30
  4053.6  478.39  4106.4  477.94  4317.2  471.73  4609.9  466.65  4795.2  466.40
  4955.8  464.72  4956.3  463.92  4962.0  463.92  4962.5  464.72  5038.2  464.84
  5144.9  467.12  5310.5  468.91  5337.4  468.18  5423.1  468.92  5454.4  467.37
  5528.4  468.36  5644.4  465.41  5667.8  466.54  5674.7  465.45  5699.7  465.44
  5881.8  467.32  5906.8  469.34  5913.2  467.80  5945.2  468.57  6017.4  467.14
  6041.2  467.27  6047.8  468.26  6286.7  468.14  6404.0  470.27  6463.0  469.47
#Mann=4,-1,0
  4053.6    0.05       0  4955.8   0.035       0  4962.5    0.05       0
  5310.5     0.1       0
Bank Sta=4955.8,4962.5
Exp/Cntr=0.3,0.1

Type RM Length L Ch R = 1,5217,920,920,920
BEGIN DESCRIPTION:
UNT 008 in RCW 8.0
END DESCRIPTION:
XS GIS Cut Line= 3
      2002874.96     13488925.02      2002075.00     13489225.00
      2000562.65     13490005.65
#Sta/Elev= 30
  4120.6  478.73  4447.2  468.36  4618.1  464.14  4722.1  463.68  4934.9  463.77
  5005.4  462.82  5201.4  462.67  5201.9  461.87  5207.6  461.87  5208.1  462.67
  5309.9  463.59  5323.8  467.32  5332.1  466.46  5346.3  466.40  5354.2  464.93
  5368.8  463.89  5481.4  463.32  5620.1  464.81  5658.8  465.65  5664.4  466.31
  5717.7  466.34  5775.2  467.36  5791.7  468.49  5807.7  467.20  6140.5  469.09
  6325.4  469.61  6482.9  469.20  6505.5  469.93  6644.5  470.33  6676.9  471.58
#Mann=4,-1,0
  4120.6    0.05       0  4722.1     0.1       0  5201.4    0.07       0
  5208.1     0.1       0
Bank Sta=5201.4,5208.1
Exp/Cntr=0.3,0.1

Type RM Length L Ch R = 1,4297,799,799,799
BEGIN DESCRIPTION:
UNT 008 in RCW 7.0
END DESCRIPTION:
XS GIS Cut Line= 3
      2002774.96     13488624.98      2002275.00     13488375.00
      2001488.50     13488451.71
#Sta/Elev= 30
  4417.4  477.27  4425.7  477.18  4431.3  475.90  4448.1  476.15  4453.7  474.65
  4470.5  474.44  4498.4  472.37  4515.2  471.88  4520.8  471.11  4537.5  470.82
  4610.2  467.11  4627.0  467.08  4677.3  464.29  4722.0  462.55  4845.1  460.86
  4890.7  461.25  4951.5  461.23  4983.0  460.66  4983.5  459.86  4989.4  459.86
  4989.9  460.66  5086.9  461.92  5187.4  465.09  5224.0  465.64  5335.0  468.13
  5350.0  467.76  5418.5  468.05  5436.7  468.68  5719.9  469.39  5766.6  469.07
#Mann=8,-1,0
  4417.4    0.05       0  4845.1     0.1       0  4890.7    0.05       0
  4951.5     0.1       0  4983.0    0.07       0  4989.9     0.1       0
  5224.0    0.05       0  5350.0     0.1       0
Bank Sta=4983,4989.9
Exp/Cntr=0.3,0.1

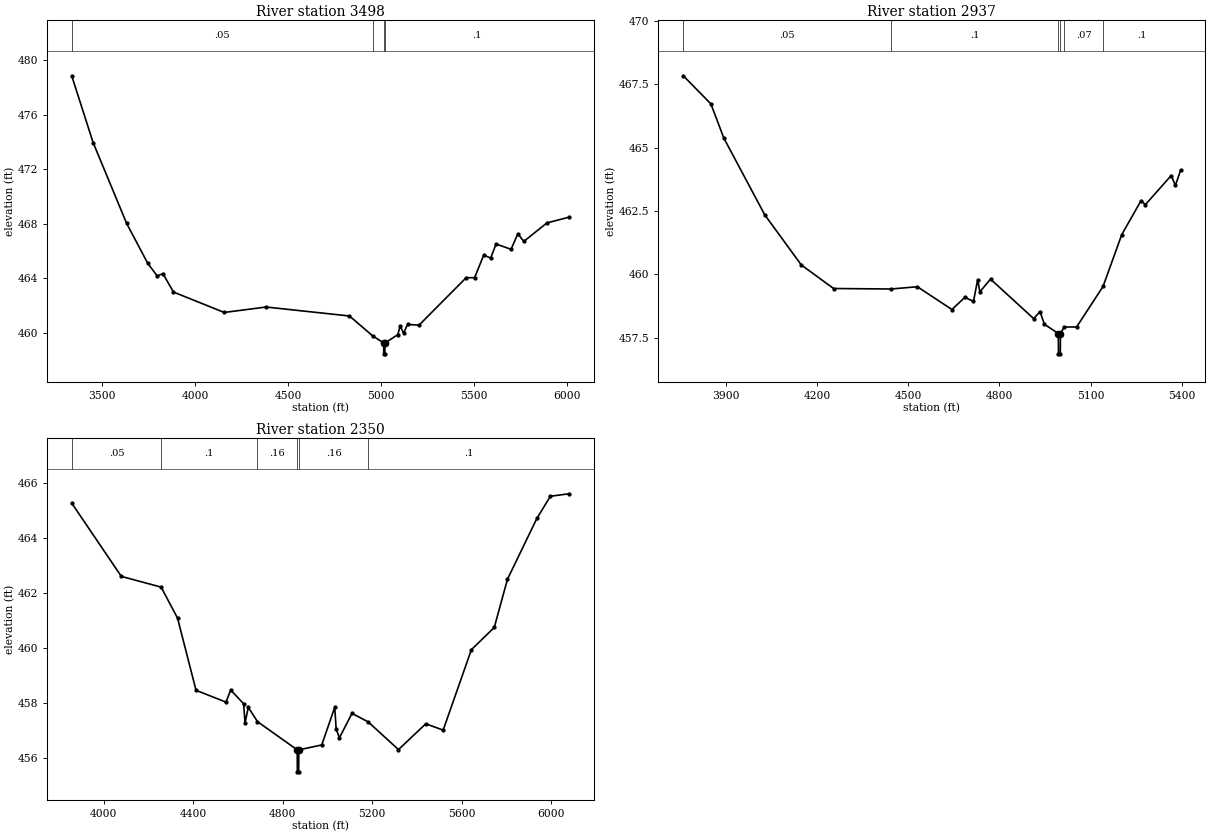
Type RM Length L Ch R = 1,3498,561,561,561
BEGIN DESCRIPTION:
UNT 008 in RCW 6.0
END DESCRIPTION:
XS GIS Cut Line= 4
      2003005.17     13488614.17      2002319.40     13487594.21
      2001568.92     13487807.29      2001244.06     13488386.73
#Sta/Elev= 30
  3335.6  478.87  3450.7  473.96  3630.7  468.03  3744.7  465.08  3795.7  464.16
  3825.7  464.34  3882.7  462.98  4155.7  461.48  4380.7  461.88  4829.1  461.22
  4952.8  459.77  5012.8  459.24  5013.3  458.44  5019.2  458.44  5019.7  459.24
  5089.0  459.85  5101.5  460.49  5120.2  459.95  5141.0  460.60  5203.2  460.55
  5456.8  464.04  5501.6  464.03  5550.7  465.69  5588.3  465.48  5617.3  466.51
  5697.6  466.12  5734.4  467.26  5766.3  466.70  5890.7  468.06  6009.1  468.48
#Mann=4,-1,0
  3335.6    0.05       0  4952.8     0.1       0  5012.8    0.07       0
  5019.7     0.1       0
Bank Sta=5012.8,5019.7
Exp/Cntr=0.3,0.1

Type RM Length L Ch R = 1,2937,587,587,587
BEGIN DESCRIPTION:
UNT 008 in RCW 5.0
END DESCRIPTION:
XS GIS Cut Line= 3
      2002479.29     13486470.94      2001575.00     13487275.00
      2001279.37     13487583.16
#Sta/Elev= 30
  3759.0  467.84  3849.8  466.73  3892.4  465.38  4027.1  462.35  4147.5  460.37
  4253.7  459.44  4442.6  459.42  4529.6  459.51  4643.4  458.61  4686.0  459.09
  4714.4  458.93  4728.2  459.79  4735.3  459.31  4770.5  459.81  4912.6  458.25
  4933.5  458.53  4947.7  458.03  4993.7  457.66  4994.2  456.86  5000.2  456.86
  5000.7  457.66  5013.2  457.92  5053.8  457.92  5140.9  459.52  5202.6  461.57
  5266.1  462.91  5280.2  462.75  5365.2  463.90  5379.3  463.51  5396.1  464.11
#Mann=6,-1,0
  3759.0    0.05       0  4442.6     0.1       0  4993.7    0.07       0
  5000.7     0.1       0  5013.2    0.07       0  5140.9     0.1       0
Bank Sta=4993.7,5000.7
Exp/Cntr=0.3,0.1

Type RM Length L Ch R = 1,2350,0,0,0
BEGIN DESCRIPTION:
UNT 008 in RCW 4.0
END DESCRIPTION:
XS GIS Cut Line= 4
      2002392.46     13486352.89      2001760.54     13486519.55
      2001104.29     13487019.55      2001004.95     13487757.35
#Sta/Elev= 30
  3856.5  465.27  4078.3  462.60  4256.2  462.21  4329.6  461.08  4412.3  458.45
  4546.1  458.02  4567.3  458.46  4625.1  457.96  4631.3  457.26  4645.9  457.83
  4686.9  457.31  4864.7  456.28  4865.2  455.48  4871.2  455.48  4871.7  456.28
  4974.3  456.46  5032.4  457.83  5038.7  457.04  5053.3  456.72  5109.5  457.61
  5181.8  457.30  5317.3  456.29  5439.3  457.23  5517.1  457.00  5643.2  459.93
  5745.6  460.74  5804.7  462.50  5935.9  464.71  5996.4  465.52  6079.5  465.61
#Mann=6,-1,0
  3856.5    0.05       0  4256.2     0.1       0  4686.9    0.16       0
  4864.7    0.07       0  4871.7    0.16       0  5181.8     0.1       0
Bank Sta=4864.7,4871.7
Exp/Cntr=0.3,0.1

Chan Stop Cuts=-1