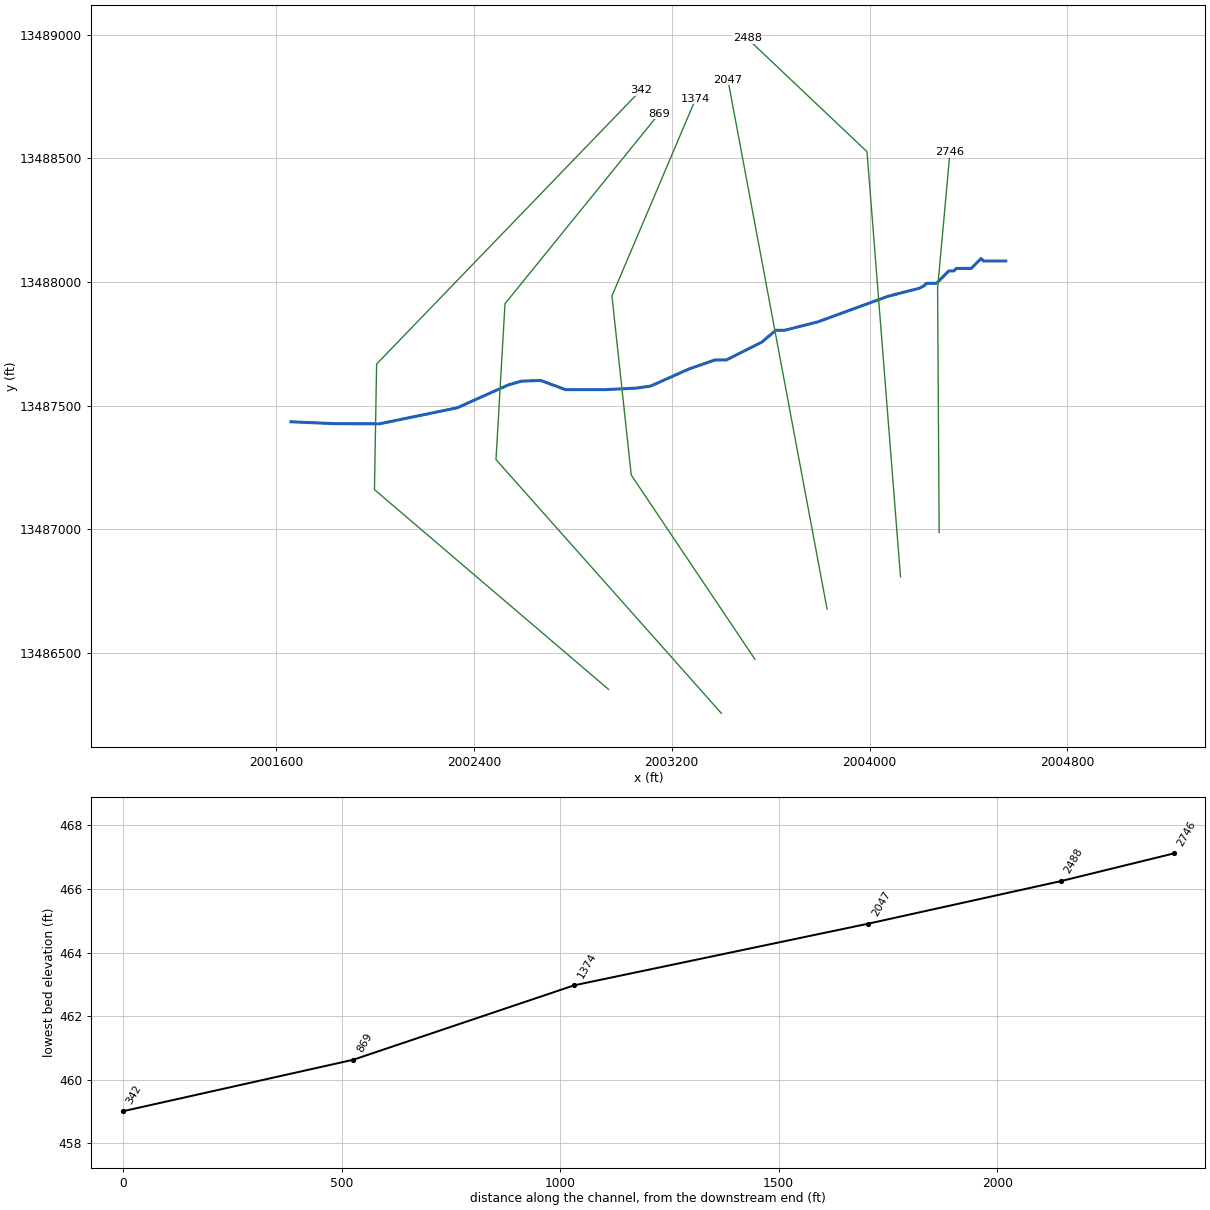
--- UNT 009 in RCW.prj (project) ---

Proj Title=UNT 009 in RCW Base Level Engineering
Current Plan=p01
Default Exp/Contr=0.3,0.1
English Units
Geom File=g01
Flow File=f01
Plan File=p01
Y Axis Title=Elevation
X Axis Title(PF)=Main Channel Distance
X Axis Title(XS)=Station
BEGIN DESCRIPTION:
UNT 009 in RCW
END DESCRIPTION:
DSS Export Rating Curves= 0
DSS Export Rating Curve Sorted= 0
DSS Export Volume Flow Curves= 0
DXF OffsetX= 0
DXF OffsetY= 0
DXF ScaleX= 1
DXF ScaleY= 10

--- UNT 009 in RCW.p01 (plan) ---

Plan Title=Multiple Run
Short Identifier=Multiple
Geom File=g01
Flow File=f01
Subcritical Flow
K Sum by GR= 0
Std Step Tol= 0.01
Critical Tol= 0.01
Num of Std Step Trials= 20
Max Error Tol= 0.3
Flow Tol Ratio= 0.001
Split Flow NTrial= 30
Split Flow Tol= 0.02
Split Flow Ratio= 0.02
Log Output Level= 0
Friction Slope Method= 1
Unsteady Friction Slope Method= 2
Unsteady Bridges Friction Slope Method= 1
Parabolic Critical Depth
Global Vel Dist=  1 , 1 , 1
Global Log Level= 0
CheckData=True
Encroach Param= -1, 0, 0, 0
BEGIN DESCRIPTION:
Multiple Run
END DESCRIPTION:

--- UNT 009 in RCW.f01 (steady flow) ---

Flow Title=Multiple
Number of Profiles=7
Profile Names=10-year,25-year,50-year,1pct_min,100-year,1pct_plu,500-year
River Rch & RM= UNT 009 in RCW,Reach-1,2746
     173     236     286     174     346     691     514
River Rch & RM= UNT 009 in RCW,Reach-1,2488
     192     262     318     193     385     768     572
Boundary for River Rch & Prof#=UNT 009 in RCW,Reach-1,1
Up Type=0
Dn Type=3
Dn Slope=0.005
Boundary for River Rch & Prof#=UNT 009 in RCW,Reach-1,2
Up Type=0
Dn Type=3
Dn Slope=0.005
Boundary for River Rch & Prof#=UNT 009 in RCW,Reach-1,3
Up Type=0
Dn Type=3
Dn Slope=0.005
Boundary for River Rch & Prof#=UNT 009 in RCW,Reach-1,4
Up Type=0
Dn Type=3
Dn Slope=0.005
Boundary for River Rch & Prof#=UNT 009 in RCW,Reach-1,5
Up Type=0
Dn Type=3
Dn Slope=0.005
Boundary for River Rch & Prof#=UNT 009 in RCW,Reach-1,6
Up Type=0
Dn Type=3
Dn Slope=0.005
Boundary for River Rch & Prof#=UNT 009 in RCW,Reach-1,7
Up Type=0
Dn Type=3
Dn Slope=0.005

--- UNT 009 in RCW.g01 (geometry) ---

Geom Title=Existing Conditions
Program Version=5.05

River Reach=UNT 009 in RCW  ,Reach-1
Reach XY= 30
       2004550.8     13488084.54       2004460.8     13488084.54
       2004450.8     13488094.54       2004410.8     13488054.54
       2004350.8     13488054.54       2004340.8     13488044.54
       2004320.8     13488044.54       2004270.8     13487994.54
       2004230.8     13487994.54       2004220.8     13487984.54
       2004200.8     13487974.54      2004072.33     13487941.25
      2003791.51     13487838.82       2003657.4     13487804.54
       2003620.8     13487804.54      2003564.69     13487756.96
       2003420.8     13487684.54      2003374.76     13487684.54
      2003270.25     13487648.28      2003115.39     13487579.18
      2003059.48     13487570.85      2002933.09     13487564.54
       2002770.8     13487564.54      2002671.09     13487601.46
      2002592.09     13487598.86      2002538.27     13487583.23
      2002333.41     13487491.22      2002017.44     13487426.12
      2001836.88     13487426.98       2001660.8     13487434.54

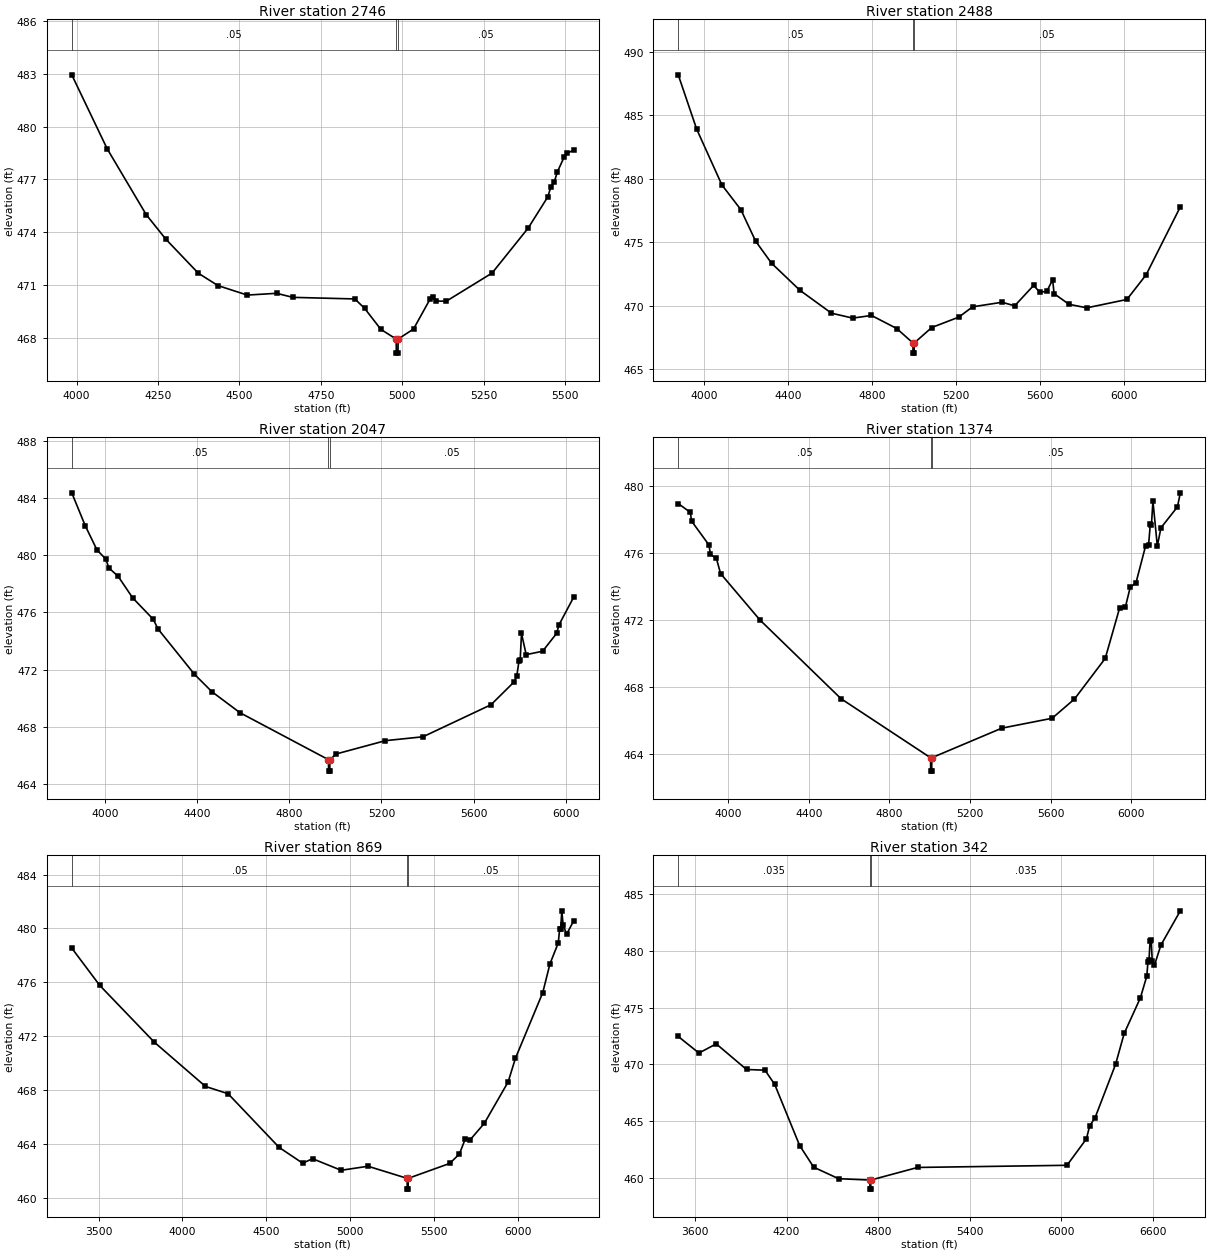
Type RM Length L Ch R = 1 ,2746    ,258,258,258
BEGIN DESCRIPTION:
UNT 009 in RCW 5.0
END DESCRIPTION:
XS GIS Cut Line= 3
       2004281.2     13486986.54        2004275.       13487975.
        2004325.     13488524.95
#Sta/Elev= 30
  3985.3  482.94  4093.8  478.74  4213.8  474.99  4273.8   473.6  4373.8  471.66
  4433.8  470.96  4523.8  470.42  4613.8  470.52  4663.8  470.29  4853.8   470.2
  4883.8  469.67  4933.8  468.47  4980.8  467.92  4981.3  467.12  4986.3  467.12
  4986.8  467.92    5034  468.49  5084.2  470.17  5094.3  470.32  5104.3  470.08
  5134.4  470.07    5275  471.67  5385.5  474.22  5445.7  475.99  5455.8  476.58
  5465.8  476.85  5475.8  477.44  5495.9  478.25    5506   478.5    5526  478.65
#Mann= 3 ,-1 , 0
  3985.3     .05       0  4980.8    .035       0  4986.8     .05       0
Bank Sta=4980.8,4986.8
XS Rating Curve= 0 ,0
Exp/Cntr=0.3,0.1

Type RM Length L Ch R = 1 ,2488    ,441,441,441
BEGIN DESCRIPTION:
Mapping XS d057953d
END DESCRIPTION:
XS GIS Cut Line= 3
      2004124.95     13486807.76      2003989.54      13488526.5
      2003505.17     13488984.82
#Sta/Elev= 30
  3876.4  488.19  3963.9  483.92  4084.3  479.51  4174.6  477.56  4244.8  475.08
  4320.7  473.34  4455.4  471.21  4605.9   469.4  4707.3  469.01  4796.5  469.22
  4916.9  468.19  4994.1  467.05  4994.6  466.25  4999.6  466.25  5000.1  467.05
  5083.8  468.27  5212.7  469.09    5278   469.9  5418.4  470.26  5478.6  469.98
  5568.9  471.59  5597.5  471.06    5631  471.11  5659.3  472.03  5666.2  470.94
    5737   470.1    5822  469.82  6012.9  470.48  6104.7  472.43  6267.3  477.78
#Mann= 3 ,-1 , 0
  3876.4     .05       0  4994.1    .035       0  5000.1     .05       0
Bank Sta=4994.1,5000.1
XS Rating Curve= 0 ,0
Exp/Cntr=0.3,0.1

Type RM Length L Ch R = 1 ,2047    ,673,673,673
BEGIN DESCRIPTION:
Mapping XS 13683f7a
END DESCRIPTION:
XS GIS Cut Line= 2
      2003828.08     13486677.54      2003427.03     13488818.19
#Sta/Elev= 30
  3856.7  484.36  3915.2  482.06    3966  480.37  4005.4  479.71  4016.9  479.12
  4057.6  478.53  4120.8  477.02  4210.2  475.52    4231  474.84  4388.8  471.68
  4464.6  470.46  4586.6  468.99  4970.3  465.71  4970.8  464.91  4975.8  464.91
  4976.3  465.71  5003.8  466.11  5217.4  467.04  5380.2  467.31  5675.3  469.55
    5777  471.17  5787.2  471.58  5796.8  472.61  5801.8  472.67  5807.5  474.53
  5827.9  473.05  5899.1  473.29  5959.6  474.53  5970.3  475.14  6034.6  477.09
#Mann= 3 ,-1 , 0
  3856.7     .05       0  4970.3    .035       0  4976.3     .05       0
Bank Sta=4970.3,4976.3
XS Rating Curve= 0 ,0
Exp/Cntr=0.3,0.1

Type RM Length L Ch R = 1 ,1374    ,505,505,505
BEGIN DESCRIPTION:
Mapping XS 2e17cd67
END DESCRIPTION:
XS GIS Cut Line= 4
      2003536.41     13486474.41      2003036.41     13487219.21
      2002958.29     13487943.16      2003296.82     13488740.01
#Sta/Elev= 30
  3752.3  478.97  3812.4  478.44  3818.4  477.92  3905.5  476.48  3911.5  475.93
  3941.5  475.69  3962.5  474.78  4157.5  472.01    4560   467.3  5004.2  463.77
  5004.7  462.97  5009.8  462.97  5010.3  463.77  5357.9  465.54  5607.2  466.13
  5718.1  467.28  5870.8  469.71  5941.8  472.71  5970.9  472.79  5994.5  473.95
  6023.6  474.24  6070.9  476.43  6085.7  476.47  6094.6  477.75    6100  477.69
  6107.5  479.11  6129.2  476.43  6147.3  477.52  6229.1  478.77  6243.3  479.61
#Mann= 3 ,-1 , 0
  3752.3     .05       0  5004.2    .035       0  5010.3     .05       0
Bank Sta=5004.2,5010.3
XS Rating Curve= 0 ,0
Exp/Cntr=0.3,0.1

Type RM Length L Ch R = 1 ,869     ,527,527,527
BEGIN DESCRIPTION:
Mapping XS 4f905353
END DESCRIPTION:
XS GIS Cut Line= 4
      2003401.01     13486255.65      2002489.54     13487281.71
        2002526.     13487911.91      2003149.38     13488680.75
#Sta/Elev= 30
  3340.2  478.54  3506.9  475.77  3833.1  471.54  4137.5  468.26  4272.1  467.72
  4576.5  463.73  4716.6  462.56    4776  462.89  4946.3  462.03  5106.6  462.33
  5339.9  461.43  5340.4  460.63  5345.5  460.63    5346  461.43  5593.7  462.54
  5651.2  463.24  5686.4  464.36  5715.1  464.29  5799.9  465.52  5942.1   468.6
  5985.3  470.35  6148.3  475.23  6191.5  477.38    6241  478.93    6249  479.96
  6255.3  479.98  6261.9  481.31  6269.8  480.27  6290.6  479.57  6333.7  480.59
#Mann= 3 ,-1 , 0
  3340.2     .05       0  5339.9    .035       0    5346     .05       0
Bank Sta=5339.9,5346
XS Rating Curve= 0 ,0
Exp/Cntr=0.3,0.1

Type RM Length L Ch R = 1 ,342     ,0,0,0
BEGIN DESCRIPTION:
UNT 009 in RCW 1.0
END DESCRIPTION:
XS GIS Cut Line= 4
      2002944.38      13486352.9      2001998.22     13487160.18
       2002006.9     13487667.99      2003074.99     13488774.99
#Sta/Elev= 30
  3490.2  472.46  3625.9     471  3739.1  471.81  3937.7  469.55  4058.5  469.49
  4122.2  468.24  4285.8  462.85    4378  460.94    4541  459.93  4745.7  459.81
  4746.2  459.01  4751.4  459.01  4751.9  459.81  5058.8  460.92  6037.6  461.11
  6164.9  463.44    6186  464.58  6221.5   465.3  6355.8     470  6412.4  472.73
  6518.4  475.86  6560.8  477.79    6568  479.05    6575  479.21  6582.2   480.9
  6589.1  480.96  6596.3  479.12  6610.5  478.73  6652.9  480.51  6780.1  483.53
#Mann= 3 ,-1 , 0
  3490.2    .035       0  4745.7     .03       0  4751.9    .035       0
Bank Sta=4745.7,4751.9
XS Rating Curve= 0 ,0
Exp/Cntr=0.3,0.1
LCMann Table=0

Chan Stop Cuts=-1
Use User Specified Reach Order=0
Composite Channel Slope=5