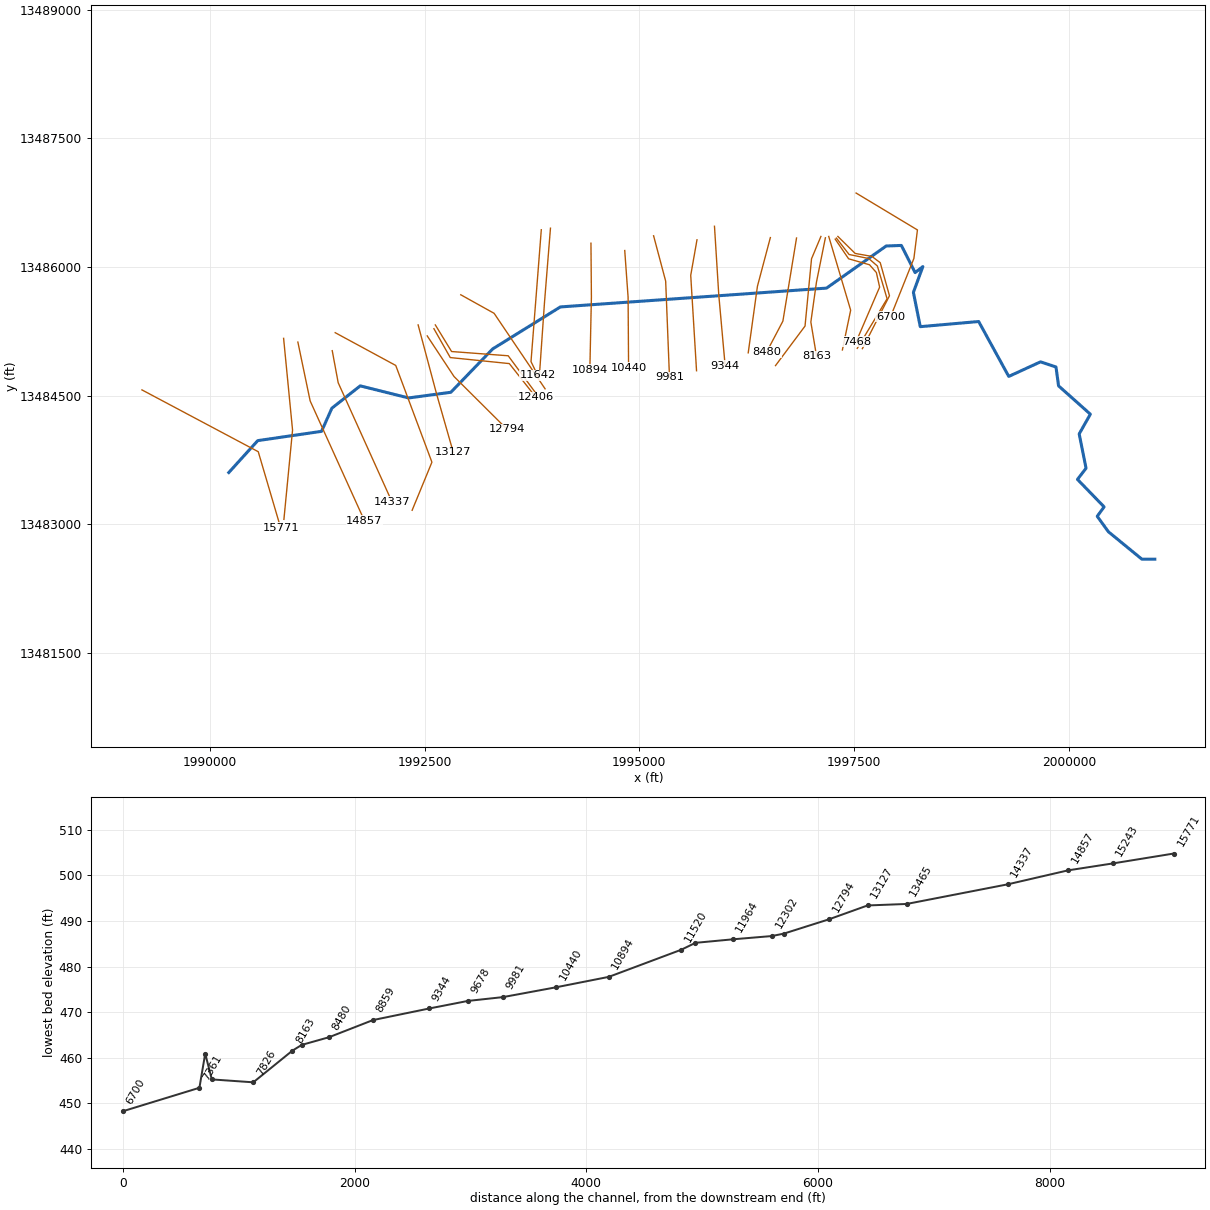
--- UNT 010 in RCW.prj (project) ---

Proj Title=UNT 010 in RCW Base Level Engineering
Current Plan=p01
Default Exp/Contr=0.3,0.1
English Units
Geom File=g01
Flow File=f01
Plan File=p01
BEGIN DESCRIPTION:
UNT 010 in RCW
END DESCRIPTION:

--- UNT 010 in RCW.p01 (plan) ---

Plan Title=Multiple Run
Short Identifier=Multiple
Geom File=g01
Flow File=f01
Subcritical Flow
K Sum by GR= 0
Std Step Tol= 0.01
Critical Tol= 0.01
Num of Std Step Trials= 20
Max Error Tol= 0.3
Flow Tol Ratio= 0.001
Split Flow NTrial= 30
Split Flow Tol= 0.02
Split Flow Ratio= 0.02
Log Output Level= 0
Friction Slope Method= 1
Unsteady Friction Slope Method= 2
Unsteady Bridges Friction Slope Method= 1
Parabolic Critical Depth
Global Vel Dist=  1 , 1 , 1
Global Log Level= 0
CheckData=True
Encroach Param= -1, 0, 0, 0
BEGIN DESCRIPTION:
Multiple Run
END DESCRIPTION:

--- UNT 010 in RCW.f01 (steady flow) ---

Flow Title=Multiple
Number of Profiles=7
Profile Names=10-year,25-year,50-year,1pct_min,100-year,1pct_plu,500-year
River Rch & RM= UNT 010 in RCW,Reach-1,15771
     158     215     261     159     316     631     472
River Rch & RM= UNT 010 in RCW,Reach-1,15243
     266     371     457     281     561    1118     856
River Rch & RM= UNT 010 in RCW,Reach-1,6700
     320     448     555     342     683    1362    1050
Boundary for River Rch & Prof#=UNT 010 in RCW,Reach-1,1
Up Type=0
Dn Type=3
Dn Slope=0.005
Boundary for River Rch & Prof#=UNT 010 in RCW,Reach-1,2
Up Type=0
Dn Type=3
Dn Slope=0.005
Boundary for River Rch & Prof#=UNT 010 in RCW,Reach-1,3
Up Type=0
Dn Type=3
Dn Slope=0.005
Boundary for River Rch & Prof#=UNT 010 in RCW,Reach-1,4
Up Type=0
Dn Type=3
Dn Slope=0.005
Boundary for River Rch & Prof#=UNT 010 in RCW,Reach-1,5
Up Type=0
Dn Type=3
Dn Slope=0.005
Boundary for River Rch & Prof#=UNT 010 in RCW,Reach-1,6
Up Type=0
Dn Type=3
Dn Slope=0.005
Boundary for River Rch & Prof#=UNT 010 in RCW,Reach-1,7
Up Type=0
Dn Type=3
Dn Slope=0.005

--- UNT 010 in RCW.g01 (geometry) ---

Geom Title=Existing Conditions

River Reach=UNT 010 in RCW,Reach-1
Reach XY= 30
      1990220.80     13483604.54      1990557.70     13483976.43
      1991300.80     13484084.54      1991420.80     13484354.54
      1991750.80     13484614.54      1992314.36     13484473.78
      1992806.28     13484540.02      1993292.66     13485044.96
      1994080.80     13485534.54      1997179.56     13485753.90
      1997874.09     13486244.70      1998050.80     13486251.21
      1998210.80     13485934.54      1998300.80     13486004.54
      1998190.80     13485704.54      1998270.80     13485304.54
      1998950.80     13485364.54      1999300.80     13484724.54
      1999670.80     13484894.54      1999850.80     13484834.54
      1999880.80     13484614.54      2000250.80     13484284.54
      2000120.80     13484054.54      2000200.80     13483654.54
      2000100.80     13483524.54      2000410.80     13483204.54
      2000330.80     13483094.54      2000460.80     13482914.54
      2000850.80     13482594.54      2001000.80     13482594.54

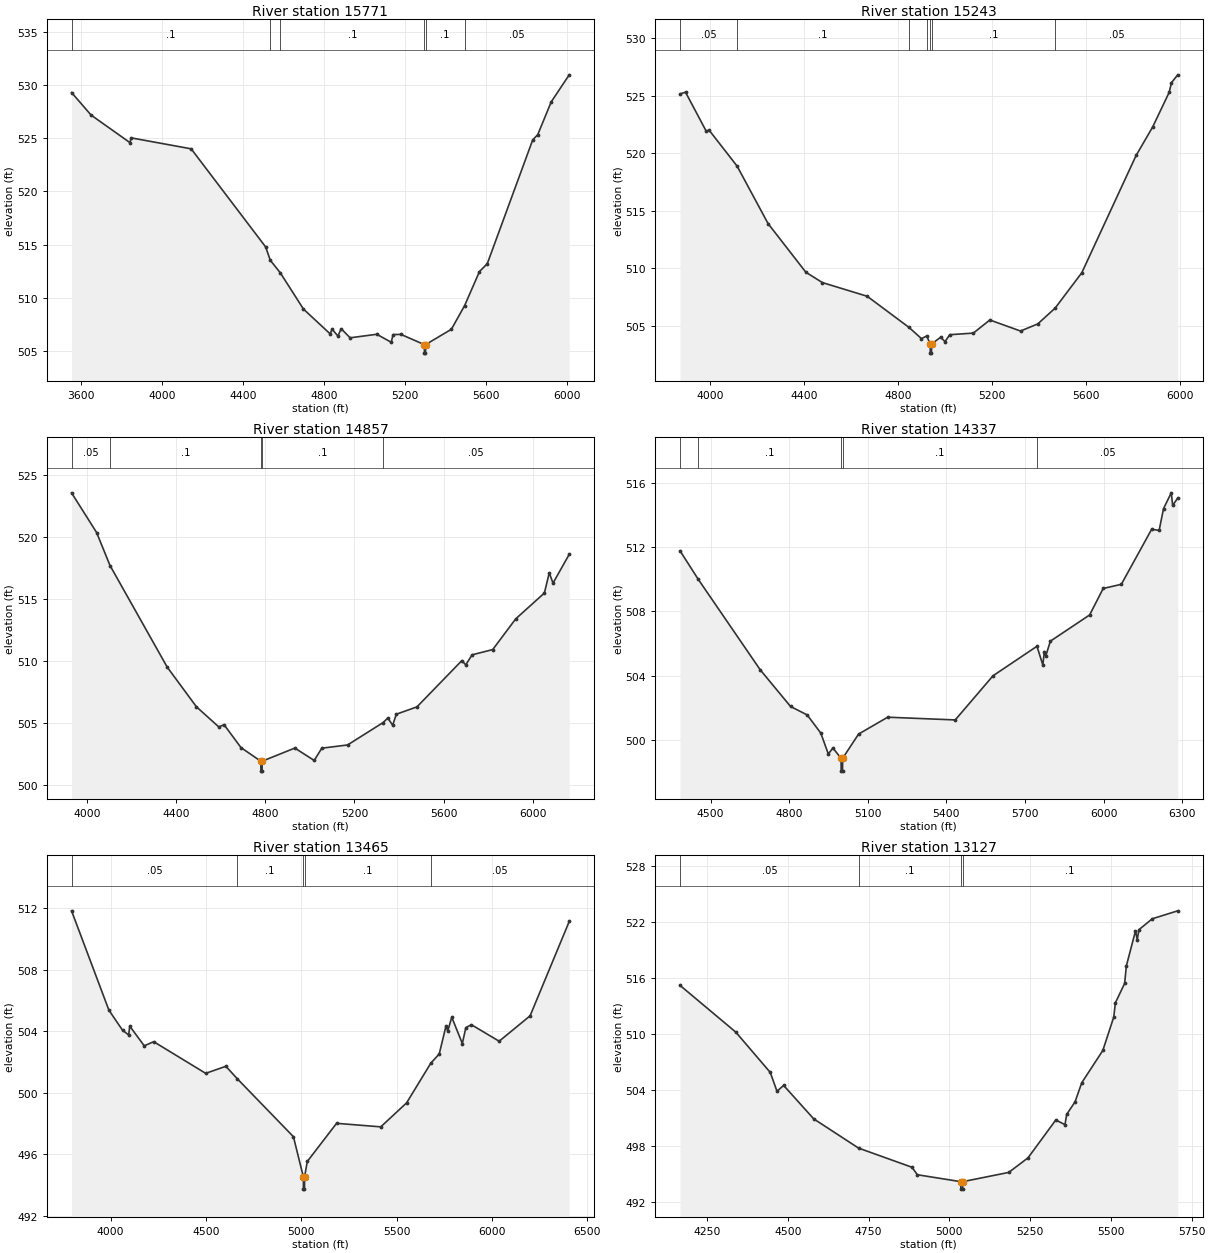
Type RM Length L Ch R = 1,15771,528,528,528
BEGIN DESCRIPTION:
UNT 010 in RCW 29.0
END DESCRIPTION:
XS GIS Cut Line= 3
      1989209.58     13484567.74      1990563.76     13483847.24
      1990824.16     13482961.86
#Sta/Elev= 30
  3552.4  529.29  3648.8  527.17  3840.9  524.58  3846.5  525.03  4142.8  524.00
  4510.7  514.78  4533.5  513.53  4582.7  512.36  4697.1  508.95  4828.9  506.62
  4838.5  507.06  4867.2  506.42  4883.5  507.10  4927.5  506.25  5059.3  506.58
  5130.4  505.83  5139.7  506.55  5178.3  506.57  5294.1  505.61  5294.6  504.81
  5299.6  504.81  5300.1  505.61  5427.4  507.05  5492.7  509.27  5566.0  512.47
  5604.6  513.21  5828.7  524.83  5853.7  525.33  5920.5  528.42  6009.2  530.95
#Mann=6,-1,0
  3552.4     0.1       0  4533.5    0.05       0  4582.7     0.1       0
  5294.1    0.07       0  5300.1     0.1       0  5492.7    0.05       0
Bank Sta=5294.1,5300.1
Exp/Cntr=0.3,0.1

Type RM Length L Ch R = 1,15243,386,386,386
BEGIN DESCRIPTION:
UNT 010 in RCW 28.0
END DESCRIPTION:
XS GIS Cut Line= 3
      1990858.90     13485168.42      1990963.06     13484098.98
      1990862.50     13483058.63
#Sta/Elev= 30
  3870.8  525.15  3894.3  525.30  3982.5  521.91  3994.8  522.00  4113.9  518.88
  4246.0  513.88  4406.7  509.66  4477.1  508.76  4668.0  507.57  4846.4  504.86
  4899.1  503.89  4921.4  504.12  4936.3  503.43  4936.8  502.63  4941.8  502.63
  4942.3  503.43  4980.8  504.01  4999.5  503.63  5019.6  504.23  5120.1  504.37
  5190.4  505.51  5321.0  504.55  5394.6  505.17  5468.4  506.54  5582.2  509.62
  5813.5  519.81  5883.6  522.27  5954.0  525.28  5964.0  526.13  5990.5  526.81
#Mann=7,-1,0
  3870.8    0.05       0  4113.9     0.1       0  4846.4    0.12       0
  4921.4     0.1       0  4936.3    0.07       0  4942.3     0.1       0
  5468.4    0.05       0
Bank Sta=4936.3,4942.3
Exp/Cntr=0.3,0.1

Type RM Length L Ch R = 1,14857,520,520,520
BEGIN DESCRIPTION:
UNT 010 in RCW 27.0
END DESCRIPTION:
XS GIS Cut Line= 3
      1991025.00     13485124.99      1991167.92     13484439.26
      1991799.87     13483043.41
#Sta/Elev= 30
  3931.1  523.55  4043.5  520.35  4103.6  517.69  4360.1  509.50  4491.3  506.30
  4591.3  504.68  4615.5  504.85  4691.1  503.01  4780.2  501.91  4780.7  501.11
  4785.8  501.11  4786.3  501.91  4932.8  502.97  5019.7  501.97  5053.8  502.96
  5169.3  503.22  5329.2  505.03  5349.8  505.39  5371.7  504.81  5388.2  505.70
  5480.6  506.29  5681.9  510.02  5699.5  509.68  5728.1  510.49  5820.5  510.91
  5923.8  513.39  6052.3  515.47  6074.2  517.10  6091.0  516.27  6163.8  518.59
#Mann=5,-1,0
  3931.1    0.05       0  4103.6     0.1       0  4780.2    0.07       0
  4786.3     0.1       0  5329.2    0.05       0
Bank Sta=4780.2,4786.3
Exp/Cntr=0.3,0.1

Type RM Length L Ch R = 1,14337,872,872,872
BEGIN DESCRIPTION:
UNT 010 in RCW 26.0
END DESCRIPTION:
XS GIS Cut Line= 3
      1991425.01     13485024.96      1991494.31     13484651.06
      1992119.30     13483265.68
#Sta/Elev= 30
  4383.1  511.78  4451.5  510.03  4689.0  504.37  4805.0  502.08  4868.7  501.55
  4920.6  500.42  4949.2  499.12  4966.9  499.49  4997.9  498.85  4998.4  498.05
  5003.5  498.05  5004.0  498.85  5064.9  500.36  5175.9  501.41  5433.8  501.24
  5578.0  503.99  5745.9  505.83  5768.3  504.66  5774.0  505.50  5779.5  505.23
  5797.2  506.15  5946.9  507.78  5998.7  509.43  6068.0  509.69  6183.7  513.12
  6212.3  513.05  6229.1  514.41  6258.6  515.39  6264.0  514.61  6283.2  515.06
#Mann=5,-1,0
  4383.1    0.05       0  4451.5     0.1       0  4997.9    0.07       0
  5004.0     0.1       0  5745.9    0.05       0
Bank Sta=4997.9,5004
Exp/Cntr=0.3,0.1

Type RM Length L Ch R = 1,13465,338,338,338
BEGIN DESCRIPTION:
UNT 010 in RCW 25.0
END DESCRIPTION:
XS GIS Cut Line= 4
      1991459.62     13485234.38      1992164.45     13484852.45
      1992585.51     13483725.20      1992355.44     13483164.99
#Sta/Elev= 30
  3795.3  511.84  3991.2  505.38  4063.0  504.07  4094.9  503.77  4100.6  504.34
  4176.7  503.06  4226.1  503.33  4499.0  501.27  4604.9  501.73  4663.7  500.93
  4959.1  497.15  5011.2  494.54  5011.7  493.74  5017.1  493.74  5017.6  494.54
  5031.9  495.54  5185.5  498.02  5417.3  497.79  5552.8  499.35  5679.7  501.93
  5723.9  502.53  5759.5  504.35  5768.5  504.02  5789.8  504.92  5845.1  503.21
  5863.7  504.25  5893.1  504.43  6038.3  503.36  6200.5  505.01  6405.9  511.15
#Mann=5,-1,0
  3795.3    0.05       0  4663.7     0.1       0  5011.2    0.07       0
  5017.6     0.1       0  5679.7    0.05       0
Bank Sta=5011.2,5017.6
Exp/Cntr=0.3,0.1

Type RM Length L Ch R = 1,13127,333,333,333
BEGIN DESCRIPTION:
UNT 010 in RCW 24.0
END DESCRIPTION:
XS GIS Cut Line= 3
      1992425.00     13485325.00      1992640.15     13484519.12
      1992834.37     13483839.33
#Sta/Elev= 30
  4165.8  515.22  4338.4  510.22  4445.3  505.90  4466.0  503.89  4486.7  504.51
  4579.8  500.93  4718.8  497.80  4884.1  495.75  4900.7  494.95  5035.0  494.21
  5035.5  493.41  5040.9  493.41  5041.4  494.21  5183.8  495.20  5243.4  496.76
  5329.4  500.81  5357.8  500.31  5363.2  501.42  5389.0  502.75  5409.8  504.80
  5475.0  508.25  5508.8  511.82  5514.0  513.36  5542.6  515.43  5547.8  517.29
  5576.2  521.05  5581.6  520.11  5586.8  521.18  5628.2  522.35  5706.9  523.20
#Mann=4,-1,0
  4165.8    0.05       0  4718.8     0.1       0  5035.0    0.07       0
  5041.4     0.1       0
Bank Sta=5035,5041.4
Exp/Cntr=0.3,0.1

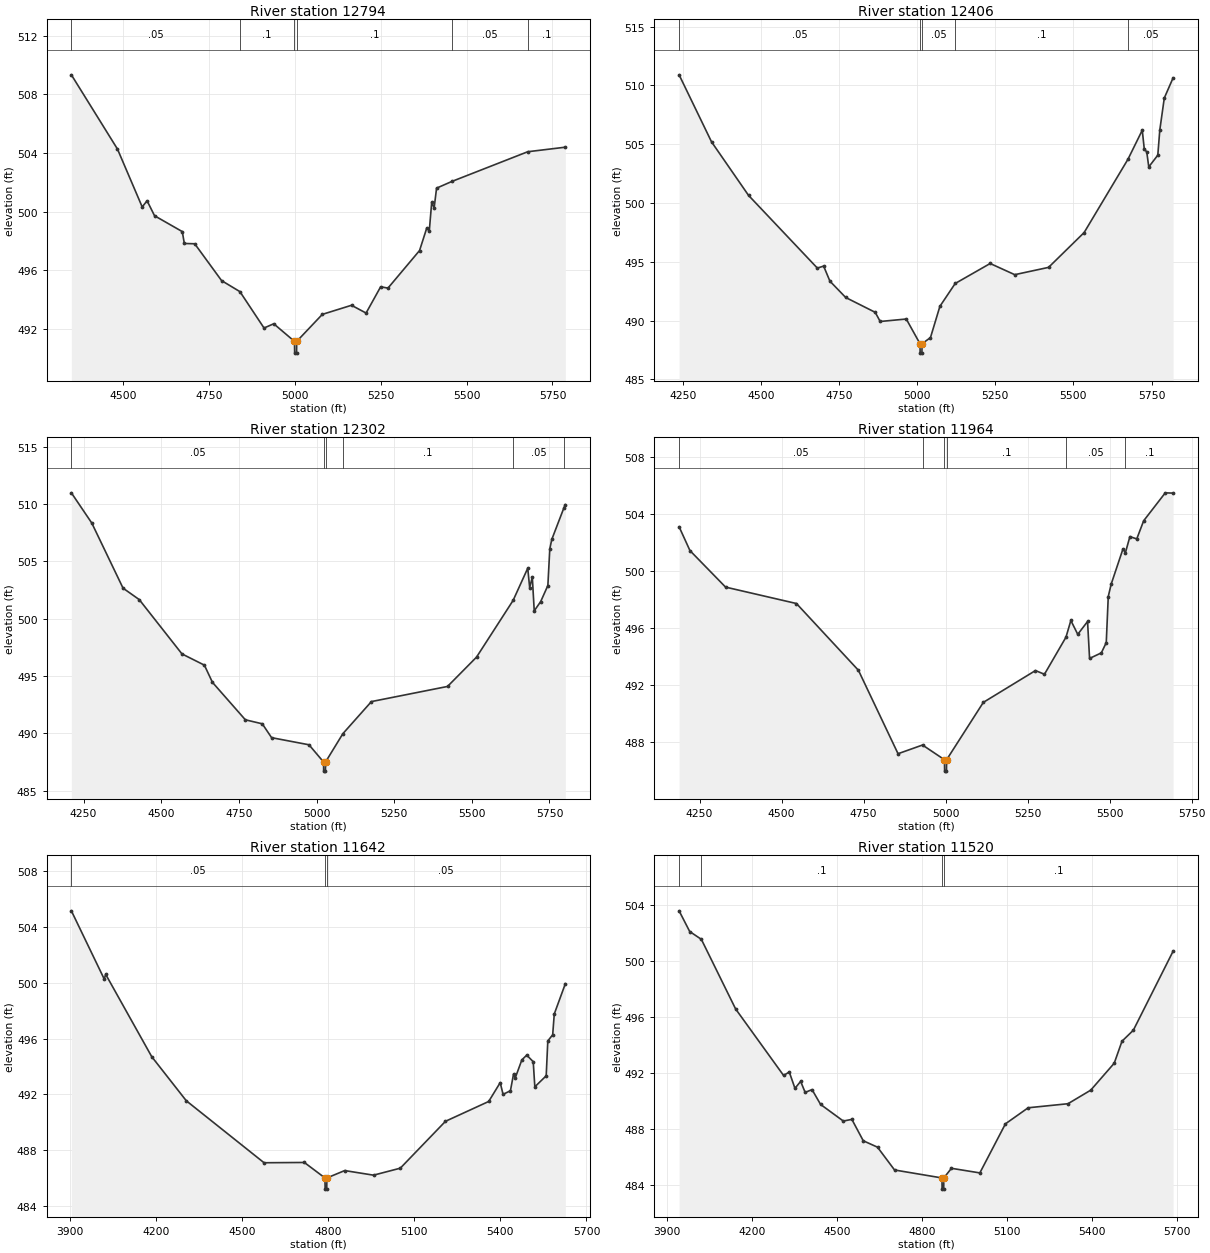
Type RM Length L Ch R = 1,12794,388,388,388
BEGIN DESCRIPTION:
UNT 010 in RCW 23.0
END DESCRIPTION:
XS GIS Cut Line= 3
      1992530.77     13485197.07      1992843.27     13484723.11
      1993459.47     13484109.52
#Sta/Elev= 30
  4350.2  509.33  4484.4  504.27  4556.3  500.33  4570.5  500.75  4592.2  499.73
  4672.9  498.65  4678.9  497.84  4709.1  497.82  4787.3  495.31  4840.6  494.56
  4910.8  492.08  4939.0  492.37  4999.4  491.17  4999.9  490.37  5005.4  490.37
  5005.9  491.17  5080.4  493.01  5165.3  493.63  5207.7  493.10  5250.1  494.89
  5271.4  494.80  5363.3  497.36  5384.5  498.91  5391.6  498.69  5398.6  500.64
  5405.7  500.26  5412.8  501.61  5457.7  502.07  5678.0  504.09  5787.5  504.40
#Mann=6,-1,0
  4350.2    0.05       0  4840.6     0.1       0  4999.4    0.07       0
  5005.9     0.1       0  5457.7    0.05       0  5678.0     0.1       0
Bank Sta=4999.4,5005.9
Exp/Cntr=0.3,0.1

Type RM Length L Ch R = 1,12406,104,104,104
BEGIN DESCRIPTION:
Mapping XS 14e9a56d
END DESCRIPTION:
XS GIS Cut Line= 4
      1992608.88     13485280.43      1992799.00     13484944.47
      1993486.50     13484874.15      1993798.36     13484479.13
#Sta/Elev= 30
  4238.5  510.90  4342.3  505.20  4460.7  500.65  4680.8  494.47  4700.9  494.64
  4721.0  493.36  4771.5  491.97  4865.9  490.71  4881.9  489.93  4965.3  490.14
  5009.2  488.04  5009.7  487.24  5015.3  487.24  5015.8  488.04  5042.7  488.56
  5072.9  491.22  5121.8  493.16  5233.7  494.86  5312.3  493.91  5420.5  494.53
  5534.3  497.49  5674.7  503.73  5720.3  506.19  5726.7  504.60  5734.7  504.34
  5741.1  503.07  5770.0  504.07  5776.4  506.21  5790.8  508.93  5818.9  510.64
#Mann=5,-1,0
  4238.5    0.05       0  5009.2    0.03       0  5015.8    0.05       0
  5121.8     0.1       0  5674.7    0.05       0
Bank Sta=5009.2,5015.8
Exp/Cntr=0.3,0.1

Type RM Length L Ch R = 1,12302,338,338,338
BEGIN DESCRIPTION:
UNT 010 in RCW 22.0
END DESCRIPTION:
XS GIS Cut Line= 4
      1992625.01     13485324.99      1992814.62     13485014.78
      1993473.48     13484965.30      1993809.89     13484509.85
#Sta/Elev= 30
  4210.7  510.99  4276.5  508.35  4377.1  502.67  4429.3  501.67  4566.8  496.93
  4639.0  495.95  4664.9  494.45  4770.9  491.18  4825.4  490.83  4855.4  489.62
  4975.8  489.00  5022.6  487.50  5023.1  486.70  5028.7  486.70  5029.2  487.50
  5084.9  489.97  5176.8  492.77  5421.8  494.09  5515.2  496.65  5633.0  501.60
  5680.1  504.41  5686.3  502.72  5694.8  503.63  5701.0  500.69  5721.8  501.50
  5744.9  502.90  5751.1  506.10  5757.5  506.92  5796.4  509.67  5801.2  509.96
#Mann=6,-1,0
  4210.7    0.05       0  5022.6    0.03       0  5029.2    0.05       0
  5084.9     0.1       0  5633.0    0.05       0  5796.4     0.1       0
Bank Sta=5022.6,5029.2
Exp/Cntr=0.3,0.1

Type RM Length L Ch R = 1,11964,322,322,322
BEGIN DESCRIPTION:
UNT 010 in RCW 21.0
END DESCRIPTION:
XS GIS Cut Line= 3
      1992921.40     13485676.24      1993309.42     13485460.09
      1993903.11     13484579.97
#Sta/Elev= 30
  4187.6  503.11  4220.7  501.44  4329.3  498.88  4545.3  497.73  4734.2  493.05
  4855.0  487.20  4929.6  487.81  4996.5  486.78  4997.0  485.98  5002.6  485.98
  5003.1  486.78  5115.0  490.80  5273.9  493.03  5301.3  492.77  5366.9  495.37
  5381.8  496.54  5402.8  495.57  5432.7  496.47  5438.8  493.88  5474.7  494.27
  5489.7  494.99  5495.8  498.22  5504.7  499.09  5540.7  501.56  5548.2  501.30
  5561.7  502.42  5582.7  502.26  5603.7  503.53  5669.6  505.49  5693.4  505.47
#Mann=6,-1,0
  4187.6    0.05       0  4929.6     0.1       0  4996.5    0.07       0
  5003.1     0.1       0  5366.9    0.05       0  5548.2     0.1       0
Bank Sta=4996.5,5003.1
Exp/Cntr=0.3,0.1

Type RM Length L Ch R = 1,11642,122,122,122
BEGIN DESCRIPTION:
Mapping XS 9a1a33ed
END DESCRIPTION:
XS GIS Cut Line= 3
      1993858.90     13486434.09      1993739.10     13484897.59
      1993817.22     13484736.16
#Sta/Elev= 30
  3906.0  505.15  4020.5  500.26  4025.5  500.60  4185.9  494.70  4306.3  491.54
  4577.1  487.10  4717.5  487.12  4789.3  486.01  4789.8  485.21  4795.4  485.21
  4795.9  486.01  4858.0  486.54  4958.3  486.21  5051.6  486.71  5209.0  490.07
  5359.5  491.49  5399.6  492.84  5409.6  492.00  5435.2  492.26  5446.0  493.45
  5452.4  493.20  5475.0  494.47  5492.0  494.81  5514.6  494.34  5520.2  492.54
  5559.8  493.33  5565.4  495.83  5582.4  496.27  5587.9  497.76  5626.5  499.93
#Mann=3,-1,0
  3906.0    0.05       0  4789.3    0.04       0  4795.9    0.05       0
Bank Sta=4789.3,4795.9
Exp/Cntr=0.3,0.1

Type RM Length L Ch R = 1,11520,626,626,626
BEGIN DESCRIPTION:
UNT 010 in RCW 20.0
END DESCRIPTION:
XS GIS Cut Line= 3
      1993965.67     13486452.27      1993895.35     13485577.28
      1993835.46     13484715.27
#Sta/Elev= 30
  3943.9  503.61  3981.3  502.13  4022.4  501.57  4143.2  496.59  4312.4  491.83
  4332.4  492.08  4352.5  490.91  4372.5  491.41  4388.4  490.62  4412.7  490.82
  4442.8  489.76  4523.0  488.57  4553.1  488.69  4593.3  487.16  4643.6  486.70
  4703.6  485.07  4870.8  484.50  4871.3  483.70  4876.9  483.70  4877.4  484.50
  4904.2  485.19  5004.4  484.86  5094.6  488.37  5174.8  489.52  5315.2  489.81
  5395.4  490.78  5478.3  492.71  5505.6  494.28  5545.7  495.07  5685.8  500.72
#Mann=4,-1,0
  3943.9    0.05       0  4022.4     0.1       0  4870.8    0.07       0
  4877.4     0.1       0
Bank Sta=4870.8,4877.4
Exp/Cntr=0.3,0.1

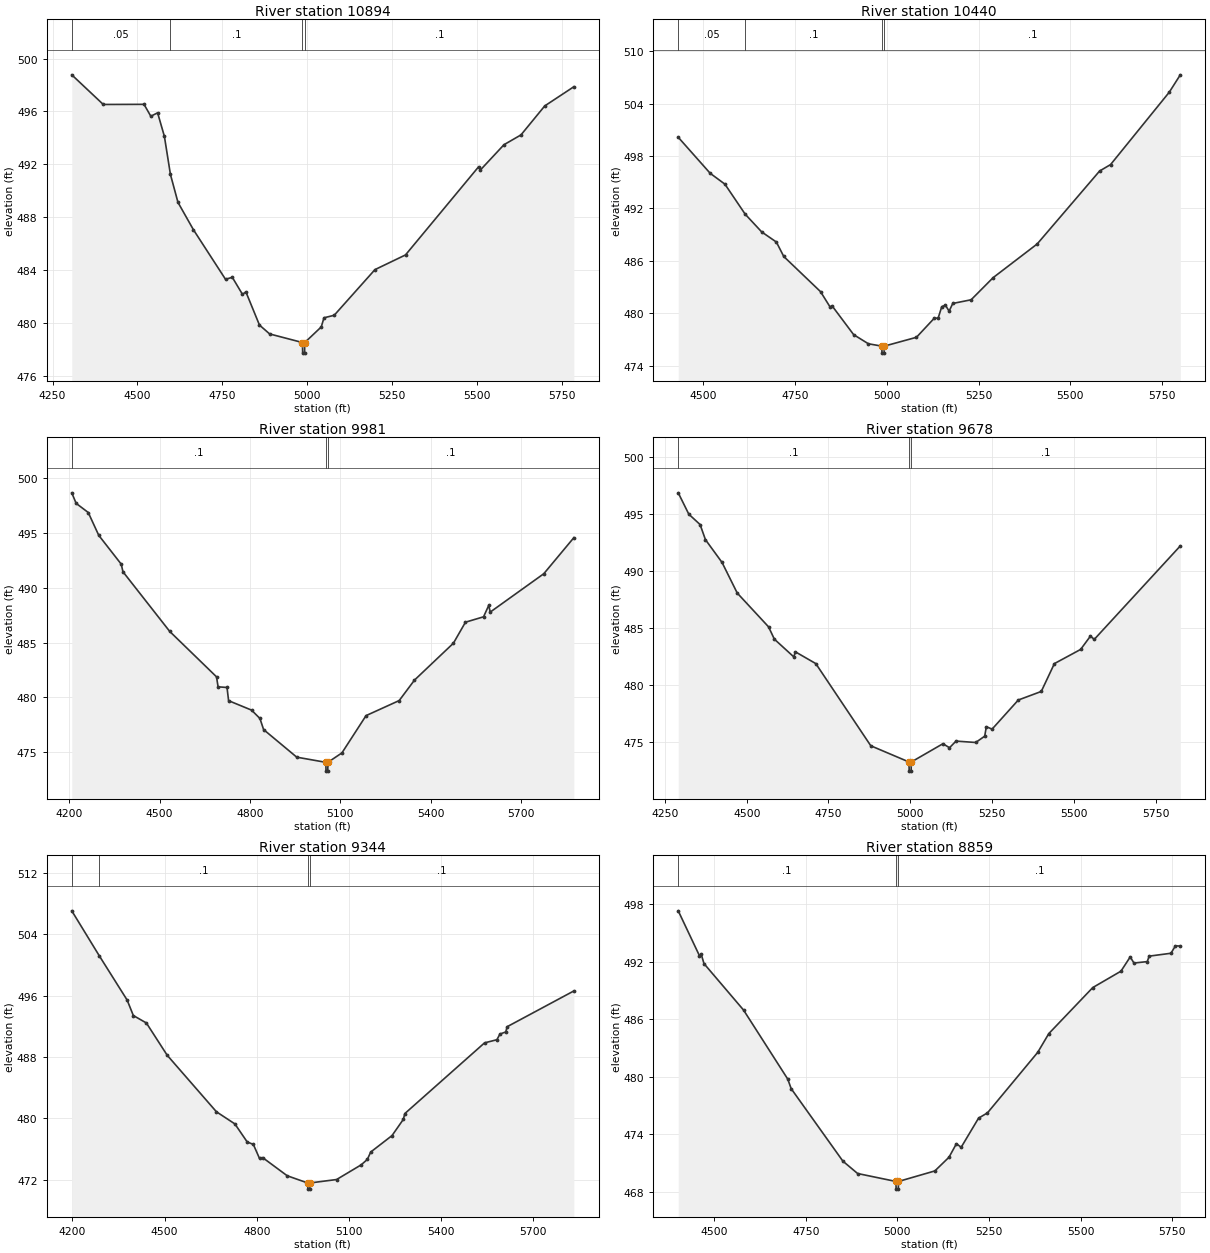
Type RM Length L Ch R = 1,10894,454,454,454
BEGIN DESCRIPTION:
UNT 010 in RCW 19.0
END DESCRIPTION:
XS GIS Cut Line= 3
      1994437.02     13486277.80      1994442.23     13485650.19
      1994424.01     13484799.32
#Sta/Elev= 30
  4306.7  498.77  4399.5  496.53  4519.5  496.54  4539.5  495.64  4559.5  495.90
  4579.5  494.12  4597.3  491.24  4619.5  489.13  4665.1  487.06  4759.5  483.32
  4779.5  483.47  4809.5  482.18  4819.5  482.37  4859.5  479.86  4889.5  479.19
  4986.2  478.54  4986.7  477.74  4992.4  477.74  4992.9  478.54  5041.5  479.72
  5049.5  480.41  5079.6  480.60  5199.6  484.05  5289.6  485.16  5505.2  491.83
  5510.2  491.58  5579.7  493.49  5629.7  494.23  5699.7  496.42  5785.4  497.87
#Mann=4,-1,0
  4306.7    0.05       0  4597.3     0.1       0  4986.2    0.07       0
  4992.9     0.1       0
Bank Sta=4986.2,4992.9
Exp/Cntr=0.3,0.1

Type RM Length L Ch R = 1,10440,459,459,459
BEGIN DESCRIPTION:
UNT 010 in RCW 18.0
END DESCRIPTION:
XS GIS Cut Line= 3
      1994830.25     13486191.84      1994869.31     13485647.59
      1994875.00     13484824.96
#Sta/Elev= 30
  4431.3  500.14  4518.4  496.02  4558.5  494.78  4613.7  491.35  4658.7  489.32
  4698.8  488.16  4718.9  486.51  4819.1  482.49  4845.5  480.71  4850.5  480.87
  4909.4  477.57  4949.5  476.53  4986.1  476.26  4986.6  475.46  4992.4  475.46
  4992.9  476.26  5080.5  477.27  5129.5  479.47  5139.5  479.45  5149.5  480.77
  5159.5  480.94  5169.5  480.26  5179.5  481.14  5229.5  481.56  5289.5  484.09
  5409.5  487.94  5579.6  496.28  5609.6  497.02  5769.6  505.30  5799.6  507.28
#Mann=4,-1,0
  4431.3    0.05       0  4613.7     0.1       0  4986.1    0.07       0
  4992.9     0.1       0
Bank Sta=4986.1,4992.9
Exp/Cntr=0.3,0.1

Type RM Length L Ch R = 1,9981,303,303,303
BEGIN DESCRIPTION:
UNT 010 in RCW 17.0
END DESCRIPTION:
XS GIS Cut Line= 3
      1995166.18     13486363.77      1995306.81     13485835.09
      1995351.08     13484715.33
#Sta/Elev= 30
  4208.0  498.62  4222.6  497.66  4262.7  496.83  4297.7  494.75  4372.3  492.13
  4378.0  491.44  4533.4  486.01  4688.8  481.88  4694.0  480.97  4723.7  480.91
  4728.9  479.71  4805.2  478.85  4833.0  478.09  4845.2  477.08  4955.3  474.57
  5052.0  474.10  5052.5  473.30  5058.3  473.30  5058.8  474.10  5105.4  474.96
  5185.5  478.35  5295.6  479.72  5346.3  481.58  5475.7  484.94  5515.7  486.85
  5575.8  487.34  5593.0  488.38  5598.0  487.77  5775.9  491.26  5875.7  494.54
#Mann=3,-1,0
  4208.0     0.1       0  5052.0    0.07       0  5058.8     0.1       0
Bank Sta=5052,5058.8
Exp/Cntr=0.3,0.1

Type RM Length L Ch R = 1,9678,334,334,334
BEGIN DESCRIPTION:
Mapping XS aed03ed8
END DESCRIPTION:
XS GIS Cut Line= 3
      1995671.39     13486316.83      1995598.48     13485902.80
      1995666.18     13484790.86
#Sta/Elev= 30
  4290.8  496.84  4323.1  494.97  4357.6  494.06  4373.9  492.74  4424.7  490.74
  4471.1  488.06  4566.8  485.10  4584.6  484.02  4643.9  482.47  4648.9  482.91
  4711.2  481.88  4879.3  474.68  4996.1  473.26  4996.6  472.46  5002.5  472.46
  5003.0  473.26  5099.7  474.86  5119.8  474.51  5139.8  475.09  5199.9  474.97
  5227.4  475.52  5232.4  476.35  5250.0  476.14  5330.1  478.69  5400.3  479.44
  5440.4  481.88  5520.5  483.12  5550.6  484.29  5562.2  484.00  5825.2  492.19
#Mann=3,-1,0
  4290.8     0.1       0  4996.1    0.07       0  5003.0     0.1       0
Bank Sta=4996.1,5003
Exp/Cntr=0.3,0.1

Type RM Length L Ch R = 1,9344,485,485,485
BEGIN DESCRIPTION:
UNT 010 in RCW 16.0
END DESCRIPTION:
XS GIS Cut Line= 3
      1995875.00     13486474.97      1995925.00     13485675.00
      1995999.52     13484845.48
#Sta/Elev= 30
  4198.0  507.03  4287.8  501.16  4378.3  495.41  4398.4  493.40  4440.9  492.43
  4508.6  488.23  4668.9  480.87  4729.0  479.29  4769.1  476.94  4789.1  476.62
  4809.2  474.79  4819.2  474.91  4899.3  472.54  4966.0  471.60  4966.5  470.80
  4972.4  470.80  4972.9  471.60  5060.1  472.05  5140.1  473.96  5160.2  474.67
  5171.2  475.63  5240.5  477.77  5277.3  479.88  5282.3  480.64  5541.7  489.84
  5581.9  490.25  5591.9  490.99  5610.6  491.26  5615.6  491.95  5832.4  496.60
#Mann=4,-1,0
  4198.0    0.05       0  4287.8     0.1       0  4966.0    0.07       0
  4972.9     0.1       0
Bank Sta=4966,4972.9
Exp/Cntr=0.3,0.1

Type RM Length L Ch R = 1,8859,379,379,379
BEGIN DESCRIPTION:
UNT 010 in RCW 15.0
END DESCRIPTION:
XS GIS Cut Line= 3
      1996525.57     13486342.92      1996375.00     13485775.00
      1996267.81     13484999.61
#Sta/Elev= 30
  4401.9  497.31  4459.6  492.64  4464.8  492.76  4472.2  491.80  4580.2  486.95
  4700.9  479.74  4710.1  478.75  4851.3  471.18  4891.5  469.89  4996.1  469.06
  4996.6  468.26  5002.5  468.26  5003.0  469.06  5102.3  470.16  5140.9  471.59
  5161.1  473.00  5174.1  472.63  5221.6  475.67  5245.9  476.22  5383.1  482.54
  5413.4  484.50  5533.3  489.30  5610.2  491.01  5635.5  492.50  5645.6  491.86
  5682.1  492.01  5687.1  492.58  5746.6  492.88  5759.0  493.66  5772.2  493.63
#Mann=3,-1,0
  4401.9     0.1       0  4996.1    0.07       0  5003.0     0.1       0
Bank Sta=4996.1,5003
Exp/Cntr=0.3,0.1

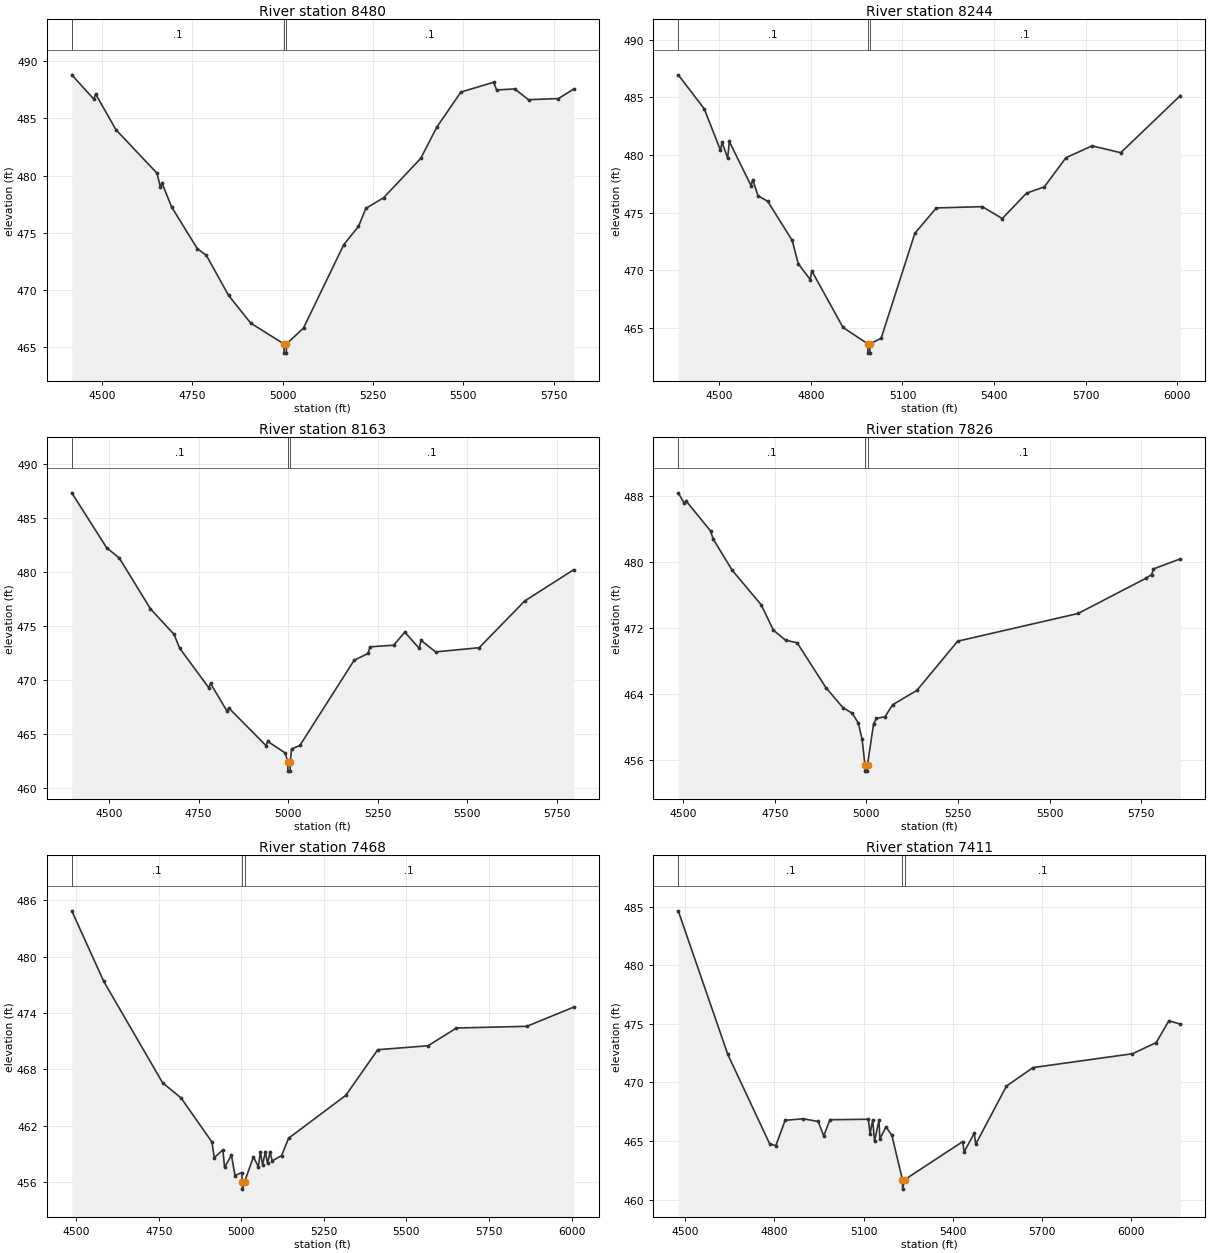
Type RM Length L Ch R = 1,8480,236,236,236
BEGIN DESCRIPTION:
UNT 010 in RCW 14.0
END DESCRIPTION:
XS GIS Cut Line= 3
      1996830.24     13486337.65      1996671.40     13485368.94
      1996482.09     13485008.48
#Sta/Elev= 30
  4417.0  488.79  4477.9  486.67  4482.9  487.12  4539.2  484.00  4652.8  480.20
  4661.8  479.02  4666.8  479.33  4693.3  477.25  4764.2  473.62  4789.4  473.03
  4850.7  469.54  4912.0  467.12  5003.9  465.30  5004.4  464.50  5010.4  464.50
  5010.9  465.30  5058.1  466.70  5169.6  473.98  5210.1  475.56  5230.4  477.13
  5279.8  478.07  5382.4  481.50  5427.2  484.25  5493.5  487.29  5583.8  488.14
  5592.3  487.47  5642.1  487.56  5680.5  486.62  5763.1  486.72  5805.8  487.56
#Mann=3,-1,0
  4417.0     0.1       0  5003.9    0.07       0  5010.9     0.1       0
Bank Sta=5003.9,5010.9
Exp/Cntr=0.3,0.1

Type RM Length L Ch R = 1,8244,81,81,81
BEGIN DESCRIPTION:
Mapping XS 10a9c042
END DESCRIPTION:
XS GIS Cut Line= 4
      1997114.12     13486355.96      1997004.73     13486095.51
      1996929.21     13485311.65      1996585.45     13484850.70
#Sta/Elev= 30
  4365.3  486.94  4450.6  483.99  4503.5  480.41  4508.9  481.09  4527.2  479.73
  4532.7  481.16  4603.9  477.33  4609.4  477.86  4626.7  476.45  4658.3  475.98
  4738.7  472.58  4758.8  470.55  4797.7  469.19  4802.7  469.95  4905.1  465.04
  4986.4  463.61  4986.9  462.81  4992.9  462.81  4993.4  463.61  5030.1  464.10
  5140.6  473.20  5210.9  475.40  5361.6  475.51  5427.0  474.48  5506.5  476.68
  5564.9  477.23  5635.8  479.76  5721.3  480.78  5815.1  480.19  6010.3  485.14
#Mann=3,-1,0
  4365.3     0.1       0  4986.4    0.07       0  4993.4     0.1       0
Bank Sta=4986.4,4993.4
Exp/Cntr=0.3,0.1

Type RM Length L Ch R = 1,8163,337,337,337
BEGIN DESCRIPTION:
UNT 010 in RCW 13.0
END DESCRIPTION:
XS GIS Cut Line= 4
      1997166.19     13486340.33      1997062.02     13485822.07
      1996996.92     13485358.53      1997063.44     13484959.45
#Sta/Elev= 30
  4395.8  487.31  4493.0  482.23  4528.7  481.26  4615.4  476.57  4681.3  474.20
  4697.0  472.92  4778.0  469.27  4783.1  469.66  4828.9  467.11  4834.0  467.39
  4937.8  463.91  4942.8  464.29  4992.1  463.21  4998.7  462.34  4999.2  461.54
  5005.2  461.54  5005.7  462.34  5009.1  463.59  5032.5  463.92  5184.0  471.81
  5223.0  472.44  5228.0  473.05  5294.2  473.20  5325.4  474.41  5365.5  472.91
  5370.6  473.65  5411.3  472.58  5532.9  472.97  5659.7  477.29  5797.1  480.20
#Mann=3,-1,0
  4395.8     0.1       0  4998.7    0.07       0  5005.7     0.1       0
Bank Sta=4998.7,5005.7
Exp/Cntr=0.3,0.1

Type RM Length L Ch R = 1,7826,358,358,358
BEGIN DESCRIPTION:
UNT 010 in RCW 12.0
END DESCRIPTION:
XS GIS Cut Line= 3
      1997205.25     13486355.93      1997460.46     13485496.55
      1997364.11     13485033.03
#Sta/Elev= 30
  4486.7  488.44  4503.4  487.15  4508.6  487.43  4575.0  483.80  4581.6  482.86
  4633.7  479.04  4713.1  474.82  4746.3  471.74  4779.5  470.52  4811.1  470.21
  4889.5  464.76  4936.2  462.31  4961.2  461.65  4978.0  460.46  4988.4  458.46
  4996.1  455.40  4996.6  454.60  5002.7  454.60  5003.2  455.40  5019.7  460.36
  5027.6  461.00  5051.0  461.22  5071.8  462.68  5137.7  464.41  5249.2  470.40
  5577.8  473.77  5762.7  478.05  5778.3  478.50  5783.4  479.19  5856.6  480.41
#Mann=3,-1,0
  4486.7     0.1       0  4996.1    0.07       0  5003.2     0.1       0
Bank Sta=4996.1,5003.2
Exp/Cntr=0.3,0.1

Type RM Length L Ch R = 1,7468,57,57,57
BEGIN DESCRIPTION:
Mapping XS 99084b7a
END DESCRIPTION:
XS GIS Cut Line= 6
      1997280.32     13486324.69      1997436.59     13486095.51
      1997679.64     13486026.06      1997759.50     13485935.79
      1997797.70     13485765.65      1997524.09     13485128.38
#Sta/Elev= 30
  4486.7  484.88  4583.6  477.36  4761.7  466.57  4817.7  464.95  4911.2  460.25
  4918.2  458.58  4944.1  459.43  4949.4  457.56  4970.1  458.86  4981.0  456.69
  5001.3  457.00  5003.0  456.04  5003.5  455.24  5010.1  456.04  5036.7  458.67
  5051.7  457.63  5057.7  459.21  5064.4  457.83  5072.7  459.18  5079.6  457.99
  5086.9  459.15  5093.8  458.25  5122.1  458.82  5143.1  460.66  5316.5  465.23
  5413.2  470.09  5565.4  470.51  5651.4  472.40  5864.4  472.58  6006.9  474.63
#Mann=3,-1,0
  4486.7     0.1       0  5003.0    0.07       0  5010.1     0.1       0
Bank Sta=5003,5010.1
Exp/Cntr=0.3,0.1

Type RM Length L Ch R = 1,7411,50,50,50
BEGIN DESCRIPTION:
Mapping XS c69ba510
END DESCRIPTION:
XS GIS Cut Line= 6
      1997294.24     13486336.80      1997441.79     13486145.85
      1997671.83     13486098.11      1997771.66     13486011.31
      1997884.50     13485629.36      1997537.29     13485052.11
#Sta/Elev= 30
  4477.0  484.64  4643.6  472.39  4784.1  464.77  4805.0  464.61  4836.2  466.77
  4897.2  466.90  4947.4  466.67  4965.9  465.44  4986.8  466.82  5115.7  466.86
  5121.7  465.63  5130.5  466.82  5136.6  464.97  5151.5  466.78  5154.6  465.19
  5175.1  466.22  5195.1  465.48  5230.4  461.70  5230.9  460.90  5237.5  461.70
  5432.6  464.95  5437.8  464.08  5471.6  465.66  5476.8  464.74  5580.0  469.69
  5669.4  471.27  6003.5  472.45  6083.2  473.40  6125.9  475.27  6164.2  474.97
#Mann=3,-1,0
  4477.0     0.1       0  5230.4    0.07       0  5237.5     0.1       0
Bank Sta=5230.4,5237.5
Exp/Cntr=0.3,0.1

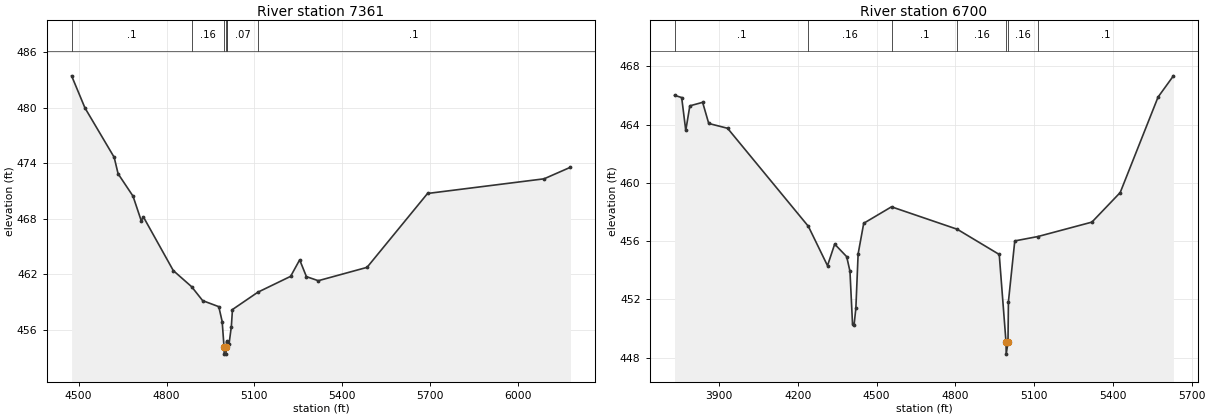
Type RM Length L Ch R = 1,7361,661,661,661
BEGIN DESCRIPTION:
Mapping XS de5cdb7a
END DESCRIPTION:
XS GIS Cut Line= 6
      1997311.61     13486355.89      1997512.98     13486158.01
      1997707.42     13486123.29      1997804.64     13486050.37
      1997912.28     13485664.95      1997597.20     13485048.46
#Sta/Elev= 30
  4476.0  483.42  4521.5  479.96  4621.3  474.63  4634.6  472.86  4685.6  470.44
  4713.5  467.80  4721.2  468.19  4823.1  462.41  4885.7  460.67  4923.3  459.17
  4978.3  458.52  4989.9  456.91  4996.2  454.20  4996.7  453.40  5002.8  453.40
  5003.3  454.20  5005.0  454.67  5006.0  454.82  5013.1  454.44  5021.2  456.38
  5025.0  458.21  5111.7  460.08  5223.5  461.79  5254.4  463.57  5277.4  461.76
  5317.9  461.32  5484.3  462.76  5690.8  470.73  6088.5  472.31  6178.7  473.56
#Mann=7,-1,0
  4476.0     0.1       0  4885.7    0.16       0  4996.2    0.07       0
  5003.3    0.16       0  5005.0    0.12       0  5006.0    0.07       0
  5111.7     0.1       0
Bank Sta=4996.2,5003.3
Exp/Cntr=0.3,0.1

Type RM Length L Ch R = 1,6700,0,0,0
BEGIN DESCRIPTION:
Mapping XS 265921ac
END DESCRIPTION:
XS GIS Cut Line= 4
      1997523.46     13486862.02      1998237.80     13486431.88
      1998196.57     13486099.85      1997925.28     13485420.55
#Sta/Elev= 30
  3730.7  466.01  3757.8  465.86  3773.4  463.60  3788.9  465.29  3837.6  465.53
  3860.9  464.08  3932.6  463.75  4240.3  457.02  4313.2  454.32  4340.5  455.80
  4386.2  454.94  4398.7  453.94  4408.4  450.34  4414.2  450.23  4421.2  451.40
  4429.8  455.13  4451.1  457.23  4556.9  458.36  4807.3  456.82  4967.2  455.09
  4993.1  449.05  4993.7  448.25  5000.5  449.05  5002.2  451.85  5026.4  456.02
  5114.3  456.32  5320.1  457.31  5427.9  459.34  5572.0  465.89  5630.6  467.35
#Mann=7,-1,0
  3730.7     0.1       0  4240.3    0.16       0  4556.9     0.1       0
  4807.3    0.16       0  4993.1    0.07       0  5000.5    0.16       0
  5114.3     0.1       0
Bank Sta=4993.1,5000.5
Exp/Cntr=0.3,0.1

Chan Stop Cuts=-1