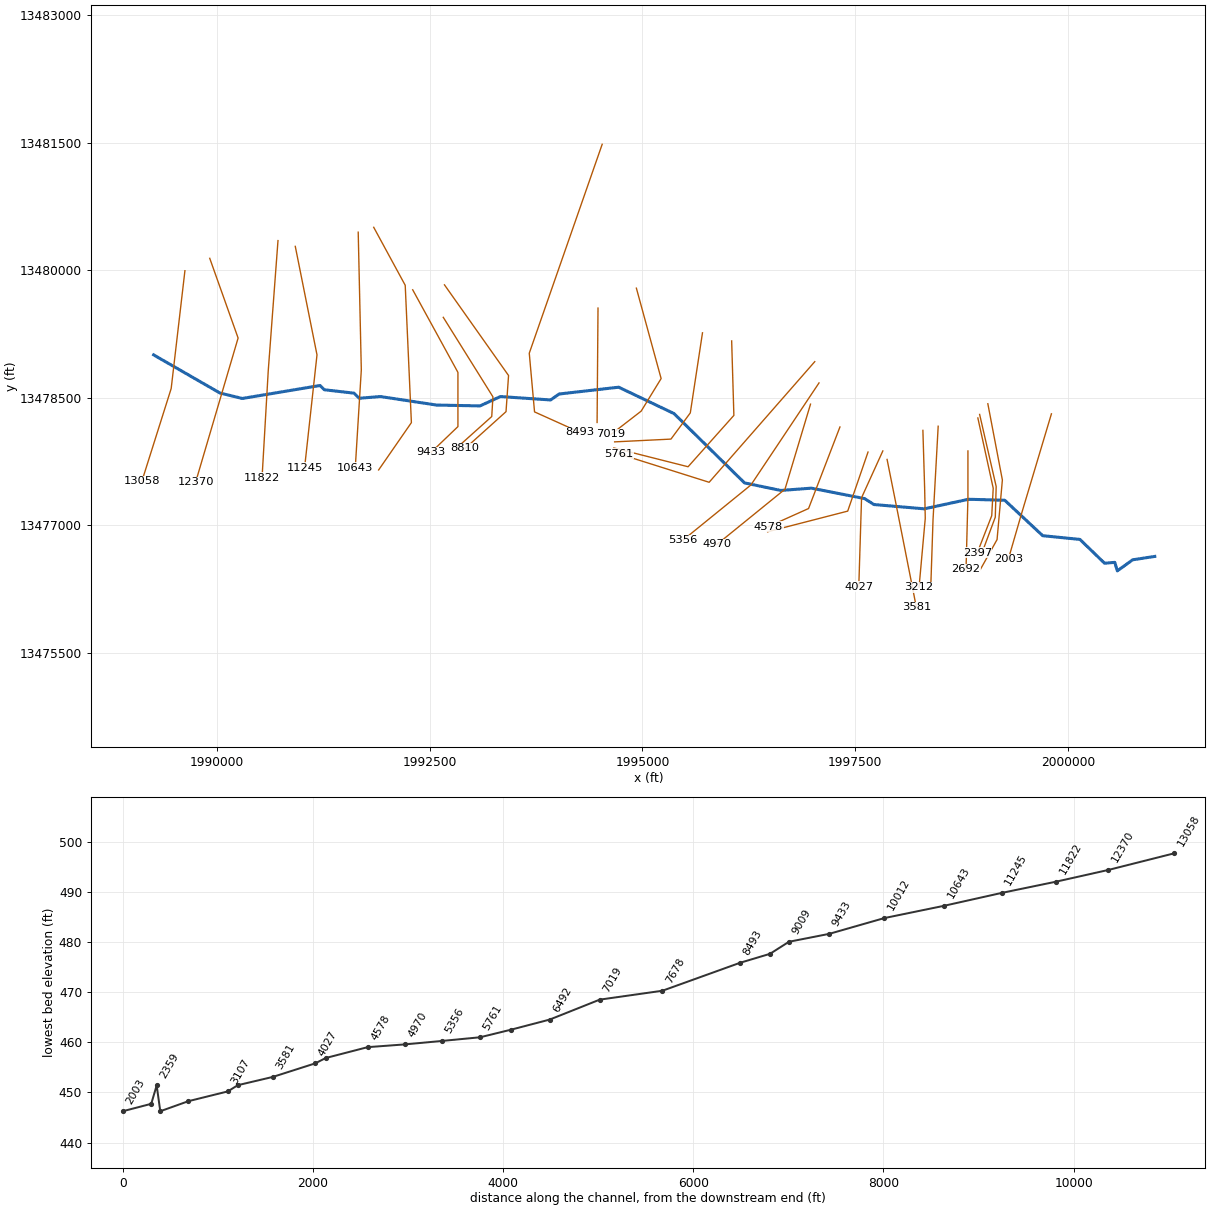
--- UNT 012 in RCW.prj (project) ---

Proj Title=UNT 012 in RCW Base Level Engineering
Current Plan=p01
Default Exp/Contr=0.3,0.1
English Units
Geom File=g01
Flow File=f01
Plan File=p01
Y Axis Title=Elevation
X Axis Title(PF)=Main Channel Distance
X Axis Title(XS)=Station
BEGIN DESCRIPTION:
UNT 012 in RCW
END DESCRIPTION:
DSS Export Rating Curves= 0
DSS Export Rating Curve Sorted= 0
DSS Export Volume Flow Curves= 0
DXF OffsetX= 0
DXF OffsetY= 0
DXF ScaleX= 1
DXF ScaleY= 10

--- UNT 012 in RCW.p01 (plan) ---

Plan Title=Multiple Run
Short Identifier=Multiple
Geom File=g01
Flow File=f01
Subcritical Flow
K Sum by GR= 0
Std Step Tol= 0.01
Critical Tol= 0.01
Num of Std Step Trials= 20
Max Error Tol= 0.3
Flow Tol Ratio= 0.001
Split Flow NTrial= 30
Split Flow Tol= 0.02
Split Flow Ratio= 0.02
Log Output Level= 0
Friction Slope Method= 1
Unsteady Friction Slope Method= 2
Unsteady Bridges Friction Slope Method= 1
Parabolic Critical Depth
Global Vel Dist=  1 , 1 , 1
Global Log Level= 0
CheckData=True
Encroach Param= -1, 0, 0, 0
BEGIN DESCRIPTION:
Multiple Run
END DESCRIPTION:

--- UNT 012 in RCW.f01 (steady flow) ---

Flow Title=Multiple
Program Version=5.05
Number of Profiles= 7
Profile Names=10-year,25-year,50-year,1pct_min,100-year,1pct_plu,500-year
River Rch & RM=UNT 012 in RCW,Reach-1         ,13058
     193     267     328     202     402     803     614
River Rch & RM=UNT 012 in RCW,Reach-1         ,11822
     269     376     466     287     573    1142     880
River Rch & RM=UNT 012 in RCW,Reach-1         ,5356
     358     507     633     393     784    1565    1226
River Rch & RM=UNT 012 in RCW,Reach-1         ,4027
     499     716     902     565    1126    2247    1787
River Rch & RM=UNT 012 in RCW,Reach-1         ,3581
     499     716     902     565    1126    2247    1787
Boundary for River Rch & Prof#=UNT 012 in RCW,Reach-1         , 1
Up Type= 0
Dn Type= 3
Dn Slope=0.005
Boundary for River Rch & Prof#=UNT 012 in RCW,Reach-1         , 2
Up Type= 0
Dn Type= 3
Dn Slope=0.005
Boundary for River Rch & Prof#=UNT 012 in RCW,Reach-1         , 3
Up Type= 0
Dn Type= 3
Dn Slope=0.005
Boundary for River Rch & Prof#=UNT 012 in RCW,Reach-1         , 4
Up Type= 0
Dn Type= 3
Dn Slope=0.005
Boundary for River Rch & Prof#=UNT 012 in RCW,Reach-1         , 5
Up Type= 0
Dn Type= 3
Dn Slope=0.005
Boundary for River Rch & Prof#=UNT 012 in RCW,Reach-1         , 6
Up Type= 0
Dn Type= 3
Dn Slope=0.005
Boundary for River Rch & Prof#=UNT 012 in RCW,Reach-1         , 7
Up Type= 0
Dn Type= 3
Dn Slope=0.005
DSS Import GetInterval= 0
DSS Import GetPeak= 0
DSS Import FillOption= 0

--- UNT 012 in RCW.g01 (geometry) ---

Geom Title=Existing Conditions

River Reach=UNT 012 in RCW,Reach-1
Reach XY= 30
      1989255.80     13479004.54      1990034.56     13478556.31
      1990297.58     13478492.07      1991210.80     13478644.54
      1991260.80     13478594.54      1991610.80     13478554.54
      1991670.80     13478494.54      1991920.80     13478514.54
      1992580.80     13478414.54      1993090.80     13478404.54
      1993330.80     13478514.54      1993920.80     13478474.54
      1994020.80     13478544.54      1994720.80     13478624.54
      1995370.80     13478314.54      1996199.36     13477499.11
      1996625.75     13477410.22      1996985.47     13477437.31
      1997610.80     13477314.54      1997720.80     13477244.54
      1998312.56     13477194.25      1998832.85     13477306.59
      1999257.70     13477294.94      1999703.53     13476878.28
      2000140.80     13476834.54      2000430.80     13476554.54
      2000550.80     13476564.54      2000580.80     13476464.54
      2000760.80     13476594.54      2001020.80     13476634.54

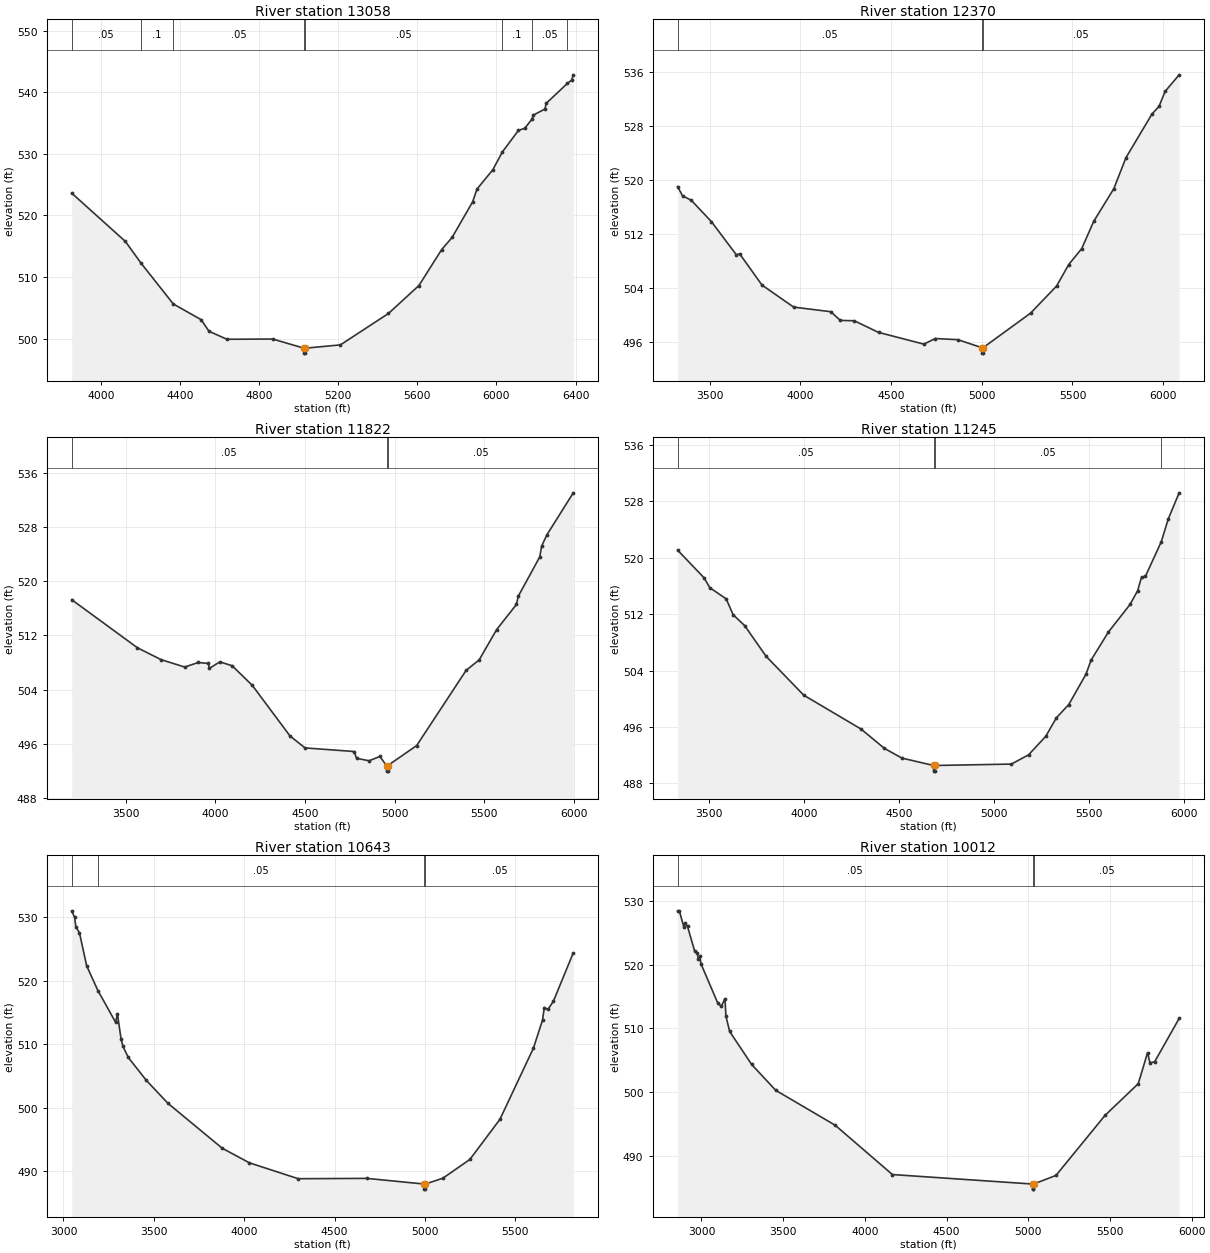
Type RM Length L Ch R = 1,13058,688,688,688
BEGIN DESCRIPTION:
UNT 012 in RCW 24.0
END DESCRIPTION:
XS GIS Cut Line= 3
      1989623.21     13479994.52      1989461.76     13478609.14
      1989118.01     13477520.59
#Sta/Elev= 30
  3852.3  523.61  4123.6  515.77  4201.4  512.30  4365.7  505.62  4506.2  503.07
  4546.5  501.18  4637.1  499.88  4868.7  499.92  5026.7  498.43  5027.2  497.63
  5032.2  497.63  5032.7  498.43  5211.0  498.97  5454.0  504.07  5608.0  508.61
  5723.3  514.46  5775.7  516.41  5879.6  522.20  5901.6  524.27  5981.9  527.42
  6029.9  530.30  6111.2  533.80  6142.8  534.14  6179.7  535.62  6186.3  536.29
  6245.8  537.28  6251.0  538.18  6359.3  541.45  6380.4  541.97  6388.6  542.83
#Mann=8,-1,0
  3852.3    0.05       0  4201.4     0.1       0  4365.7    0.05       0
  5026.7    0.03       0  5032.7    0.05       0  6029.9     0.1       0
  6179.7    0.05       0  6359.3     0.1       0
Bank Sta=5026.7,5032.7
Exp/Cntr=0.3,0.1

Type RM Length L Ch R = 1,12370,548,548,548
BEGIN DESCRIPTION:
UNT 012 in RCW 23.0
END DESCRIPTION:
XS GIS Cut Line= 3
      1989914.87     13480140.42      1990248.22     13479202.89
      1989748.23     13477505.01
#Sta/Elev= 30
  3323.2  518.99  3350.2  517.62  3398.1  516.97  3509.4  513.80  3647.4  508.88
  3665.1  509.04  3788.4  504.41  3962.9  501.15  4167.4  500.47  4220.5  499.18
  4296.9  499.13  4430.7  497.41  4680.9  495.67  4743.4  496.50  4868.5  496.33
  5001.1  495.14  5001.6  494.34  5006.6  494.34  5007.1  495.14  5268.8  500.25
  5412.6  504.27  5479.2  507.44  5551.1  509.81  5617.8  513.87  5728.2  518.68
  5794.9  523.26  5938.7  529.73  5977.2  530.84  6010.6  533.06  6088.2  535.52
#Mann=3,-1,0
  3323.2    0.05       0  5001.1    0.03       0  5007.1    0.05       0
Bank Sta=5001.1,5007.1
Exp/Cntr=0.3,0.1

Type RM Length L Ch R = 1,11822,577,577,577
BEGIN DESCRIPTION:
UNT 012 in RCW 22.0
END DESCRIPTION:
XS GIS Cut Line= 3
      1990716.97     13480348.71      1990602.39     13478817.48
      1990529.55     13477558.50
#Sta/Elev= 30
  3199.9  517.27  3565.5  510.20  3697.7  508.44  3829.8  507.35  3905.6  508.02
  3962.0  507.87  3967.0  507.15  4025.9  508.11  4094.2  507.54  4206.4  504.66
  4417.0  497.19  4500.8  495.43  4774.8  494.90  4788.0  493.90  4858.1  493.54
  4918.2  494.17  4955.2  492.81  4955.7  492.01  4960.8  492.01  4961.3  492.81
  5123.3  495.78  5399.0  506.86  5471.7  508.40  5569.3  512.87  5679.5  516.57
  5689.5  517.77  5809.7  523.58  5820.2  525.18  5849.8  526.85  5996.5  533.02
#Mann=3,-1,0
  3199.9    0.05       0  4955.2    0.03       0  4961.3    0.05       0
Bank Sta=4955.2,4961.3
Exp/Cntr=0.3,0.1

Type RM Length L Ch R = 1,11245,602,602,602
BEGIN DESCRIPTION:
UNT 012 in RCW 21.0
END DESCRIPTION:
XS GIS Cut Line= 3
      1990920.10     13480281.00      1991175.30     13479004.98
      1991029.64     13477678.44
#Sta/Elev= 30
  3336.1  521.10  3474.8  517.18  3505.4  515.77  3591.3  514.19  3627.8  511.94
  3688.2  510.40  3801.1  506.04  3999.2  500.52  4300.1  495.72  4423.2  492.97
  4515.0  491.60  4681.2  490.55  4681.7  489.75  4686.9  489.75  4687.4  490.55
  5090.1  490.75  5180.6  492.06  5271.2  494.70  5326.9  497.32  5391.9  499.20
  5482.4  503.51  5509.1  505.50  5600.1  509.48  5713.8  513.39  5754.0  515.36
  5774.2  517.28  5794.3  517.37  5878.1  522.30  5915.0  525.55  5971.9  529.23
#Mann=4,-1,0
  3336.1    0.05       0  4681.2   0.035       0  4687.4    0.05       0
  5878.1     0.1       0
Bank Sta=4681.2,4687.4
Exp/Cntr=0.3,0.1

Type RM Length L Ch R = 1,10643,631,631,631
BEGIN DESCRIPTION:
UNT 012 in RCW 20.0
END DESCRIPTION:
XS GIS Cut Line= 3
      1991659.68     13480447.69      1991696.14     13478827.89
      1991625.00     13477675.00
#Sta/Elev= 30
  3045.8  530.99  3061.8  529.97  3068.5  528.50  3088.5  527.52  3128.5  522.33
  3190.5  518.45  3288.6  513.45  3298.6  514.78  3318.6  510.84  3328.6  509.71
  3358.6  507.92  3458.6  504.31  3578.6  500.69  3878.7  493.63  4028.7  491.34
  4298.8  488.84  4678.9  488.89  4996.4  488.00  4996.9  487.20  5002.1  487.20
  5002.6  488.00  5099.7  488.92  5248.9  491.87  5415.2  498.18  5600.7  509.39
  5650.8  513.79  5660.8  515.77  5680.8  515.47  5710.9  516.75  5821.1  524.38
#Mann=4,-1,0
  3045.8     0.1       0  3190.5    0.05       0  4996.4   0.035       0
  5002.6    0.05       0
Bank Sta=4996.4,5002.6
Exp/Cntr=0.3,0.1

Type RM Length L Ch R = 1,10012,579,579,579
BEGIN DESCRIPTION:
UNT 012 in RCW 19.0
END DESCRIPTION:
XS GIS Cut Line= 4
      1991841.99     13480504.94      1992212.18     13479823.17
      1992284.68     13478208.10      1991899.64     13477651.36
#Sta/Elev= 30
  2854.2  528.45  2865.4  528.39  2893.0  525.86  2899.6  526.59  2914.8  526.00
  2958.5  522.12  2974.7  521.87  2980.4  520.90  2990.7  521.29  2996.5  520.17
  3100.1  513.95  3122.0  513.45  3143.9  514.66  3150.0  511.90  3172.7  509.50
  3307.3  504.32  3454.6  500.26  3818.3  494.78  4168.7  487.03  5026.5  485.54
  5027.0  484.74  5032.2  484.74  5032.7  485.54  5169.7  486.89  5470.6  496.34
  5673.4  501.30  5730.1  506.16  5745.0  504.59  5773.3  504.73  5923.6  511.55
#Mann=3,-1,0
  2854.2    0.05       0  5026.5   0.035       0  5032.7    0.05       0
Bank Sta=5026.5,5032.7
Exp/Cntr=0.3,0.1

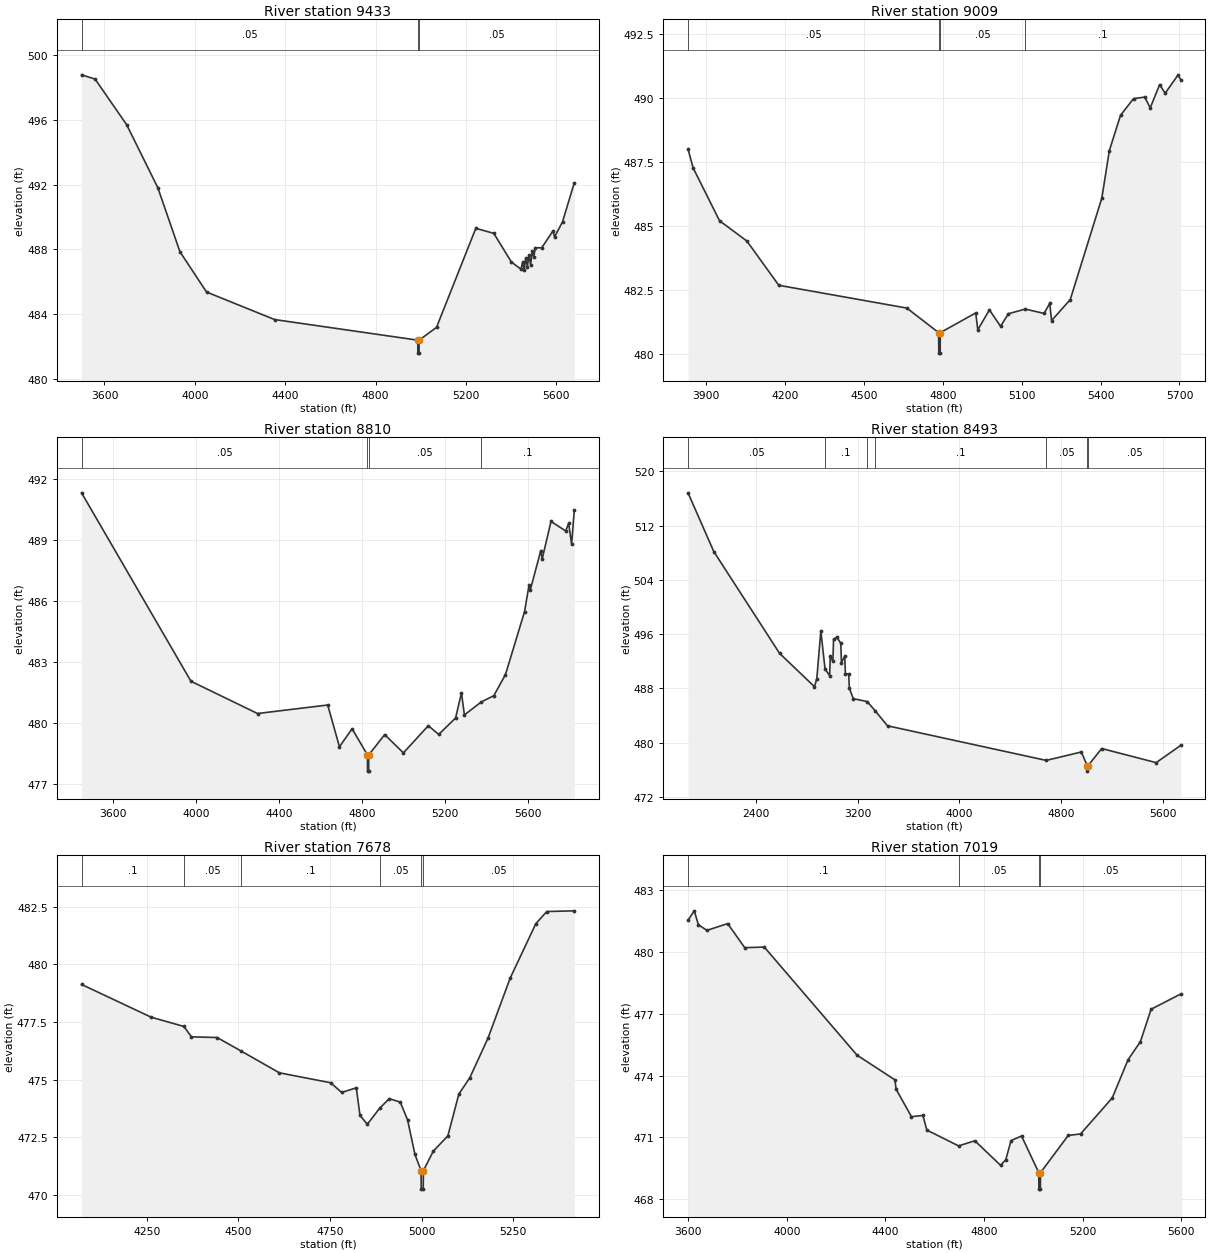
Type RM Length L Ch R = 1,9433,424,424,424
BEGIN DESCRIPTION:
UNT 012 in RCW 18.0
END DESCRIPTION:
XS GIS Cut Line= 4
      1992300.07     13479770.15      1992831.55     13478798.75
      1992831.55     13478161.23      1992516.98     13477859.35
#Sta/Elev= 30
  3498.5  498.77  3558.3  498.51  3698.2  495.69  3836.2  491.80  3933.8  487.86
  4051.5  485.37  4353.1  483.67  4986.4  482.40  4986.9  481.60  4992.1  481.60
  4992.6  482.40  5069.5  483.19  5243.3  489.30  5323.0  488.99  5400.9  487.22
  5443.4  486.78  5450.3  487.20  5457.5  486.74  5464.5  487.49  5471.7  486.94
  5478.6  487.67  5485.8  487.05  5492.8  487.89  5500.0  487.56  5506.9  488.10
  5535.2  488.10  5584.9  489.14  5591.8  488.77  5627.1  489.70  5679.3  492.11
#Mann=3,-1,0
  3498.5    0.05       0  4986.4   0.035       0  4992.6    0.05       0
Bank Sta=4986.4,4992.6
Exp/Cntr=0.3,0.1

Type RM Length L Ch R = 1,9009,199,199,199
BEGIN DESCRIPTION:
UNT 012 in RCW 17.0
END DESCRIPTION:
XS GIS Cut Line= 4
      1992659.45     13479446.35      1993242.81     13478511.43
      1993228.92     13478279.66      1992826.98     13477919.30
#Sta/Elev= 30
  3831.0  487.99  3850.6  487.25  3950.9  485.19  4054.7  484.40  4176.2  482.67
  4663.2  481.78  4784.2  480.82  4784.7  480.02  4789.9  480.02  4790.4  480.82
  4925.3  481.59  4933.0  480.93  4977.2  481.71  5019.6  481.07  5049.6  481.56
  5114.0  481.74  5185.1  481.57  5206.8  481.97  5213.5  481.29  5284.6  482.11
  5404.9  486.08  5433.3  487.93  5475.9  489.31  5525.3  489.96  5567.9  490.02
  5588.8  489.60  5624.7  490.51  5645.6  490.17  5695.0  490.89  5705.0  490.69
#Mann=4,-1,0
  3831.0    0.05       0  4784.2   0.035       0  4790.4    0.05       0
  5114.0     0.1       0
Bank Sta=4784.2,4790.4
Exp/Cntr=0.3,0.1

Type RM Length L Ch R = 1,8810,317,317,317
BEGIN DESCRIPTION:
Mapping XS 4db7ea2c
END DESCRIPTION:
XS GIS Cut Line= 4
      1992673.36     13479828.27      1993426.47     13478762.08
      1993396.72     13478336.87      1992916.45     13477904.69
#Sta/Elev= 30
  3446.5  491.34  3974.4  482.05  4295.7  480.46  4634.3  480.88  4690.9  478.82
  4751.9  479.71  4826.0  478.42  4826.5  477.62  4831.7  477.62  4832.2  478.42
  4909.3  479.42  4999.5  478.52  5119.8  479.86  5170.0  479.43  5251.3  480.24
  5279.7  481.48  5293.9  480.39  5375.1  481.03  5435.9  481.34  5492.0  482.38
  5584.0  485.48  5605.6  486.78  5612.3  486.57  5662.4  488.49  5669.1  488.08
  5711.7  489.93  5782.7  489.46  5796.9  489.84  5811.1  488.81  5824.2  490.50
#Mann=4,-1,0
  3446.5    0.05       0  4826.0   0.035       0  4832.2    0.05       0
  5375.1     0.1       0
Bank Sta=4826,4832.2
Exp/Cntr=0.3,0.1

Type RM Length L Ch R = 1,8493,815,815,815
BEGIN DESCRIPTION:
UNT 012 in RCW 16.0
END DESCRIPTION:
XS GIS Cut Line= 4
      1994526.87     13481481.54      1993669.89     13479024.45
      1993731.96     13478334.08      1994261.59     13478095.23
#Sta/Elev= 30
  1865.7  516.83  2068.6  508.17  2586.2  493.17  2860.6  488.26  2878.8  489.45
  2910.5  496.48  2943.6  490.88  2979.5  489.89  2984.8  492.77  3005.3  491.99
  3010.6  495.22  3036.4  495.56  3067.4  494.66  3072.7  491.82  3098.5  492.76
  3103.8  490.19  3129.6  490.13  3134.9  488.02  3165.9  486.50  3275.5  486.07
  3336.2  484.75  3435.0  482.50  4683.8  477.40  4959.4  478.64  5006.5  476.62
  5007.0  475.82  5012.7  476.62  5120.0  479.15  5548.4  477.07  5742.1  479.62
#Mann=7,-1,0
  1865.7    0.05       0  2943.6     0.1       0  3275.5    0.05       0
  3336.2     0.1       0  4683.8    0.05       0  5006.5   0.035       0
  5012.7    0.05       0
Bank Sta=5006.5,5012.7
Exp/Cntr=0.3,0.1

Type RM Length L Ch R = 1,7678,659,659,659
BEGIN DESCRIPTION:
Mapping XS 2dd8a4c2
END DESCRIPTION:
XS GIS Cut Line= 2
      1994477.83     13479555.04      1994466.98     13478209.79
#Sta/Elev= 30
  4071.8  479.13  4261.9  477.71  4351.1  477.31  4371.9  476.86  4441.9  476.83
  4507.9  476.24  4611.9  475.30  4751.9  474.87  4781.9  474.45  4821.9  474.65
  4831.9  473.46  4851.9  473.07  4885.9  473.77  4911.9  474.18  4941.9  474.03
  4961.9  473.26  4981.9  471.77  4998.7  471.06  4999.2  470.26  5004.6  470.26
  5005.1  471.06  5031.9  471.90  5071.9  472.57  5101.9  474.38  5131.9  475.09
  5181.9  476.82  5241.9  479.40  5311.9  481.76  5341.9  482.29  5417.1  482.32
#Mann=6,-1,0
  4071.8     0.1       0  4351.1    0.05       0  4507.9     0.1       0
  4885.9    0.05       0  4998.7   0.035       0  5005.1    0.05       0
Bank Sta=4998.7,5005.1
Exp/Cntr=0.3,0.1

Type RM Length L Ch R = 1,7019,527,527,527
BEGIN DESCRIPTION:
UNT 012 in RCW 15.0
END DESCRIPTION:
XS GIS Cut Line= 4
      1994928.68     13479789.39      1995219.48     13478726.01
      1994985.20     13478343.52      1994630.86     13478069.32
#Sta/Elev= 30
  3599.3  481.55  3624.6  482.01  3641.2  481.34  3675.7  481.06  3760.2  481.39
  3829.3  480.22  3908.6  480.25  4284.8  475.00  4438.4  473.80  4443.6  473.34
  4505.8  472.01  4552.3  472.07  4568.0  471.36  4697.1  470.59  4762.8  470.84
  4867.1  469.65  4888.4  469.92  4909.7  470.85  4952.3  471.07  5022.3  469.29
  5022.8  468.49  5028.7  468.49  5029.2  469.29  5141.9  471.10  5191.7  471.17
  5320.3  472.92  5384.6  474.78  5434.4  475.65  5477.9  477.23  5598.3  477.97
#Mann=4,-1,0
  3599.3     0.1       0  4697.1    0.05       0  5022.3   0.035       0
  5029.2    0.05       0
Bank Sta=5022.3,5029.2
Exp/Cntr=0.3,0.1

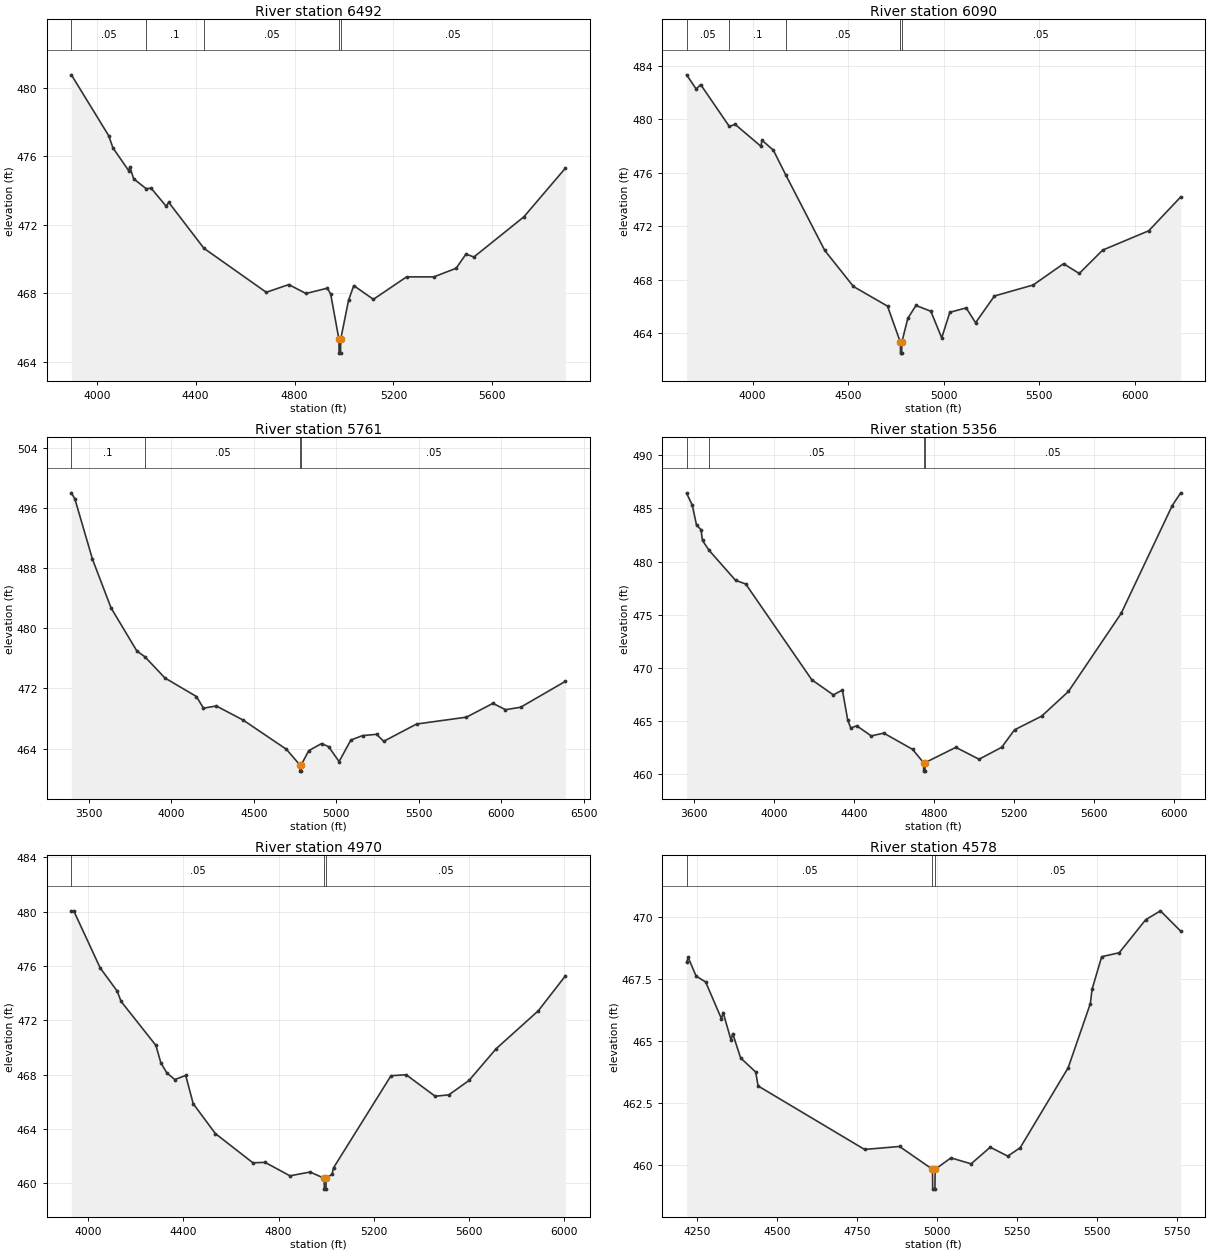
Type RM Length L Ch R = 1,6492,402,402,402
BEGIN DESCRIPTION:
UNT 012 in RCW 14.0
END DESCRIPTION:
XS GIS Cut Line= 4
      1995705.59     13479264.20      1995562.36     13478322.36
      1995335.04     13478014.20      1994673.13     13477981.65
#Sta/Elev= 30
  3897.6  480.75  4048.5  477.20  4065.7  476.49  4129.3  475.16  4134.4  475.36
  4149.7  474.68  4199.8  474.11  4220.5  474.13  4281.2  473.08  4291.3  473.31
  4433.5  470.63  4685.8  468.06  4776.8  468.51  4846.4  467.99  4933.1  468.30
  4946.4  467.95  4979.8  465.31  4980.3  464.51  4986.2  464.51  4986.7  465.31
  5018.7  467.60  5039.6  468.45  5119.0  467.65  5253.3  468.96  5363.4  468.96
  5453.5  469.46  5493.5  470.29  5525.5  470.12  5727.4  472.46  5895.9  475.31
#Mann=5,-1,0
  3897.6    0.05       0  4199.8     0.1       0  4433.5    0.05       0
  4979.8   0.035       0  4986.7    0.05       0
Bank Sta=4979.8,4986.7
Exp/Cntr=0.3,0.1

Type RM Length L Ch R = 1,6090,329,329,329
BEGIN DESCRIPTION:
UNT 012 in RCW 13.0
END DESCRIPTION:
XS GIS Cut Line= 4
      1996048.47     13479168.68      1996074.42     13478293.01
      1995536.27     13477689.00      1994663.95     13477910.03
#Sta/Elev= 30
  3655.0  483.31  3705.1  482.25  3728.7  482.58  3878.7  479.45  3908.8  479.61
  4044.0  477.97  4049.0  478.43  4108.9  477.68  4174.3  475.82  4377.9  470.19
  4527.6  467.50  4706.1  466.03  4773.7  463.32  4774.2  462.52  4780.1  462.52
  4780.6  463.32  4812.3  465.12  4854.9  466.08  4932.7  465.65  4989.6  463.66
  5032.2  465.57  5117.5  465.90  5166.8  464.79  5265.5  466.79  5468.2  467.61
  5627.0  469.20  5709.0  468.47  5832.0  470.22  6072.8  471.66  6239.9  474.19
#Mann=5,-1,0
  3655.0    0.05       0  3878.7     0.1       0  4174.3    0.05       0
  4773.7   0.035       0  4780.6    0.05       0
Bank Sta=4773.7,4780.6
Exp/Cntr=0.3,0.1

Type RM Length L Ch R = 1,5761,405,405,405
BEGIN DESCRIPTION:
UNT 012 in RCW 12.0
END DESCRIPTION:
XS GIS Cut Line= 3
      1997024.99     13478924.99      1995783.71     13477506.39
      1994725.64     13477840.29
#Sta/Elev= 30
  3395.1  498.03  3416.4  497.22  3522.7  489.21  3635.7  482.71  3792.3  476.97
  3840.3  476.22  3962.2  473.39  4153.0  470.92  4195.7  469.37  4273.5  469.66
  4436.7  467.78  4698.7  463.89  4780.7  461.79  4781.2  460.99  4787.1  460.99
  4787.6  461.79  4833.5  463.71  4911.3  464.66  4954.0  464.25  5017.6  462.26
  5088.8  465.13  5160.0  465.72  5244.4  465.89  5288.0  464.96  5487.3  467.26
  5788.9  468.17  5949.9  470.01  6025.8  469.17  6117.6  469.49  6389.6  472.95
#Mann=4,-1,0
  3395.1     0.1       0  3840.3    0.05       0  4780.7   0.035       0
  4787.6    0.05       0
Bank Sta=4780.7,4787.6
Exp/Cntr=0.3,0.1

Type RM Length L Ch R = 1,5356,386,386,386
BEGIN DESCRIPTION:
UNT 012 in RCW 11.0
END DESCRIPTION:
XS GIS Cut Line= 3
      1997075.00     13478675.00      1996275.00     13477475.00
      1995475.00     13476825.00
#Sta/Elev= 30
  3563.0  486.43  3591.5  485.31  3612.6  483.43  3635.1  483.00  3642.6  481.98
  3676.1  481.04  3807.9  478.23  3859.0  477.88  4189.5  468.86  4297.6  467.43
  4342.7  467.89  4369.7  465.04  4384.8  464.31  4414.8  464.52  4486.9  463.57
  4550.0  463.83  4694.2  462.30  4748.8  461.05  4749.5  460.25  4756.2  460.25
  4756.9  461.05  4910.6  462.49  5026.8  461.37  5140.3  462.50  5204.2  464.14
  5340.0  465.43  5474.3  467.76  5737.9  475.11  5993.6  485.27  6036.0  486.47
#Mann=4,-1,0
  3563.0     0.1       0  3676.1    0.05       0  4748.8   0.035       0
  4756.9    0.05       0
Bank Sta=4748.8,4756.9
Exp/Cntr=0.3,0.1

Type RM Length L Ch R = 1,4970,392,392,392
BEGIN DESCRIPTION:
UNT 012 in RCW 10.0
END DESCRIPTION:
XS GIS Cut Line= 3
      1996975.00     13478424.99      1996675.00     13477425.00
      1995875.00     13476775.00
#Sta/Elev= 30
  3929.7  480.06  3940.1  480.04  4050.6  475.86  4122.0  474.15  4138.5  473.39
  4284.7  470.15  4305.5  468.87  4330.8  468.12  4363.8  467.64  4409.9  467.94
  4441.3  465.86  4534.4  463.66  4691.8  461.51  4743.2  461.54  4847.6  460.55
  4932.0  460.83  4991.1  460.37  4991.9  459.57  4998.7  459.57  4999.4  460.37
  5024.0  460.66  5030.5  461.14  5271.8  467.92  5335.7  467.99  5457.1  466.41
  5514.6  466.51  5599.4  467.57  5712.9  469.90  5890.3  472.70  6004.5  475.28
#Mann=3,-1,0
  3929.7    0.05       0  4991.1   0.035       0  4999.4    0.05       0
Bank Sta=4991.1,4999.4
Exp/Cntr=0.3,0.1

Type RM Length L Ch R = 1,4578,442,442,442
BEGIN DESCRIPTION:
Mapping XS cd9c09e2
END DESCRIPTION:
XS GIS Cut Line= 3
      1997320.98     13478156.87      1996952.07     13477197.68
      1996479.50     13476985.25
#Sta/Elev= 30
  4216.3  468.16  4221.3  468.36  4246.0  467.61  4276.0  467.37  4325.3  465.89
  4330.6  466.14  4355.3  465.03  4360.6  465.29  4385.3  464.31  4432.6  463.74
  4439.9  463.18  4773.1  460.62  4882.4  460.74  4985.5  459.82  4986.3  459.02
  4993.2  459.02  4993.9  459.82  5043.3  460.28  5106.3  460.04  5166.3  460.71
  5221.0  460.35  5260.0  460.69  5409.9  463.91  5479.4  466.50  5484.8  467.08
  5514.9  468.39  5569.7  468.55  5652.4  469.88  5698.7  470.24  5762.1  469.42
#Mann=3,-1,0
  4216.3    0.05       0  4985.5   0.035       0  4993.9    0.05       0
Bank Sta=4985.5,4993.9
Exp/Cntr=0.3,0.1

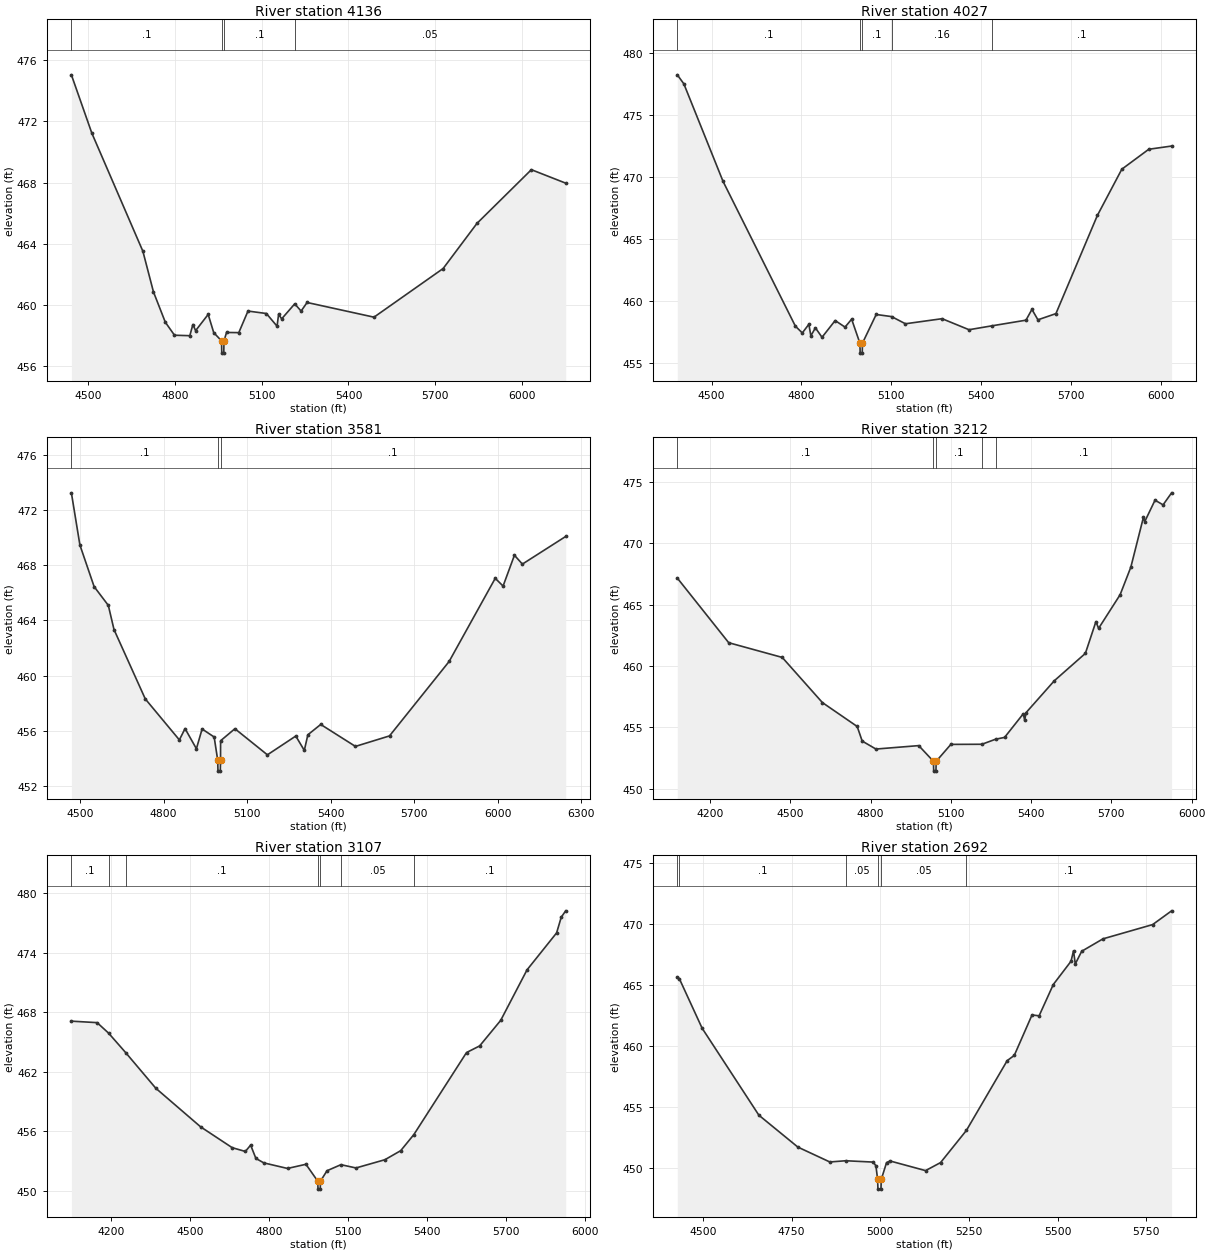
Type RM Length L Ch R = 1,4136,109,109,109
BEGIN DESCRIPTION:
Mapping XS 3794c4a6
END DESCRIPTION:
XS GIS Cut Line= 3
      1997650.87     13477861.79      1997412.14     13477167.30
      1996470.26     13476924.24
#Sta/Elev= 30
  4443.0  475.04  4513.6  471.23  4689.9  463.51  4726.5  460.85  4767.4  458.87
  4799.1  458.02  4852.0  457.99  4862.6  458.72  4872.1  458.32  4915.4  459.38
  4934.6  458.19  4961.6  457.65  4962.4  456.85  4969.3  456.85  4970.0  457.65
  4978.9  458.20  5021.2  458.19  5052.9  459.60  5116.4  459.44  5153.3  458.61
  5158.7  459.39  5169.2  459.09  5214.3  460.07  5236.4  459.60  5257.0  460.16
  5488.1  459.20  5726.9  462.38  5843.7  465.33  6031.6  468.84  6150.1  467.96
#Mann=4,-1,0
  4443.0     0.1       0  4961.6    0.07       0  4970.0     0.1       0
  5214.3    0.05       0
Bank Sta=4961.6,4970
Exp/Cntr=0.3,0.1

Type RM Length L Ch R = 1,4027,446,446,446
BEGIN DESCRIPTION:
UNT 012 in RCW 8.0
END DESCRIPTION:
XS GIS Cut Line= 3
      1997824.99     13477874.98      1997575.00     13477325.00
      1997542.38     13476278.74
#Sta/Elev= 30
  4385.4  478.26  4407.3  477.53  4538.1  469.66  4779.7  457.97  4802.8  457.42
  4824.8  458.12  4831.4  457.19  4846.7  457.83  4868.7  457.07  4912.6  458.42
  4945.6  457.89  4967.6  458.53  4995.3  456.59  4996.1  455.79  5003.0  455.79
  5003.7  456.59  5049.6  458.91  5101.0  458.74  5147.3  458.16  5269.7  458.57
  5359.7  457.68  5437.5  458.00  5549.8  458.45  5569.8  459.32  5589.8  458.48
  5649.9  458.98  5788.4  466.91  5870.0  470.64  5960.0  472.25  6036.3  472.51
#Mann=5,-1,0
  4385.4     0.1       0  4995.3    0.07       0  5003.7     0.1       0
  5101.0    0.16       0  5437.5     0.1       0
Bank Sta=4995.3,5003.7
Exp/Cntr=0.3,0.1

Type RM Length L Ch R = 1,3581,369,369,369
BEGIN DESCRIPTION:
UNT 012 in RCW 7.0
END DESCRIPTION:
XS GIS Cut Line= 3
      1997874.99     13477775.04      1997975.00     13477275.00
      1998219.43     13476034.50
#Sta/Elev= 30
  4469.2  473.24  4499.8  469.46  4550.8  466.45  4601.8  465.09  4622.2  463.34
  4734.4  458.32  4856.8  455.35  4877.2  456.17  4918.0  454.71  4938.4  456.14
  4981.7  455.56  4994.4  453.89  4995.4  453.09  5003.7  453.09  5004.6  453.89
  5004.8  455.29  5056.2  456.16  5172.8  454.27  5274.7  455.63  5305.3  454.59
  5318.0  455.72  5364.2  456.47  5488.8  454.88  5611.1  455.64  5825.1  461.03
  5990.6  467.05  6018.8  466.49  6059.5  468.72  6088.1  468.08  6243.5  470.08
#Mann=3,-1,0
  4469.2     0.1       0  4994.4    0.07       0  5004.6     0.1       0
Bank Sta=4994.4,5004.6
Exp/Cntr=0.3,0.1

Type RM Length L Ch R = 1,3212,105,105,105
BEGIN DESCRIPTION:
Mapping XS 248023f3
END DESCRIPTION:
XS GIS Cut Line= 4
      1998295.82     13478116.98      1998316.65     13477422.51
      1998323.59     13477082.23      1998250.68     13476273.25
#Sta/Elev= 30
  4077.7  467.18  4269.8  461.91  4469.9  460.71  4619.9  457.03  4750.0  455.08
  4768.7  453.89  4820.0  453.24  4980.0  453.52  5035.0  452.24  5035.9  451.44
  5044.3  451.44  5045.2  452.24  5100.1  453.62  5216.2  453.63  5267.0  454.04
  5300.8  454.19  5370.9  456.12  5375.9  455.58  5381.2  456.21  5486.8  458.81
  5602.8  461.04  5642.2  463.63  5652.2  463.08  5732.6  465.82  5772.7  468.07
  5819.6  472.12  5824.6  471.78  5863.1  473.53  5893.2  473.15  5925.1  474.13
#Mann=5,-1,0
  4077.7     0.1       0  5035.0    0.07       0  5045.2     0.1       0
  5216.2    0.05       0  5267.0     0.1       0
Bank Sta=5035,5045.2
Exp/Cntr=0.3,0.1

Type RM Length L Ch R = 1,3107,415,415,415
BEGIN DESCRIPTION:
UNT 012 in RCW 6.0
END DESCRIPTION:
XS GIS Cut Line= 3
      1998475.50     13478165.56      1998414.74     13477063.14
      1998388.76     13476288.07
#Sta/Elev= 30
  4048.3  467.10  4146.2  466.95  4189.6  465.90  4254.6  463.94  4369.3  460.35
  4539.6  456.47  4659.8  454.37  4709.9  453.99  4729.9  454.63  4749.9  453.29
  4780.0  452.84  4870.1  452.28  4940.2  452.70  4985.2  451.00  4986.1  450.20
  4994.5  450.20  4995.4  451.00  5020.3  452.05  5073.2  452.66  5130.5  452.33
  5240.6  453.16  5300.6  454.07  5350.6  455.69  5550.8  463.94  5600.8  464.61
  5680.8  467.18  5780.9  472.26  5893.4  475.98  5911.0  477.56  5927.9  478.20
#Mann=7,-1,0
  4048.3     0.1       0  4189.6    0.05       0  4254.6     0.1       0
  4985.2    0.07       0  4995.4     0.1       0  5073.2    0.05       0
  5350.6     0.1       0
Bank Sta=4985.2,4995.4
Exp/Cntr=0.3,0.1

Type RM Length L Ch R = 1,2692,295,295,295
BEGIN DESCRIPTION:
UNT 012 in RCW 5.0
END DESCRIPTION:
XS GIS Cut Line= 3
      1998825.00     13477874.95      1998825.00     13477325.00
      1998802.76     13476481.55
#Sta/Elev= 30
  4427.7  465.65  4433.6  465.52  4497.7  461.46  4657.7  454.32  4767.7  451.70
  4857.7  450.48  4902.7  450.58  4980.2  450.47  4987.7  450.16  4992.5  449.05
  4993.4  448.25  5001.9  448.25  5002.8  449.05  5017.7  450.43  5027.7  450.56
  5127.7  449.77  5170.0  450.43  5242.8  453.07  5357.8  458.80  5377.8  459.23
  5427.8  462.55  5447.8  462.48  5487.8  465.05  5537.8  466.96  5544.8  467.82
  5549.8  466.74  5567.9  467.78  5627.9  468.80  5767.9  469.97  5821.4  471.10
#Mann=6,-1,0
  4427.7    0.05       0  4433.6     0.1       0  4902.7    0.05       0
  4992.5    0.03       0  5002.8    0.05       0  5242.8     0.1       0
Bank Sta=4992.5,5002.8
Exp/Cntr=0.3,0.1

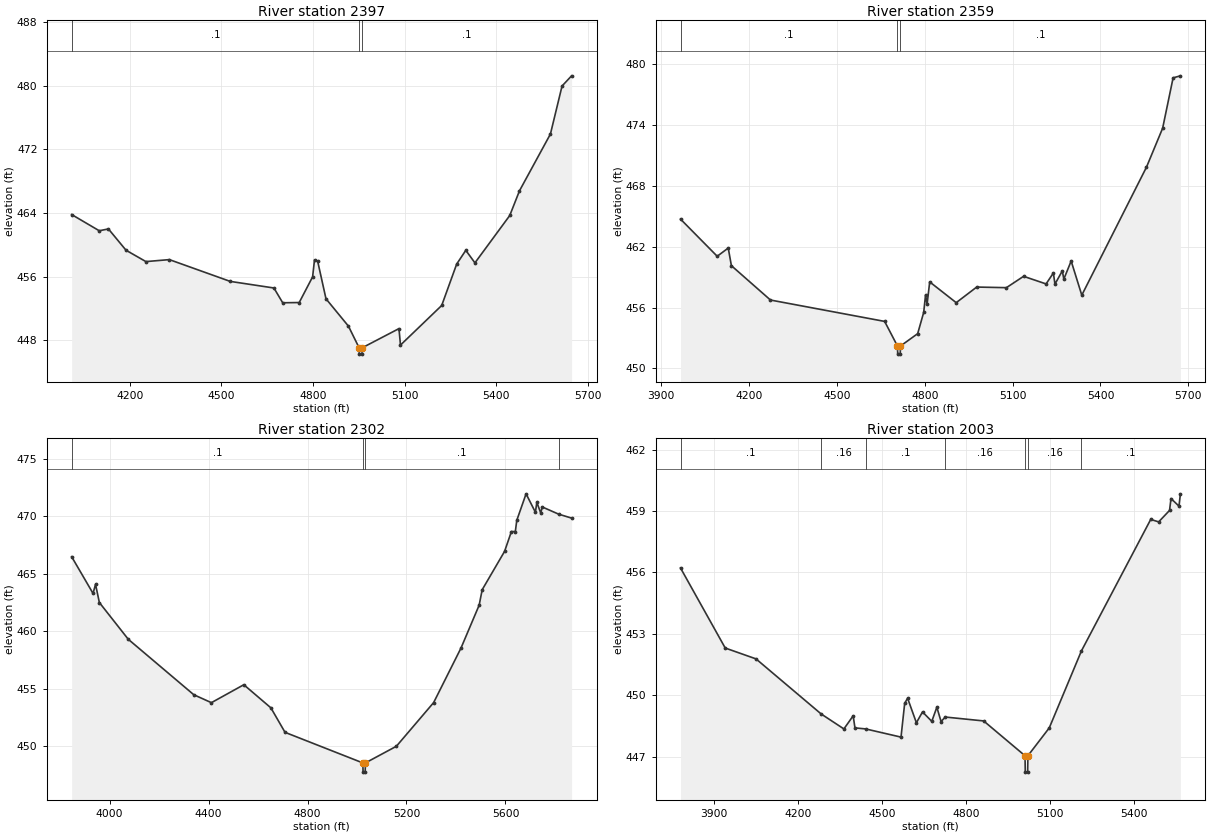
Type RM Length L Ch R = 1,2397,38,38,38
BEGIN DESCRIPTION:
Mapping XS ea842a51
END DESCRIPTION:
XS GIS Cut Line= 4
      1998941.66     13478262.76      1999122.21     13477436.40
      1999104.84     13477113.48      1998934.69     13476675.94
#Sta/Elev= 30
  4008.9  463.81  4099.3  461.77  4129.4  462.00  4187.1  459.32  4252.3  457.89
  4329.1  458.14  4528.6  455.40  4671.9  454.57  4700.7  452.71  4754.8  452.74
  4798.7  455.97  4805.0  458.12  4815.2  457.95  4842.6  453.21  4916.2  449.77
  4951.1  447.05  4952.0  446.25  4960.5  446.25  4961.4  447.05  5081.8  449.46
  5086.8  447.39  5221.9  452.37  5271.0  457.58  5300.9  459.31  5330.8  457.73
  5445.0  463.69  5476.9  466.80  5578.3  473.94  5616.4  479.98  5647.6  481.26
#Mann=3,-1,0
  4008.9     0.1       0  4951.1    0.07       0  4961.4     0.1       0
Bank Sta=4951.1,4961.4
Exp/Cntr=0.3,0.1

Type RM Length L Ch R = 1,2359,57,57,57
BEGIN DESCRIPTION:
Mapping XS 511ef433
END DESCRIPTION:
XS GIS Cut Line= 4
      1998962.49     13478304.41      1999156.93     13477457.23
      1999146.51     13477096.12      1998980.26     13476649.32
#Sta/Elev= 30
  3965.8  464.73  4091.1  461.06  4128.8  461.87  4139.6  460.13  4273.0  456.74
  4662.9  454.63  4706.7  452.20  4707.6  451.40  4716.1  451.40  4717.0  452.20
  4775.7  453.42  4796.3  455.52  4802.7  457.26  4807.8  456.31  4816.8  458.53
  4907.3  456.48  4977.3  458.02  5078.8  457.96  5137.4  459.08  5214.2  458.33
  5239.2  459.41  5244.5  458.31  5269.6  459.61  5274.9  458.81  5299.9  460.59
  5336.2  457.22  5557.0  469.85  5612.3  473.70  5648.0  478.67  5673.0  478.87
#Mann=3,-1,0
  3965.8     0.1       0  4706.7    0.07       0  4717.0     0.1       0
Bank Sta=4706.7,4717
Exp/Cntr=0.3,0.1

Type RM Length L Ch R = 1,2302,299,299,299
BEGIN DESCRIPTION:
UNT 012 in RCW 4.0
END DESCRIPTION:
XS GIS Cut Line= 4
      1999059.03     13478429.83      1999229.84     13477533.62
      1999167.34     13476832.23      1998970.27     13476479.57
#Sta/Elev= 30
  3846.8  466.46  3933.2  463.27  3943.3  464.06  3958.7  462.48  4075.7  459.28
  4340.4  454.46  4411.6  453.77  4542.6  455.33  4652.0  453.32  4709.2  451.19
  5023.7  448.53  5024.6  447.73  5033.1  447.73  5034.0  448.53  5159.3  449.98
  5309.9  453.78  5420.4  458.52  5493.8  462.25  5506.0  463.59  5596.6  466.93
  5624.1  468.65  5640.0  468.65  5645.8  469.62  5683.4  471.93  5721.1  470.33
  5726.9  471.19  5742.8  470.26  5748.6  470.79  5815.3  470.16  5867.3  469.82
#Mann=4,-1,0
  3846.8     0.1       0  5023.7    0.07       0  5034.0     0.1       0
  5815.3    0.05       0
Bank Sta=5023.7,5034
Exp/Cntr=0.3,0.1

Type RM Length L Ch R = 1,2003,0,0,0
BEGIN DESCRIPTION:
Mapping XS 546bba33
END DESCRIPTION:
XS GIS Cut Line= 3
      1999806.22     13478311.36      1999452.07     13477127.37
      1999299.70     13476601.00
#Sta/Elev= 30
  3780.3  456.22  3939.9  452.31  4049.7  451.78  4282.2  449.09  4363.3  448.36
  4396.4  449.00  4402.8  448.41  4440.8  448.36  4567.1  447.96  4580.2  449.61
  4590.6  449.86  4622.0  448.66  4643.8  449.19  4676.9  448.73  4695.0  449.42
  4710.0  448.72  4725.1  448.94  4862.0  448.75  5009.6  447.05  5010.5  446.25
  5019.0  446.25  5019.9  447.05  5096.1  448.41  5210.9  452.17  5458.1  458.59
  5486.5  458.47  5525.3  459.03  5530.5  459.61  5558.9  459.24  5564.1  459.84
#Mann=7,-1,0
  3780.3     0.1       0  4282.2    0.16       0  4440.8     0.1       0
  4725.1    0.16       0  5009.6    0.07       0  5019.9    0.16       0
  5210.9     0.1       0
Bank Sta=5009.6,5019.9
Exp/Cntr=0.3,0.1

Chan Stop Cuts=-1