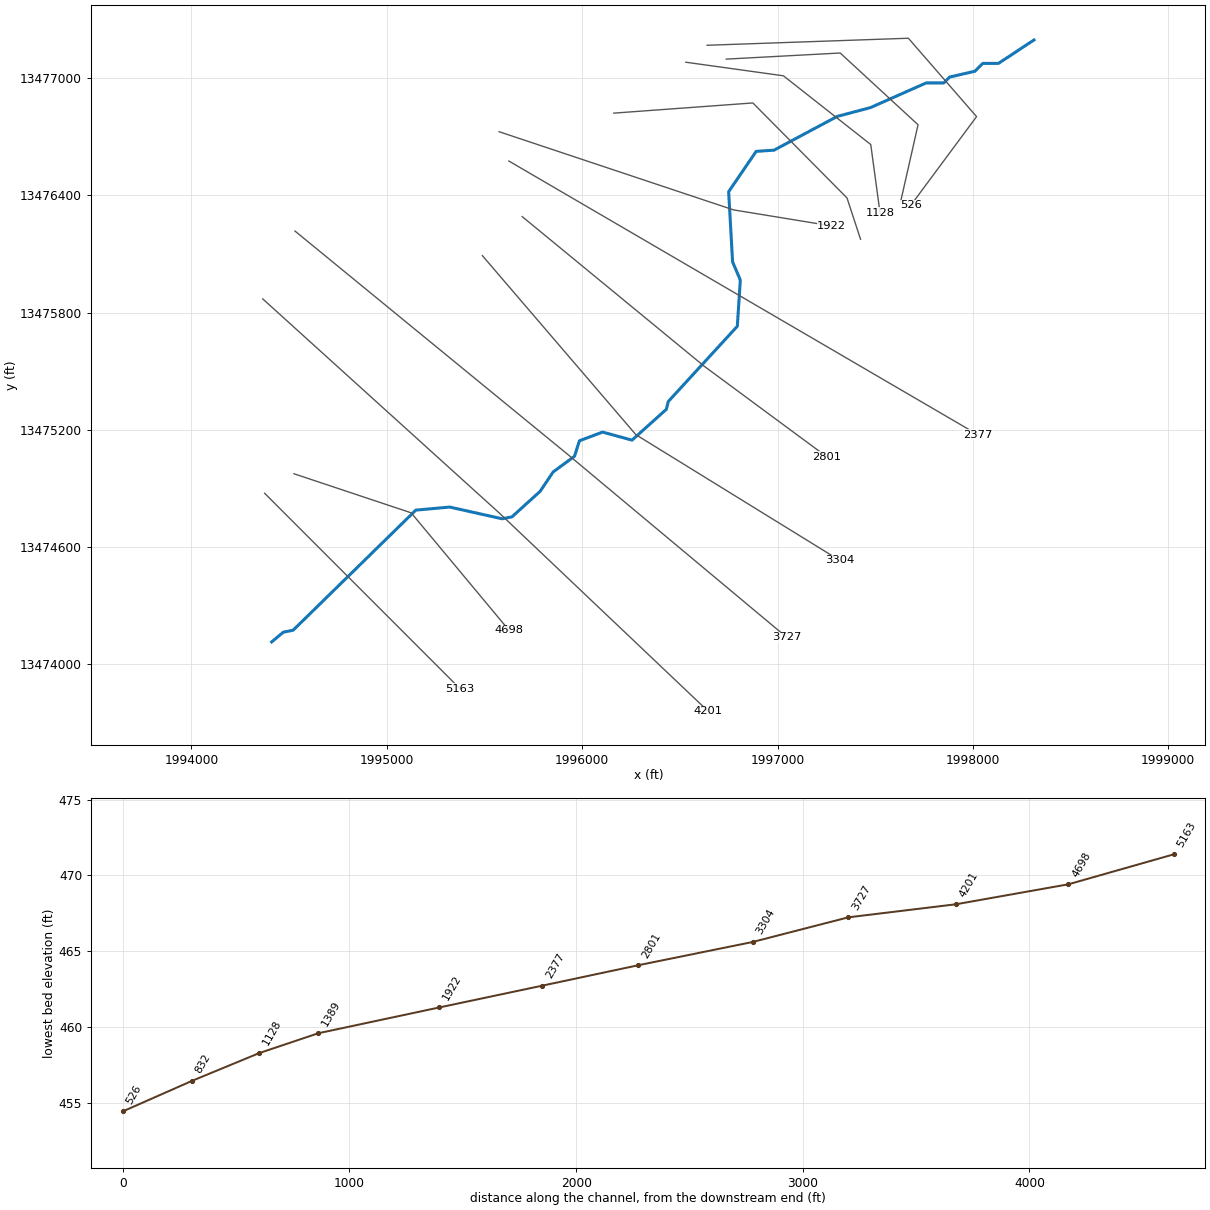
--- UNT 013 in RCW.prj (project) ---

Proj Title=UNT 013 in RCW Base Level Engineering
Current Plan=p01
Default Exp/Contr=0.3,0.1
English Units
Geom File=g01
Flow File=f01
Plan File=p01
Y Axis Title=Elevation
X Axis Title(PF)=Main Channel Distance
X Axis Title(XS)=Station
BEGIN DESCRIPTION:
UNT 013 in RCW
END DESCRIPTION:
DSS Export Rating Curves= 0
DSS Export Rating Curve Sorted= 0
DSS Export Volume Flow Curves= 0
DXF OffsetX= 0
DXF OffsetY= 0
DXF ScaleX= 1
DXF ScaleY= 10

--- UNT 013 in RCW.p01 (plan) ---

Plan Title=Multiple Run
Short Identifier=Multiple
Geom File=g01
Flow File=f01
Subcritical Flow
K Sum by GR= 0
Std Step Tol= 0.01
Critical Tol= 0.01
Num of Std Step Trials= 20
Max Error Tol= 0.3
Flow Tol Ratio= 0.001
Split Flow NTrial= 30
Split Flow Tol= 0.02
Split Flow Ratio= 0.02
Log Output Level= 0
Friction Slope Method= 1
Unsteady Friction Slope Method= 2
Unsteady Bridges Friction Slope Method= 1
Parabolic Critical Depth
Global Vel Dist=  1 , 1 , 1
Global Log Level= 0
CheckData=True
Encroach Param= -1, 0, 0, 0
BEGIN DESCRIPTION:
Multiple Run
END DESCRIPTION:

--- UNT 013 in RCW.f01 (steady flow) ---

Flow Title=Multiple
Program Version=5.05
Number of Profiles= 7
Profile Names=10-year,25-year,50-year,1pct_min,100-year,1pct_plu,500-year
River Rch & RM=UNT 013 in RCW,Reach-1         ,5163
     163     221     268     162     324     646     479
River Rch & RM=UNT 013 in RCW,Reach-1         ,2377
     197     270     329     200     398     795     595
Boundary for River Rch & Prof#=UNT 013 in RCW,Reach-1         , 1
Up Type= 0
Dn Type= 3
Dn Slope=0.005
Boundary for River Rch & Prof#=UNT 013 in RCW,Reach-1         , 2
Up Type= 0
Dn Type= 3
Dn Slope=0.005
Boundary for River Rch & Prof#=UNT 013 in RCW,Reach-1         , 3
Up Type= 0
Dn Type= 3
Dn Slope=0.005
Boundary for River Rch & Prof#=UNT 013 in RCW,Reach-1         , 4
Up Type= 0
Dn Type= 3
Dn Slope=0.005
Boundary for River Rch & Prof#=UNT 013 in RCW,Reach-1         , 5
Up Type= 0
Dn Type= 3
Dn Slope=0.005
Boundary for River Rch & Prof#=UNT 013 in RCW,Reach-1         , 6
Up Type= 0
Dn Type= 3
Dn Slope=0.005
Boundary for River Rch & Prof#=UNT 013 in RCW,Reach-1         , 7
Up Type= 0
Dn Type= 3
Dn Slope=0.005
DSS Import GetInterval= 0
DSS Import GetPeak= 0
DSS Import FillOption= 0

--- UNT 013 in RCW.g01 (geometry) ---

Geom Title=Existing Conditions

River Reach=UNT 013 in RCW,Reach-1
Reach XY= 30
      1994410.80     13474114.54      1994470.80     13474164.54
      1994520.80     13474174.54      1995148.49     13474788.79
      1995322.10     13474804.54      1995590.80     13474744.54
      1995640.80     13474754.54      1995785.30     13474885.31
      1995851.27     13474983.92      1995960.99     13475064.48
      1995985.99     13475143.65      1996104.74     13475188.09
      1996255.43     13475147.12      1996430.80     13475304.54
      1996440.80     13475344.54      1996794.32     13475729.76
      1996809.60     13475965.87      1996770.10     13476058.97
      1996749.88     13476417.95      1996890.80     13476624.54
      1996981.82     13476630.45      1997305.61     13476803.19
      1997475.75     13476848.33      1997760.80     13476974.54
      1997850.80     13476974.54      1997880.80     13477004.54
      1998010.80     13477034.54      1998050.80     13477074.54
      1998130.80     13477074.54      1998312.56     13477194.25

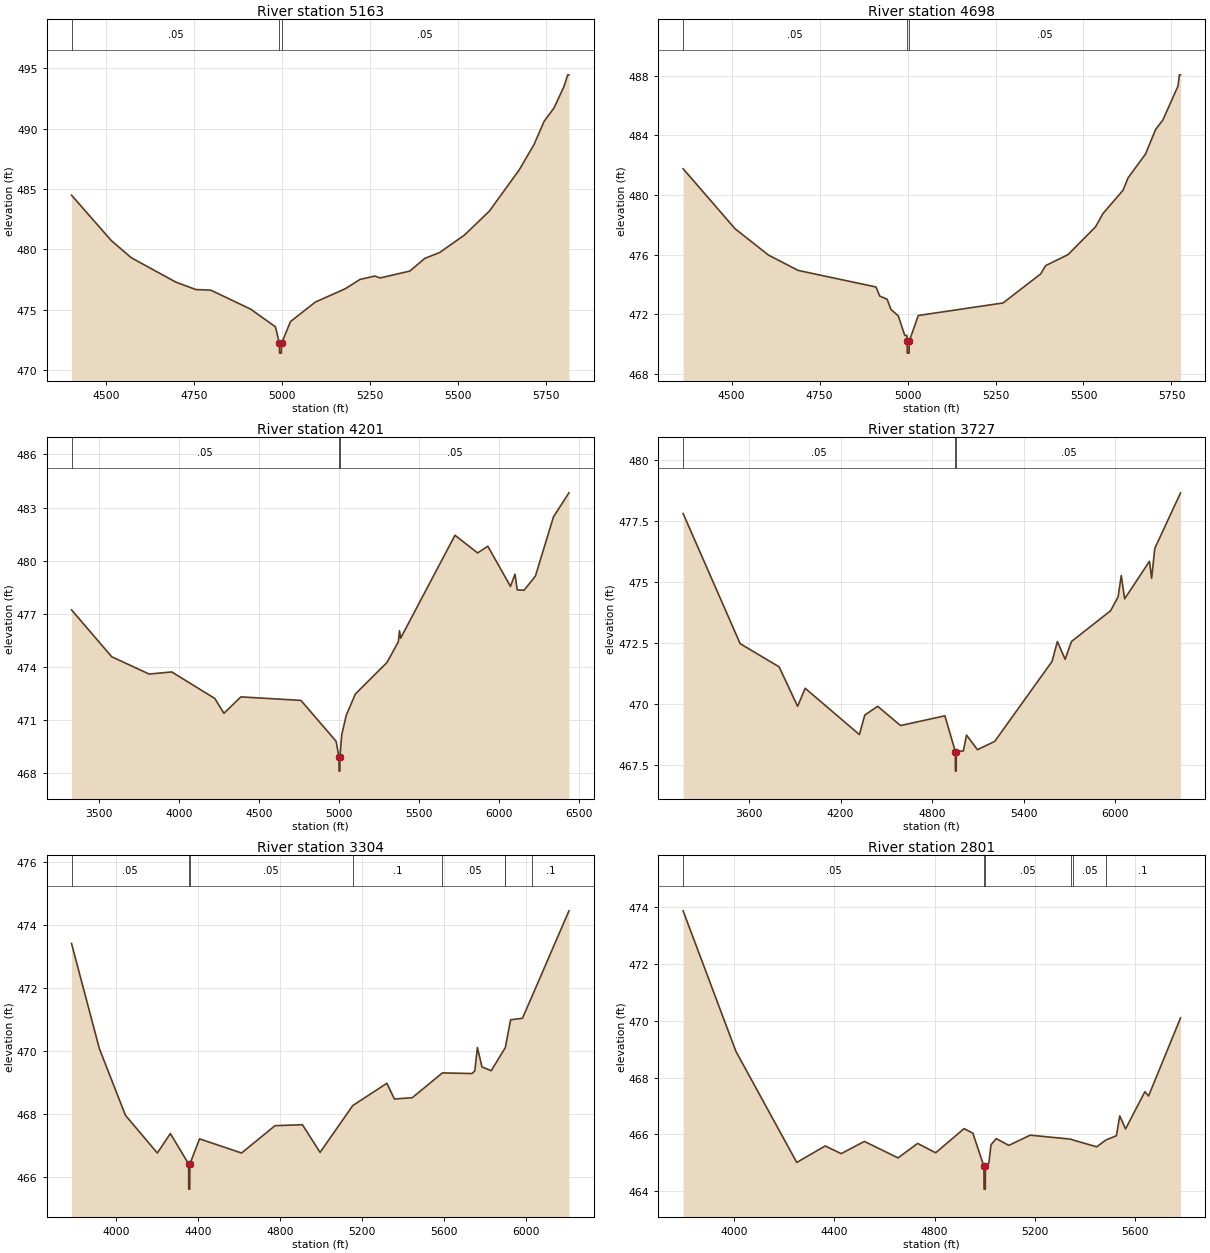
Type RM Length L Ch R = 1,5163,465,465,465
BEGIN DESCRIPTION:
UNT 013 in RCW 9.0
END DESCRIPTION:
XS GIS Cut Line= 3
      1994375.00     13474875.00      1994775.00     13474475.00
      1995374.99     13473875.01
#Sta/Elev= 30
  4401.6  484.48  4514.7  480.72  4571.3  479.30  4698.6  477.27  4755.2  476.66
  4797.6  476.61  4910.7  475.04  4981.4  473.57  4992.6  472.19  4993.1  471.39
  4998.1  471.39  4998.6  472.19  5023.9  474.00  5094.6  475.62  5179.4  476.72
  5221.8  477.50  5264.3  477.78  5278.4  477.62  5363.3  478.19  5405.7  479.24
  5448.1  479.73  5518.8  481.18  5589.5  483.16  5674.4  486.58  5716.8  488.70
  5745.1  490.60  5773.4  491.72  5801.7  493.49  5812.3  494.46  5815.8  494.46
#Mann=3,-1,0
  4401.6    0.05       0  4992.6    0.03       0  4998.6    0.05       0
Bank Sta=4992.6,4998.6
Exp/Cntr=0.3,0.1

Type RM Length L Ch R = 1,4698,497,497,497
BEGIN DESCRIPTION:
UNT 013 in RCW 8.0
END DESCRIPTION:
XS GIS Cut Line= 3
      1994525.01     13474975.00      1995125.00     13474775.00
      1995625.02     13474174.97
#Sta/Elev= 30
  4362.3  481.76  4509.9  477.74  4604.7  475.98  4689.1  474.95  4910.4  473.84
  4921.0  473.23  4942.0  473.02  4952.6  472.35  4973.7  471.90  4992.1  470.60
  4998.0  470.60  4998.9  470.21  4999.4  469.41  5004.4  469.41  5004.9  470.21
  5030.5  471.93  5271.4  472.77  5378.1  474.71  5392.4  475.27  5456.2  476.01
  5534.3  477.87  5555.1  478.75  5612.4  480.32  5626.7  481.15  5676.2  482.74
  5704.8  484.38  5725.7  485.03  5768.6  487.30  5772.5  488.05  5775.8  488.05
#Mann=3,-1,0
  4362.3    0.05       0  4998.9    0.03       0  5004.9    0.05       0
Bank Sta=4998.9,5004.9
Exp/Cntr=0.3,0.1

Type RM Length L Ch R = 1,4201,474,474,474
BEGIN DESCRIPTION:
UNT 013 in RCW 7.0
END DESCRIPTION:
XS GIS Cut Line= 3
      1994365.27     13475869.55      1995575.00     13474775.00
      1996645.71     13473759.20
#Sta/Elev= 30
  3328.8  477.21  3579.7  474.56  3813.6  473.58  3954.8  473.70  4223.8  472.20
  4280.6  471.36  4386.7  472.29  4761.8  472.09  4981.4  469.78  4999.5  468.89
  5000.0  468.09  5005.0  468.09  5005.5  468.89  5016.6  470.14  5045.0  471.25
  5101.6  472.45  5299.8  474.24  5370.6  475.41  5377.5  476.03  5384.7  475.61
  5724.1  481.43  5865.7  480.43  5929.2  480.81  6070.8  478.54  6099.1  479.23
  6113.2  478.34  6155.7  478.32  6226.5  479.12  6339.4  482.47  6436.1  483.83
#Mann=3,-1,0
  3328.8    0.05       0  4999.5    0.03       0  5005.5    0.05       0
Bank Sta=4999.5,5005.5
Exp/Cntr=0.3,0.1

Type RM Length L Ch R = 1,3727,423,423,423
BEGIN DESCRIPTION:
UNT 013 in RCW 6.0
END DESCRIPTION:
XS GIS Cut Line= 3
      1994530.17     13476216.80      1995925.00     13475075.00
      1997046.23     13474138.89
#Sta/Elev= 30
  3167.0  477.80  3541.2  472.46  3796.7  471.51  3918.0  469.89  3967.6  470.63
  4323.4  468.73  4358.7  469.53  4443.4  469.89  4593.4  469.10  4884.2  469.50
  4952.9  468.03  4953.4  467.23  4958.4  467.23  4958.9  468.03  5005.4  468.06
  5026.2  468.71  5097.8  468.11  5211.0  468.45  5587.1  471.73  5622.3  472.55
  5673.0  471.82  5714.7  472.55  5971.1  473.81  6020.5  474.38  6041.3  475.26
  6063.5  474.30  6226.2  475.84  6240.5  475.14  6261.3  476.37  6430.2  478.65
#Mann=3,-1,0
  3167.0    0.05       0  4952.9    0.03       0  4958.9    0.05       0
Bank Sta=4952.9,4958.9
Exp/Cntr=0.3,0.1

Type RM Length L Ch R = 1,3304,503,503,503
BEGIN DESCRIPTION:
UNT 013 in RCW 5.0
END DESCRIPTION:
XS GIS Cut Line= 3
      1995489.39     13476090.92      1996275.00     13475175.00
      1997316.64     13474532.76
#Sta/Elev= 30
  3781.5  473.42  3917.6  470.07  4044.9  467.95  4200.7  466.75  4264.4  467.37
  4353.6  466.40  4354.1  465.60  4359.1  465.60  4359.6  466.40  4407.1  467.20
  4612.3  466.75  4775.8  467.62  4909.7  467.65  4995.9  466.77  5155.5  468.26
  5322.3  468.97  5359.0  468.47  5446.4  468.51  5593.4  469.30  5737.5  469.28
  5751.8  469.36  5764.6  470.11  5787.0  469.49  5832.1  469.37  5900.5  470.10
  5901.5  470.12  5926.7  470.99  5984.7  471.04  6030.9  471.73  6211.9  474.46
#Mann=8,-1,0
  3781.5    0.05       0  4353.6    0.03       0  4359.6    0.05       0
  5155.5     0.1       0  5593.4    0.05       0  5900.5     0.1       0
  5901.5    0.05       0  6030.9     0.1       0
Bank Sta=4353.6,4359.6
Exp/Cntr=0.3,0.1

Type RM Length L Ch R = 1,2801,424,424,424
BEGIN DESCRIPTION:
UNT 013 in RCW 4.0
END DESCRIPTION:
XS GIS Cut Line= 3
      1995693.39     13476290.56      1996625.00     13475525.00
      1997250.74     13475062.87
#Sta/Elev= 30
  3797.3  473.87  4007.9  468.92  4250.4  465.01  4363.8  465.59  4427.7  465.32
  4520.2  465.75  4654.4  465.17  4732.6  465.68  4804.4  465.35  4917.7  466.20
  4952.9  466.04  4996.9  464.87  4997.4  464.07  5002.4  464.07  5002.9  464.87
  5016.6  464.99  5025.1  465.63  5045.9  465.85  5096.0  465.61  5181.6  465.97
  5343.4  465.83  5352.2  465.80  5446.8  465.56  5483.2  465.80  5525.2  465.95
  5538.6  466.65  5561.7  466.19  5638.8  467.50  5653.5  467.35  5781.0  470.10
#Mann=6,-1,0
  3797.3    0.05       0  4996.9   0.035       0  5002.9    0.05       0
  5343.4     0.1       0  5352.2    0.05       0  5483.2     0.1       0
Bank Sta=4996.9,5002.9
Exp/Cntr=0.3,0.1

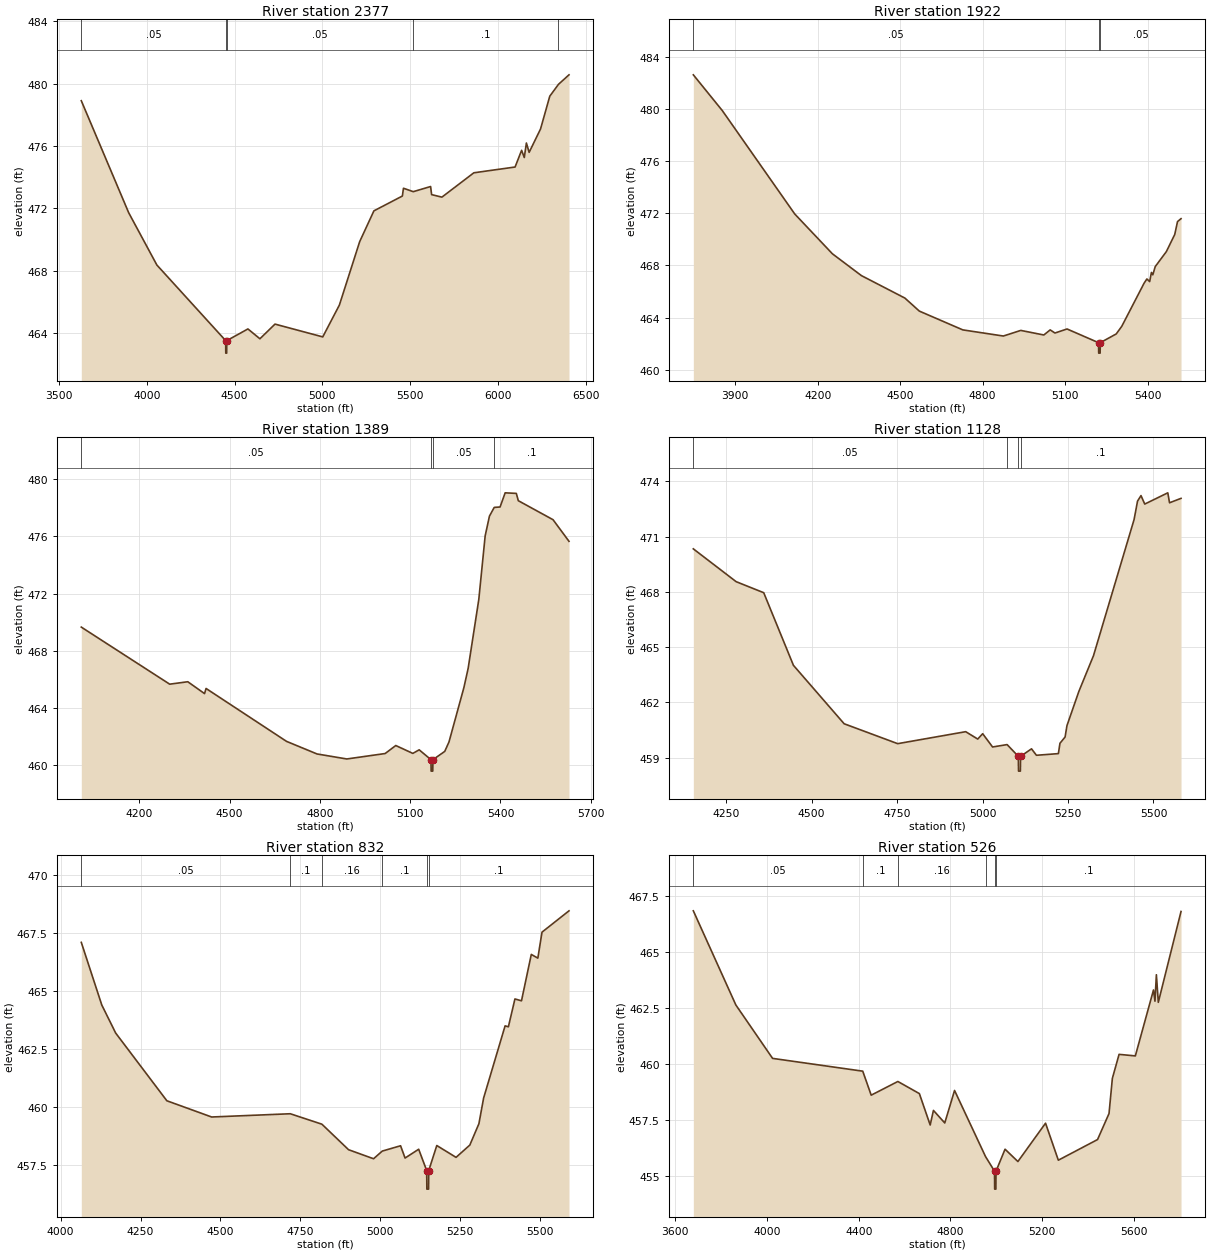
Type RM Length L Ch R = 1,2377,455,455,455
BEGIN DESCRIPTION:
UNT 013 in RCW 3.0
END DESCRIPTION:
XS GIS Cut Line= 3
      1995624.97     13476575.02      1996825.00     13475875.00
      1998024.98     13475175.01
#Sta/Elev= 30
  3626.7  478.90  3896.7  471.72  4057.1  468.37  4449.3  463.52  4449.8  462.72
  4455.0  462.72  4455.5  463.52  4576.0  464.27  4644.3  463.64  4730.3  464.58
  5002.3  463.76  5097.0  465.80  5212.8  469.87  5293.8  471.84  5455.9  472.79
  5462.1  473.29  5518.0  473.07  5616.7  473.40  5622.5  472.88  5681.2  472.72
  5863.2  474.28  6098.0  474.65  6135.2  475.72  6150.5  475.26  6162.5  476.19
  6178.2  475.59  6243.1  477.09  6295.7  479.19  6345.2  479.95  6405.2  480.56
#Mann=5,-1,0
  3626.7    0.05       0  4449.3   0.035       0  4455.5    0.05       0
  5518.0     0.1       0  6345.2    0.05       0
Bank Sta=4449.3,4455.5
Exp/Cntr=0.3,0.1

Type RM Length L Ch R = 1,1922,533,533,533
BEGIN DESCRIPTION:
UNT 013 in RCW 2.0
END DESCRIPTION:
XS GIS Cut Line= 3
      1995575.05     13476724.98      1996775.00     13476325.00
      1997277.56     13476242.83
#Sta/Elev= 30
  3747.7  482.60  3853.1  479.86  4116.6  471.94  4253.6  468.89  4359.0  467.22
  4517.1  465.50  4569.8  464.50  4728.0  463.06  4875.5  462.59  4938.8  463.02
  5022.7  462.67  5045.8  463.06  5063.2  462.82  5107.2  463.13  5221.8  462.08
  5222.3  461.28  5227.5  461.28  5228.0  462.08  5286.1  462.75  5306.4  463.34
  5387.5  466.64  5397.6  466.96  5407.7  466.76  5414.1  467.46  5419.2  467.28
  5428.0  467.91  5468.5  469.06  5498.9  470.37  5509.1  471.36  5521.8  471.58
#Mann=3,-1,0
  3747.7    0.05       0  5221.8   0.035       0  5228.0    0.05       0
Bank Sta=5221.8,5228
Exp/Cntr=0.3,0.1

Type RM Length L Ch R = 1,1389,261,261,261
BEGIN DESCRIPTION:
UNT 013 in RCW 1.0
END DESCRIPTION:
XS GIS Cut Line= 4
      1996162.11     13476820.08      1996873.94     13476872.16
      1997355.71     13476386.05      1997425.01     13476174.98
#Sta/Elev= 30
  4007.4  469.65  4301.1  465.66  4361.2  465.83  4416.9  465.00  4421.9  465.36
  4689.3  461.66  4790.6  460.78  4889.6  460.43  5016.9  460.81  5052.2  461.37
  5108.8  460.82  5130.0  461.07  5169.2  460.38  5169.7  459.58  5175.1  459.58
  5175.6  460.38  5214.9  460.96  5229.0  461.62  5278.5  465.42  5292.7  466.77
  5328.0  471.58  5349.2  476.03  5363.4  477.41  5379.3  478.02  5398.7  478.05
  5415.6  479.04  5452.7  479.00  5459.3  478.49  5574.7  477.16  5627.7  475.65
#Mann=4,-1,0
  4007.4    0.05       0  5169.2   0.035       0  5175.6    0.05       0
  5379.3     0.1       0
Bank Sta=5169.2,5175.6
Exp/Cntr=0.3,0.1

Type RM Length L Ch R = 1,1128,296,296,296
BEGIN DESCRIPTION:
Mapping XS a33432bf
END DESCRIPTION:
XS GIS Cut Line= 4
      1996531.04     13477080.50      1997030.19     13477011.05
      1997477.24     13476659.49      1997524.84     13476308.99
#Sta/Elev= 30
  4154.2  470.33  4279.4  468.55  4360.1  467.95  4447.0  464.01  4595.3  460.84
  4751.9  459.76  4950.8  460.41  4986.0  460.01  5000.5  460.30  5029.4  459.58
  5071.9  459.71  5104.8  459.07  5105.3  458.27  5110.7  458.27  5111.2  459.07
  5143.3  459.48  5157.7  459.13  5221.9  459.22  5226.5  459.78  5241.5  460.12
  5247.0  460.74  5281.9  462.60  5324.5  464.53  5443.3  471.92  5453.4  472.92
  5463.5  473.22  5474.5  472.76  5541.9  473.37  5547.0  472.83  5580.6  473.07
#Mann=4,-1,0
  4154.2    0.05       0  5071.9     0.1       0  5104.8   0.035       0
  5111.2     0.1       0
Bank Sta=5104.8,5111.2
Exp/Cntr=0.3,0.1

Type RM Length L Ch R = 1,832,306,306,306
BEGIN DESCRIPTION:
Mapping XS 042298fc
END DESCRIPTION:
XS GIS Cut Line= 4
      1996737.57     13477096.48      1997320.90     13477127.73
      1997719.34     13476760.54      1997630.80     13476369.95
#Sta/Elev= 30
  4064.7  467.08  4128.8  464.38  4172.3  463.17  4332.5  460.25  4472.7  459.55
  4718.8  459.69  4817.8  459.24  4901.2  458.14  4979.5  457.75  5006.7  458.08
  5064.0  458.31  5078.1  457.78  5120.7  458.16  5145.8  457.24  5146.3  456.44
  5151.7  456.44  5152.2  457.24  5177.4  458.32  5237.7  457.81  5280.8  458.34
  5309.2  459.26  5324.0  460.37  5391.2  463.48  5401.5  463.44  5422.0  464.64
  5442.5  464.56  5473.2  466.56  5493.7  466.40  5506.7  467.52  5591.2  468.44
#Mann=6,-1,0
  4064.7    0.05       0  4718.8     0.1       0  4817.8    0.16       0
  5006.7     0.1       0  5145.8    0.07       0  5152.2     0.1       0
Bank Sta=5145.8,5152.2
Exp/Cntr=0.3,0.1

Type RM Length L Ch R = 1,526,0,0,0
BEGIN DESCRIPTION:
Mapping XS a33432fd
END DESCRIPTION:
XS GIS Cut Line= 4
      1996639.55     13477167.30      1997669.86     13477203.25
      1998018.82     13476802.21      1997682.35     13476348.49
#Sta/Elev= 30
  3678.7  466.83  3864.3  462.63  4024.4  460.25  4417.7  459.68  4454.6  458.61
  4570.9  459.22  4664.7  458.68  4711.9  457.28  4726.1  457.93  4775.5  457.37
  4818.2  458.82  4953.4  455.87  4992.6  455.22  4993.1  454.42  4998.5  454.42
  4999.0  455.22  5038.5  456.20  5094.5  455.65  5215.1  457.36  5270.9  455.71
  5441.9  456.63  5492.0  457.79  5506.6  459.36  5535.9  460.43  5606.8  460.36
  5686.0  463.30  5692.4  462.80  5698.6  463.98  5707.0  462.75  5806.1  466.80
#Mann=6,-1,0
  3678.7    0.05       0  4417.7     0.1       0  4570.9    0.16       0
  4953.4     0.1       0  4992.6    0.07       0  4999.0     0.1       0
Bank Sta=4992.6,4999
Exp/Cntr=0.3,0.1

Chan Stop Cuts=-1