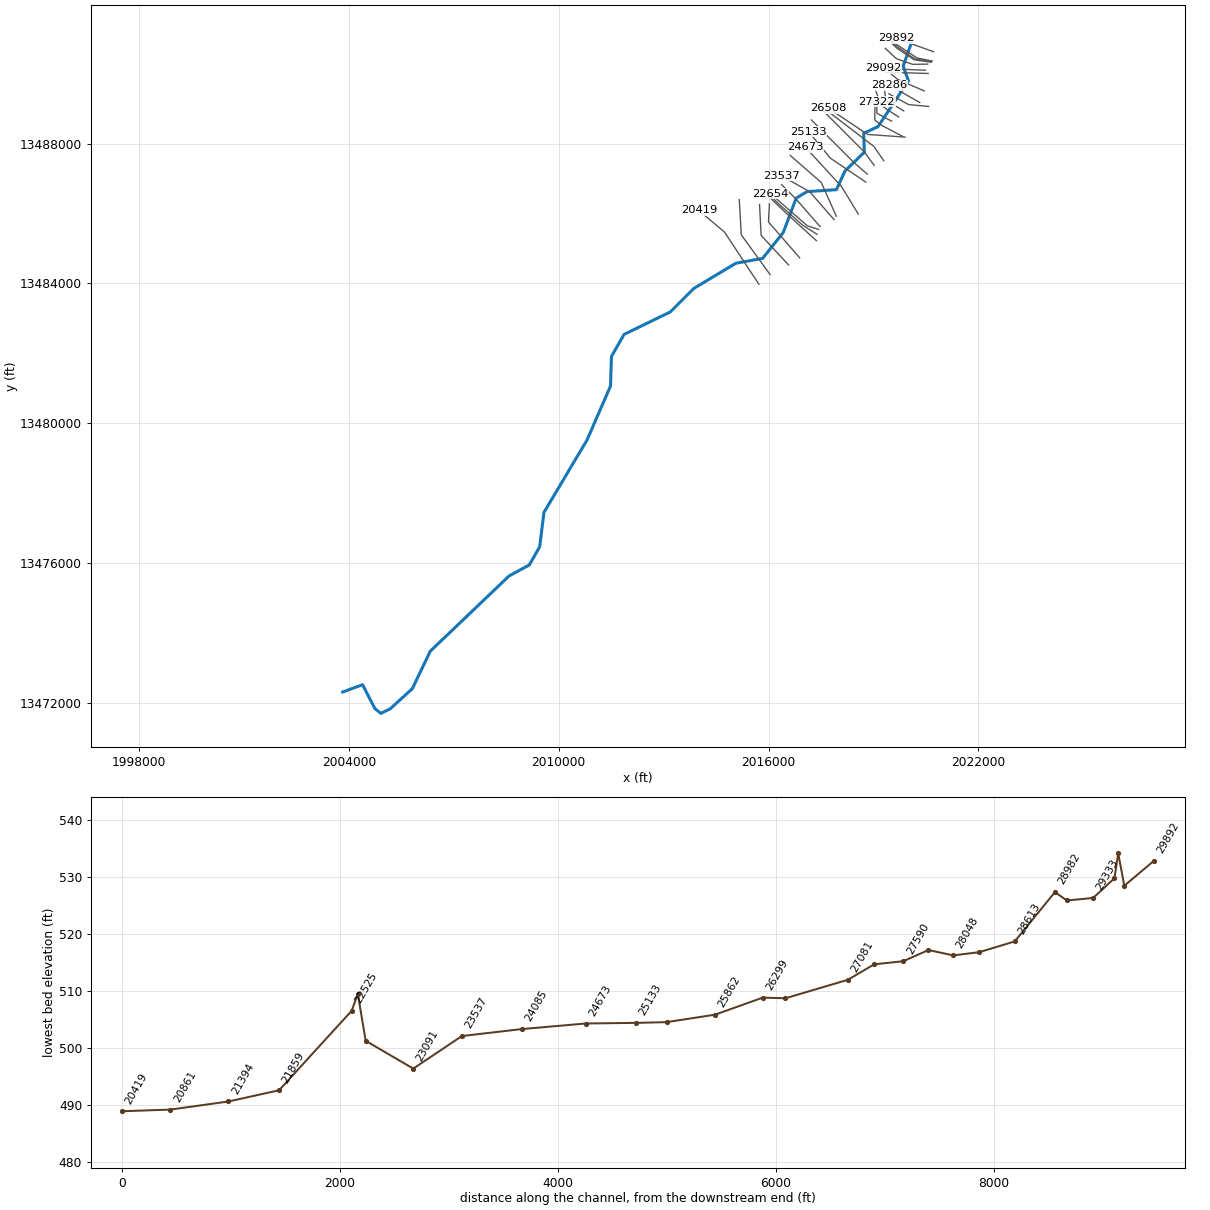
--- UNT 015 in RCW.prj (project) ---

Proj Title=UNT 015 in RCW Base Level Engineering
Current Plan=p01
Default Exp/Contr=0.3,0.1
English Units
Geom File=g01
Flow File=f01
Plan File=p01
Y Axis Title=Elevation
X Axis Title(PF)=Main Channel Distance
X Axis Title(XS)=Station
BEGIN DESCRIPTION:
UNT 015 in RCW
END DESCRIPTION:
DSS Export Rating Curves= 0
DSS Export Rating Curve Sorted= 0
DSS Export Volume Flow Curves= 0
DXF OffsetX= 0
DXF OffsetY= 0
DXF ScaleX= 1
DXF ScaleY= 10

--- UNT 015 in RCW.p01 (plan) ---

Plan Title=Multiple Run
Short Identifier=Multiple
Geom File=g01
Flow File=f01
Subcritical Flow
K Sum by GR= 0
Std Step Tol= 0.01
Critical Tol= 0.01
Num of Std Step Trials= 20
Max Error Tol= 0.3
Flow Tol Ratio= 0.001
Split Flow NTrial= 30
Split Flow Tol= 0.02
Split Flow Ratio= 0.02
Log Output Level= 0
Friction Slope Method= 1
Unsteady Friction Slope Method= 2
Unsteady Bridges Friction Slope Method= 1
Parabolic Critical Depth
Global Vel Dist=  1 , 1 , 1
Global Log Level= 0
CheckData=True
Encroach Param= -1, 0, 0, 0
BEGIN DESCRIPTION:
Multiple Run
END DESCRIPTION:

--- UNT 015 in RCW.f01 (steady flow) ---

Flow Title=Multiple
Program Version=5.05
Number of Profiles= 7
Profile Names=10-year,25-year,50-year,1pct_min,100-year,1pct_plu,500-year
River Rch & RM=UNT 015 in RCW,Reach-1         ,29892
     176     240     291     177     352     703     523
River Rch & RM=UNT 015 in RCW,Reach-1         ,29619
     207     284     347     211     422     841     632
River Rch & RM=UNT 015 in RCW,Reach-1         ,26508
     412     585     732     455     908    1812    1423
River Rch & RM=UNT 015 in RCW,Reach-1         ,23091
     437     620     775     482     963    1920    1507
River Rch & RM=UNT 015 in RCW,Reach-1         ,19937
     524     750     943     590    1177    2348    1862
River Rch & RM=UNT 015 in RCW,Reach-1         ,16228
     569     816    1027     643    1283    2559    2032
River Rch & RM=UNT 015 in RCW,Reach-1         ,14015
     662     950    1197     749    1495    2982    2367
River Rch & RM=UNT 015 in RCW,Reach-1         ,8260
     803    1161    1468     922    1840    3671    2935
River Rch & RM=UNT 015 in RCW,Reach-1         ,5579
     803    1161    1468     922    1840    3671    2935
River Rch & RM=UNT 015 in RCW,Reach-1         ,4619
     803    1161    1468     922    1840    3671    2935
Boundary for River Rch & Prof#=UNT 015 in RCW,Reach-1         , 1
Up Type= 0
Dn Type= 3
Dn Slope=0.01533
Boundary for River Rch & Prof#=UNT 015 in RCW,Reach-1         , 2
Up Type= 0
Dn Type= 3
Dn Slope=0.01533
Boundary for River Rch & Prof#=UNT 015 in RCW,Reach-1         , 3
Up Type= 0
Dn Type= 3
Dn Slope=0.01533
Boundary for River Rch & Prof#=UNT 015 in RCW,Reach-1         , 4
Up Type= 0
Dn Type= 3
Dn Slope=0.01533
Boundary for River Rch & Prof#=UNT 015 in RCW,Reach-1         , 5
Up Type= 0
Dn Type= 3
Dn Slope=0.01533
Boundary for River Rch & Prof#=UNT 015 in RCW,Reach-1         , 6
Up Type= 0
Dn Type= 3
Dn Slope=0.01533
Boundary for River Rch & Prof#=UNT 015 in RCW,Reach-1         , 7
Up Type= 0
Dn Type= 3
Dn Slope=0.01533
DSS Import GetInterval= 0
DSS Import GetPeak= 0
DSS Import FillOption= 0

--- UNT 015 in RCW.g01 (geometry) ---

Geom Title=Existing Conditions
Program Version=5.05

River Reach=UNT 015 in RCW  ,Reach-1
Reach XY= 30
      2020114.82     13490966.53       2019850.8     13490214.54
       2020000.8     13489794.54       2019130.8     13488484.54
       2018720.8     13488294.54       2018740.8     13487754.54
      2018186.48     13487215.79      2017942.73     13486681.06
      2017100.61     13486626.11      2016790.26     13486438.64
       2016420.8     13485454.54      2015829.27     13484714.86
      2015070.18      13484579.2       2013860.8     13483854.54
       2013190.8     13483184.54       2011870.1     13482542.54
      2011508.12     13481912.33       2011480.8     13481064.54
       2010810.8     13479524.54      2009576.95     13477450.68
      2009456.74     13476471.58      2009159.35     13475949.01
       2008580.8     13475634.54      2006327.63     13473484.12
      2005813.74      13472410.5       2005180.8     13471834.54
       2004910.8     13471704.54       2004740.8     13471844.54
       2004390.8     13472524.54      2003822.11     13472315.22

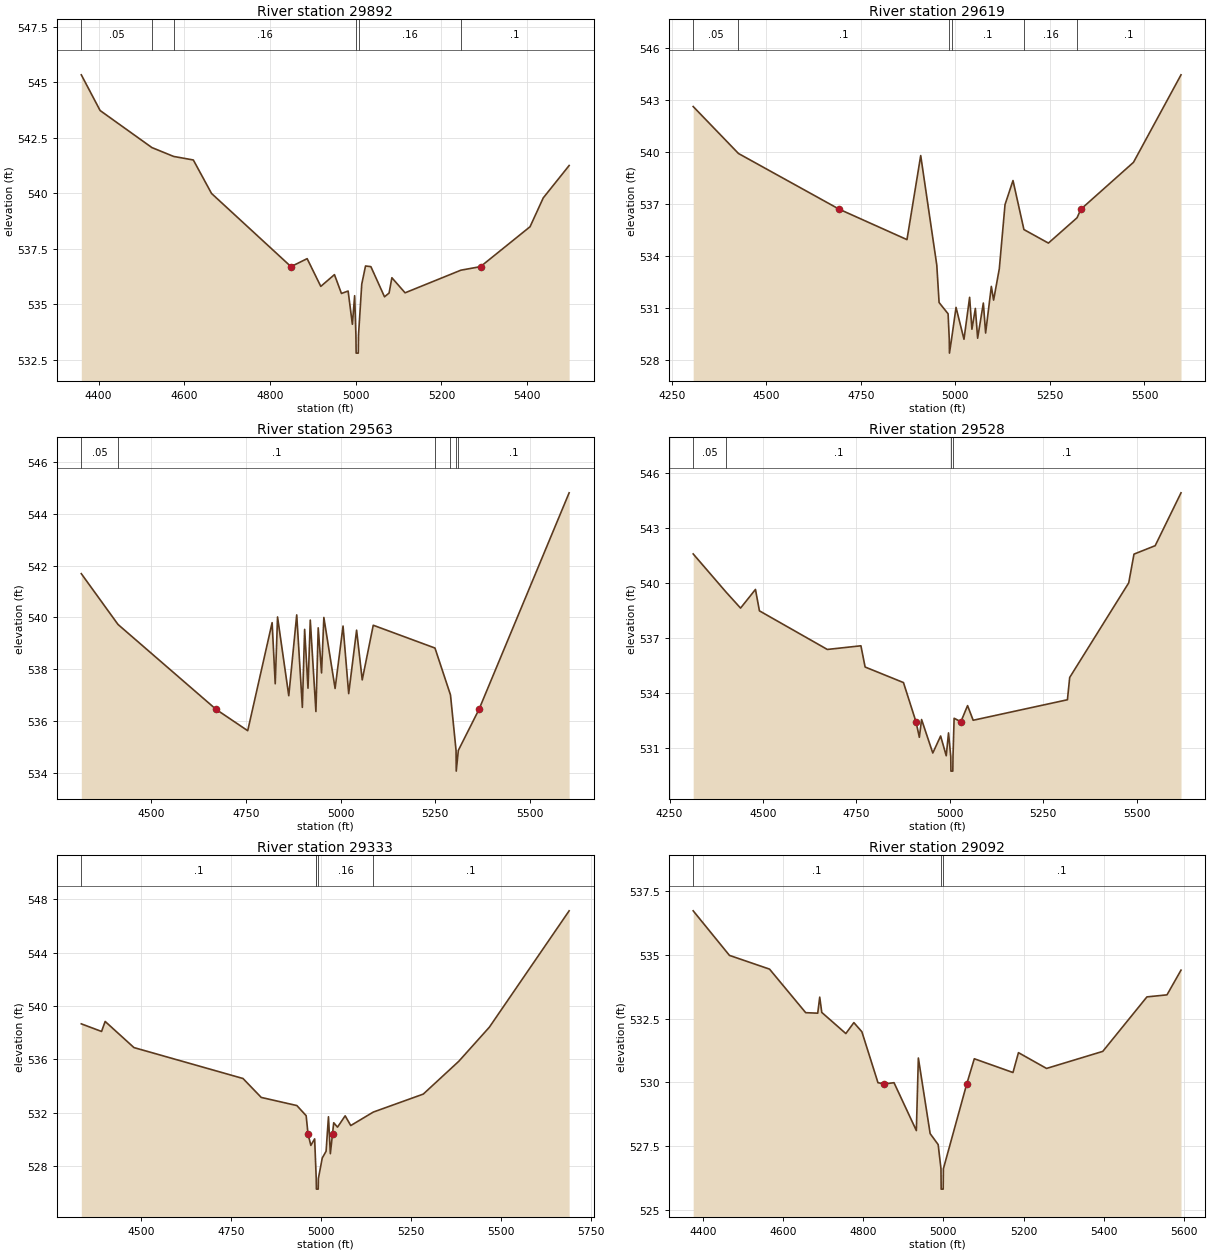
Type RM Length L Ch R = 1 ,29892   ,273,273,273
BEGIN DESCRIPTION:
Mapping XS 93bff3e4
END DESCRIPTION:
XS GIS Cut Line= 2
      2020721.07     13490625.13      2019649.48     13491009.08
#Sta/Elev= 30
  4359.7  545.34  4403.6  543.73  4524.4  542.06  4575.1  541.66  4621.1   541.5
  4663.6  539.99 4848.98536.6904  4886.7  537.05  4918.5   535.8  4950.4  536.33
  4966.7  535.48  4982.3  535.59  4992.2  534.09  4997.5  535.38  5000.5  533.59
    5001  532.79    5006  532.79  5006.5  533.59  5014.1   535.9  5022.9  536.72
  5035.4  536.69  5067.2  535.33  5077.9   535.5  5084.4  536.19  5115.2  535.51
  5245.4  536.53 5291.23536.6903  5406.8  538.49  5437.6  539.79    5498  541.25
#Mann= 6 ,-1 , 0
  4359.7     .05       0  4524.4      .1       0  4575.1     .16       0
  5000.5     .07       0  5006.5     .16       0  5245.4      .1       0
Bank Sta=4848.98,5291.23
XS Rating Curve= 0 ,0
Exp/Cntr=0.3,0.1

Type RM Length L Ch R = 1 ,29619   ,56,56,56
BEGIN DESCRIPTION:
UNT 015 in RCW 60.0
END DESCRIPTION:
XS GIS Cut Line= 4
      2020680.92     13490360.38      2020242.52     13490449.36
      2020005.97     13490609.95      2019539.66      13490913.6
#Sta/Elev= 30
  4306.9  542.63  4426.6  539.92 4692.92536.7049  4872.1  534.95  4908.4   539.8
  4950.9  533.48    4957  531.32  4980.8  530.67  4983.9   529.2  4984.4   528.4
  4989.9   529.2  5001.8  531.04  5022.8   529.2  5037.7  531.62  5043.8  529.78
  5052.9  530.98  5058.9  529.26    5074  531.29    5080  529.56  5095.1  532.25
  5101.1  531.46  5116.2  533.27  5131.3  536.97  5152.4  538.36  5181.3  535.53
    5246  534.75  5321.7  536.21 5331.86 536.705  5470.9  539.41  5596.6  544.46
#Mann= 6 ,-1 , 0
  4306.9     .05       0  4426.6      .1       0  4983.9     .07       0
  4989.9      .1       0  5181.3     .16       0  5321.7      .1       0
Bank Sta=4692.92,5331.86
XS Rating Curve= 0 ,0
Exp/Cntr=0.3,0.1

Type RM Length L Ch R = 1 ,29563   ,35,35,35
BEGIN DESCRIPTION:
Mapping XS 7a5c6e4c
END DESCRIPTION:
XS GIS Cut Line= 4
      2020659.14      13490345.2      2020183.92     13490421.15
      2019730.37     13490733.65      2019529.29     13490893.64
#Sta/Elev= 30
  4315.1  541.69  4412.1  539.73 4671.53  536.45  4754.8  535.63  4819.3   539.8
  4827.5  537.44  4833.6  540.02  4863.3  536.98  4884.3   540.1  4899.2  536.53
  4905.2  539.54  4914.1  537.27  4920.1   539.9    4935  536.37  4941.1   539.6
  4949.9  537.86    4956     540  4985.7  537.26  5006.7  539.67  5021.6  537.06
  5042.5  539.51  5057.4  537.59  5086.5   539.7  5249.6  538.82  5290.6  537.01
  5305.3  534.87  5305.8  534.07  5311.3  534.87 5365.84536.4499  5604.1  544.81
#Mann= 6 ,-1 , 0
  4315.1     .05       0  4412.1      .1       0  5249.6     .16       0
  5290.6      .1       0  5305.3     .07       0  5311.3      .1       0
Bank Sta=4671.53,5365.84
XS Rating Curve= 0 ,0
Exp/Cntr=0.3,0.1

Type RM Length L Ch R = 1 ,29528   ,195,195,195
BEGIN DESCRIPTION:
Mapping XS 6d384faa
END DESCRIPTION:
XS GIS Cut Line= 4
       2020650.5     13490325.67      2020166.56     13490395.11
      2019676.11      13490722.8      2019511.21     13490879.02
#Sta/Elev= 30
  4313.1  541.58  4401.3  539.49  4439.9  538.62  4479.8  539.64  4490.4  538.47
  4672.2  536.36  4762.1  536.56  4773.3   535.4    4876  534.55 4909.53532.4077
  4918.5  531.56  4924.5  532.53  4954.5   530.7  4975.5  531.63  4990.5  530.55
  4996.6   531.8  5002.6  530.51  5003.1  529.71  5008.1  529.71  5008.6  530.51
  5011.6   532.6 5029.62532.4072  5047.6  533.29  5062.6  532.49  5314.9  533.61
    5321  534.83    5479     540  5493.1  541.57  5549.8  542.03    5619  544.92
#Mann= 4 ,-1 , 0
  4313.1     .05       0  4401.3      .1       0  5002.6     .07       0
  5008.6      .1       0
Bank Sta=4909.53,5029.62
XS Rating Curve= 0 ,0
Exp/Cntr=0.3,0.1

Type RM Length L Ch R = 1 ,29333   ,241,241,241
BEGIN DESCRIPTION:
Mapping XS 92f80a77
END DESCRIPTION:
XS GIS Cut Line= 4
      2020551.25     13490271.75      2020119.38     13490265.24
      2019654.97       13490428.      2019339.03      13490722.3
#Sta/Elev= 30
  4334.5  538.66  4390.8  538.09  4400.8  538.84  4480.8  536.88  4783.9  534.56
  4834.6  533.14  4933.6  532.53  4959.4  531.77  4964.6530.4063  4972.4  529.54
    4983  530.03  4987.3  527.13  4987.4  527.06  4987.9  526.26  4992.9  526.26
  4993.4  527.06  5004.2   528.6  5014.8   529.1  5021.4  531.69  5026.7  528.92
 5032.66530.4068    5036  531.24  5046.6  530.91  5067.8  531.76  5083.4  531.03
  5145.9  532.04  5284.9  533.39  5383.6  535.85  5468.6  538.41  5690.3  547.14
#Mann= 5 ,-1 , 0
  4334.5      .1       0  4987.3     .16       0  4987.4     .07       0
  4993.4     .16       0  5145.9      .1       0
Bank Sta=4964.6,5032.66
XS Rating Curve= 0 ,0
Exp/Cntr=0.3,0.1

Type RM Length L Ch R = 1 ,29092   ,110,110,110
BEGIN DESCRIPTION:
Mapping XS ce264a80
END DESCRIPTION:
XS GIS Cut Line= 2
      2020485.29     13490096.94      2019270.03     13490147.29
#Sta/Elev= 30
  4376.2  536.74  4466.6  534.99  4566.6  534.45  4656.7  532.74  4686.7  532.72
  4691.7  533.35  4696.8  532.75  4756.8  531.92  4776.8  532.35  4796.8  531.99
  4836.9  529.99 4852.41529.9418  4876.9  529.99  4932.6  528.11  4937.6  530.96
    4967  527.99    4987  527.56    4994  526.61  4994.5  525.81  4999.5  525.81
    5000  526.61 5058.26529.9419  5077.1  530.93  5173.5  530.39  5187.2  531.17
  5257.2  530.55  5397.4  531.22  5507.5  533.36  5557.5  533.44  5592.5  534.41
#Mann= 3 ,-1 , 0
  4376.2      .1       0    4994     .07       0    5000      .1       0
Bank Sta=4852.41,5058.26
XS Rating Curve= 0 ,0
Exp/Cntr=0.3,0.1

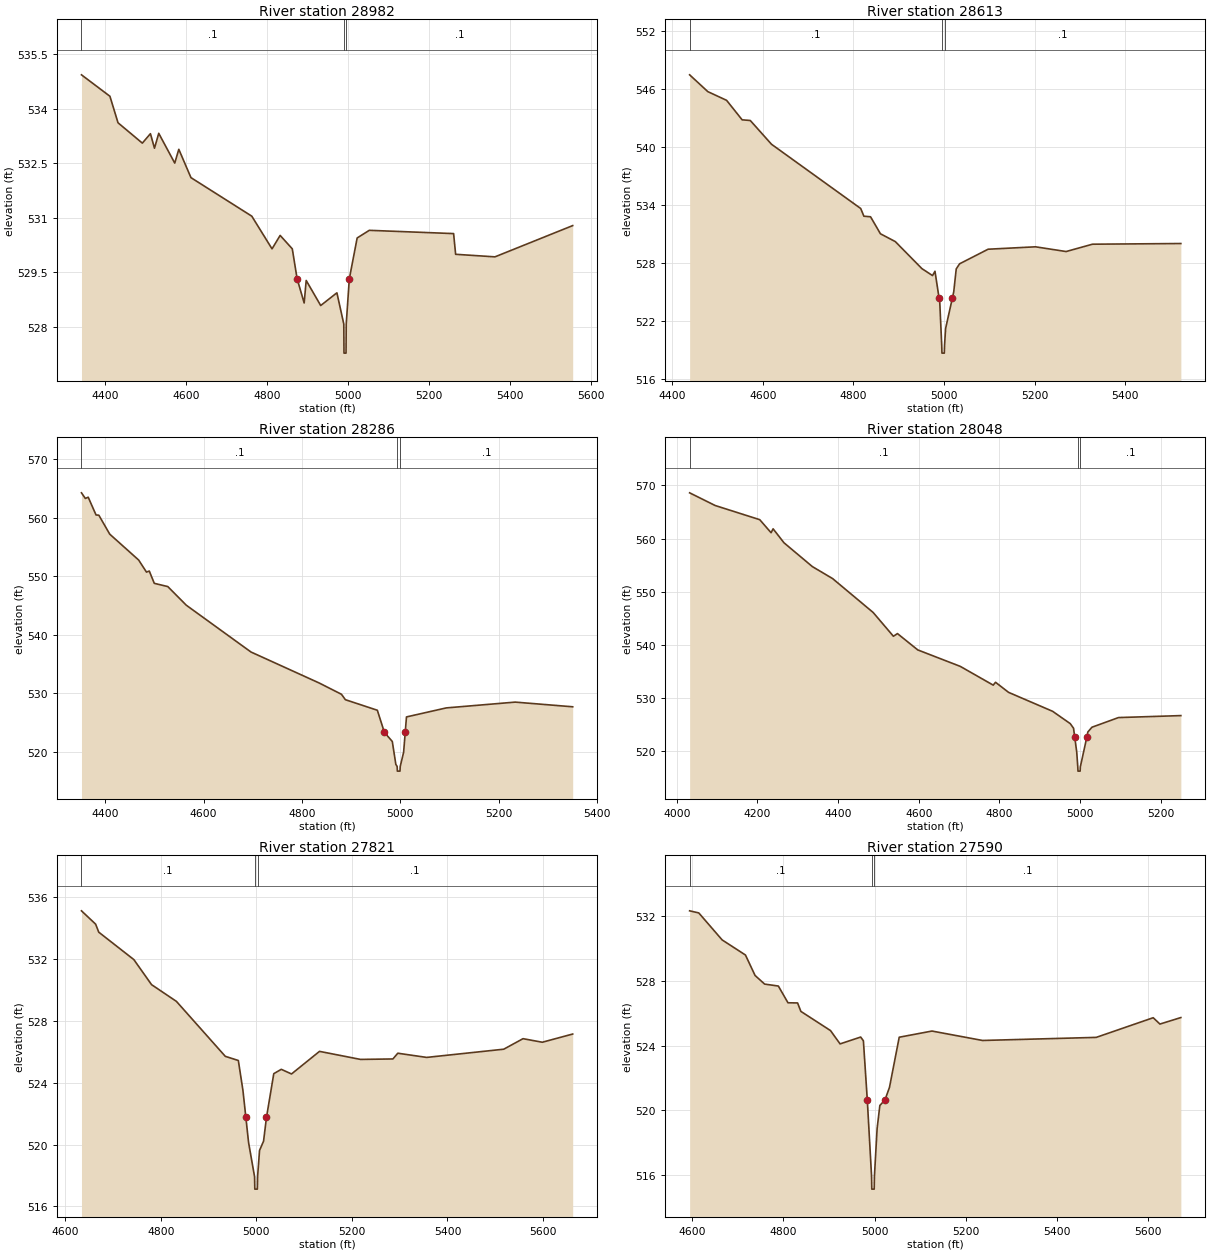
Type RM Length L Ch R = 1 ,28982   ,369,369,369
BEGIN DESCRIPTION:
Mapping XS fcfa0106
END DESCRIPTION:
XS GIS Cut Line= 2
      2020565.13     13490004.93      2019353.28     13490037.92
#Sta/Elev= 30
    4342  534.94  4412.2  534.35  4432.2  533.62  4492.2  533.06  4512.2  533.32
  4522.2  532.92  4532.7  533.33  4572.2  532.51  4582.2  532.89  4612.2  532.11
  4762.3  531.05  4812.3  530.15  4832.3  530.52  4862.3  530.15 4874.22529.3252
  4891.6  528.66  4896.6  529.28  4932.4  528.59  4972.4  528.94  4989.4  528.08
  4989.9  527.28  4994.9  527.28  4995.4  528.08 5003.03529.3254  5022.4  530.45
  5052.4  530.66  5260.4  530.57  5265.4     530  5362.5  529.93  5554.3  530.79
#Mann= 3 ,-1 , 0
    4342      .1       0  4989.4     .07       0  4995.4      .1       0
Bank Sta=4874.22,5003.03
XS Rating Curve= 0 ,0
Exp/Cntr=0.3,0.1

Type RM Length L Ch R = 1 ,28613   ,327,327,327
BEGIN DESCRIPTION:
UNT 015 in RCW 57.0
END DESCRIPTION:
XS GIS Cut Line= 3
      2020450.87     13489505.78      2019689.13     13489837.82
      2019495.57     13490000.18
#Sta/Elev= 30
  4438.7  547.45  4478.8  545.71  4520.2  544.81  4554.5  542.79  4572.5  542.72
  4619.3  540.26    4816  533.61  4823.1  532.81  4837.8  532.75  4859.6  530.99
  4892.4  530.18  4951.1  527.38  4974.5  526.66  4979.9  527.11 4989.03524.3107
  4990.5  523.86  4994.8  519.43  4995.3  518.63  5000.5  518.63    5001  519.43
  5003.4  521.19 5018.18524.3105  5021.3  524.98  5026.8  527.35  5034.2  527.88
  5097.1  529.39  5201.7  529.64  5269.2  529.15  5327.3  529.91  5522.3  529.98
#Mann= 3 ,-1 , 0
  4438.7      .1       0  4994.8     .07       0    5001      .1       0
Bank Sta=4989.03,5018.18
XS Rating Curve= 0 ,0
Exp/Cntr=0.3,0.1

Type RM Length L Ch R = 1 ,28286   ,238,238,238
BEGIN DESCRIPTION:
UNT 015 in RCW 56.0
END DESCRIPTION:
XS GIS Cut Line= 2
      2020324.98     13489175.01      2019455.81     13489666.07
#Sta/Elev= 30
    4352  564.24  4359.9  563.28  4365.7  563.49  4381.6  560.46  4387.3  560.42
  4409.4  557.19  4468.2  552.77  4484.1  550.71  4489.8  550.89    4500  548.79
  4527.4  548.24    4565  545.06  4696.5  537.07  4834.9  531.79  4880.3  529.86
  4888.4  528.93  4953.3  527.13 4967.57523.3643  4983.7   521.8  4990.9  517.89
  4993.5  517.54    4994  516.74  4999.3  516.74  4999.8  517.54  5006.7  519.96
 5009.97523.3598  5012.5  525.99  5093.4  527.53  5233.5  528.52  5350.3  527.72
#Mann= 3 ,-1 , 0
    4352      .1       0  4993.5     .07       0  4999.8      .1       0
Bank Sta=4967.57,5009.97
XS Rating Curve= 0 ,0
Exp/Cntr=0.3,0.1

Type RM Length L Ch R = 1 ,28048   ,227,227,227
BEGIN DESCRIPTION:
UNT 015 in RCW 55.0
END DESCRIPTION:
XS GIS Cut Line= 3
      2020578.05     13489061.34      2020008.58     13489113.43
      2019441.44     13489422.43
#Sta/Elev= 30
  4032.1  568.61  4095.4  566.22  4205.9  563.55    4234  561.09    4239  561.83
  4266.1  559.19  4336.4  554.71  4386.6  552.45    4487  546.07  4537.2  541.59
  4547.3  542.09  4597.5  539.02  4703.1  535.91  4784.7  532.38  4790.4  532.92
  4822.7  531.02  4931.9  527.45  4975.6  525.13  4983.8  524.26 4986.58522.6764
  4991.7  519.76  4994.3  516.98  4994.8  516.18  5000.1  516.18  5000.6  516.98
 5017.02522.6779  5019.2  523.55  5029.4  524.45  5095.2  526.27  5249.8  526.64
#Mann= 3 ,-1 , 0
  4032.1      .1       0  4994.3     .07       0  5000.6      .1       0
Bank Sta=4986.58,5017.02
XS Rating Curve= 0 ,0
Exp/Cntr=0.3,0.1

Type RM Length L Ch R = 1 ,27821   ,231,231,231
BEGIN DESCRIPTION:
Mapping XS 48334e36
END DESCRIPTION:
XS GIS Cut Line= 3
      2019866.24     13488935.46       2019355.8     13489235.82
      2019299.97     13489668.08
#Sta/Elev= 30
    4634   535.1  4663.6  534.24  4670.2  533.72  4743.6  531.95  4780.7  530.33
  4832.7  529.25    4935   525.7  4962.3  525.43  4971.9  523.51 4978.06521.7542
  4983.7  520.14  4996.3  517.92  4996.8  517.12  5002.1  517.12  5002.6  517.92
  5006.7  519.62  5015.1  520.22 5021.21521.7551  5036.5  524.58  5052.2  524.86
  5073.6  524.56  5132.2  526.02  5218.1   525.5  5285.9  525.53    5296   525.9
  5356.5  525.63  5517.8  526.16  5558.2  526.84  5598.5  526.61  5662.1  527.14
#Mann= 3 ,-1 , 0
    4634      .1       0  4996.3     .07       0  5002.6      .1       0
Bank Sta=4978.06,5021.21
XS Rating Curve= 0 ,0
Exp/Cntr=0.3,0.1

Type RM Length L Ch R = 1 ,27590   ,268,268,268
BEGIN DESCRIPTION:
Mapping XS 52cb2157
END DESCRIPTION:
XS GIS Cut Line= 3
      2019718.66     13488760.12      2019227.33     13489084.78
      2019053.17     13489541.71
#Sta/Elev= 30
  4594.2  532.29  4614.3  532.16  4665.5   530.5  4716.7  529.57  4737.8  528.31
  4758.8  527.78  4788.9  527.66    4810  526.63  4831.1  526.62  4838.3   526.1
  4903.3  524.92  4924.3   524.1  4969.5  524.52  4975.5  524.29 4984.05520.6478
  4993.4  515.96  4993.9  515.16  4999.2  515.16  4999.7  515.96  5005.6  518.89
  5011.6  520.31 5022.72520.6454  5032.7  521.42  5054.1  524.51    5126  524.89
    5237  524.31  5486.4   524.5  5611.4  525.71  5626.2  525.32  5672.1  525.72
#Mann= 3 ,-1 , 0
  4594.2      .1       0  4993.4     .07       0  4999.7      .1       0
Bank Sta=4984.05,5022.72
XS Rating Curve= 0 ,0
Exp/Cntr=0.3,0.1

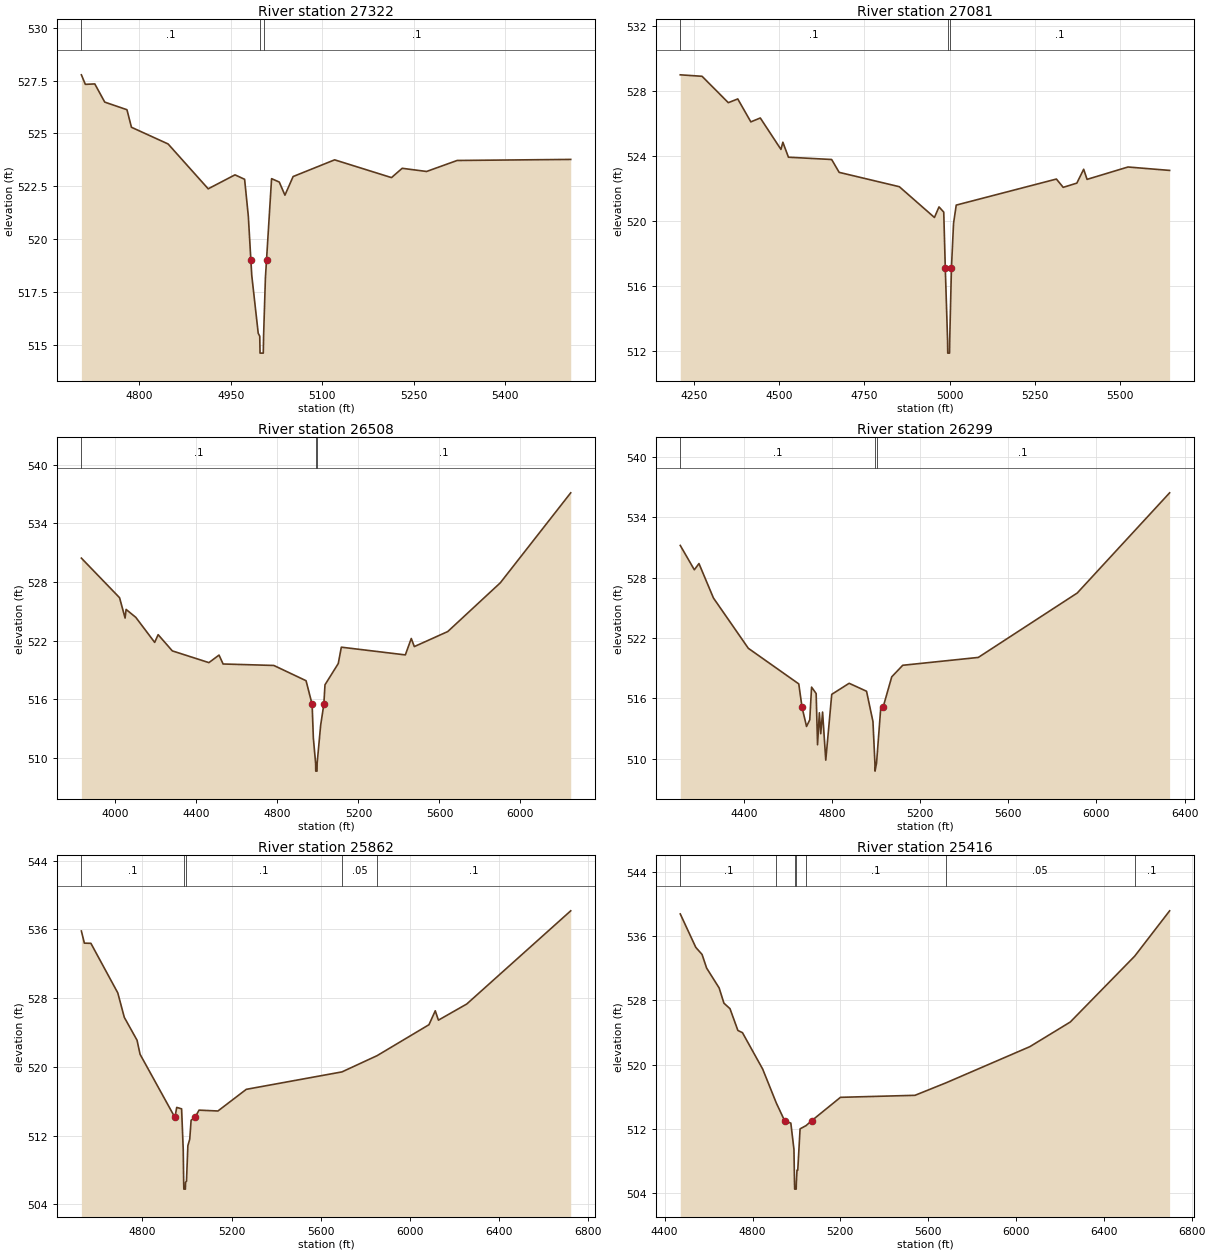
Type RM Length L Ch R = 1 ,27322   ,241,241,241
BEGIN DESCRIPTION:
Mapping XS 28ffa017
END DESCRIPTION:
XS GIS Cut Line= 3
      2019520.76     13488640.32      2019100.59     13488866.03
      2019093.96      13489191.2
#Sta/Elev= 30
  4704.9  527.77  4711.4  527.32  4726.9  527.34  4743.2  526.48  4779.6  526.12
    4787  525.29  4847.1   524.5  4912.8  522.38  4956.7  523.04  4972.5  522.83
  4978.6  521.08 4982.77519.0025  4984.2  518.29  4994.8  515.55  4997.3  515.41
  4997.8  514.61  5003.1  514.61  5003.6  515.41  5006.6  518.17 5008.39519.0012
  5016.7  522.86  5029.3   522.7  5038.6  522.08    5052  522.96  5120.1  523.75
  5213.3  522.91  5230.8  523.35  5270.8   523.2  5320.9  523.72  5507.1  523.77
#Mann= 3 ,-1 , 0
  4704.9      .1       0  4997.3     .07       0  5003.6      .1       0
Bank Sta=4982.77,5008.39
XS Rating Curve= 0 ,0
Exp/Cntr=0.3,0.1

Type RM Length L Ch R = 1 ,27081   ,573,573,573
BEGIN DESCRIPTION:
UNT 015 in RCW 54.0
END DESCRIPTION:
XS GIS Cut Line= 4
       2019840.6     13488202.41      2019219.95     13488527.92
      2019039.83     13488675.49      2019044.28     13489177.09
#Sta/Elev= 30
  4209.8  528.99  4273.7   528.9  4350.7  527.28  4378.4  527.51  4416.8   526.1
  4444.5  526.34  4505.1  524.41  4510.7  524.85  4527.1  523.93  4653.8  523.79
  4675.9     523  4852.3  522.12  4955.3  520.23  4968.7  520.88  4982.6  520.56
 4987.08517.1461  4993.8   512.7  4994.3   511.9  4999.6   511.9  5000.1   512.7
  5005.2 517.148  5011.3  519.86  5019.2  520.99    5313  522.59    5333  522.08
    5373  522.34    5393  523.19    5403  522.57    5523  523.33  5645.1  523.12
#Mann= 3 ,-1 , 0
  4209.8      .1       0  4993.8     .07       0  5000.1      .1       0
Bank Sta=4987.08,5005.2
XS Rating Curve= 0 ,0
Exp/Cntr=0.3,0.1

Type RM Length L Ch R = 1 ,26508   ,209,209,209
BEGIN DESCRIPTION:
UNT 015 in RCW 53.0
END DESCRIPTION:
XS GIS Cut Line= 3
      2019903.12     13488184.61       2018835.4     13488260.13
       2017715.6     13489007.53
#Sta/Elev= 30
  3831.6  530.45  4020.2   526.4  4047.5  524.32  4052.5   525.2  4100.4  524.39
  4193.6  521.83  4210.7  522.62  4280.8  520.96  4461.3  519.76  4511.4  520.53
  4531.5  519.62  4782.1  519.47  4941.2  517.91 4971.22515.4885  4977.2  512.06
  4988.5  509.46  4989.1  508.66  4995.4  508.66  4995.9  509.46  5013.3  513.35
 5029.01515.4896  5034.7  517.49  5100.4  519.67  5115.4  521.34  5431.5  520.55
  5460.9  522.23  5475.9   521.4  5641.1  522.94  5900.4  527.92  6248.3  537.13
#Mann= 3 ,-1 , 0
  3831.6      .1       0  4988.5     .07       0  4995.9      .1       0
Bank Sta=4971.22,5029.01
XS Rating Curve= 0 ,0
Exp/Cntr=0.3,0.1

Type RM Length L Ch R = 1 ,26299   ,437,437,437
BEGIN DESCRIPTION:
Mapping XS c1248129
END DESCRIPTION:
XS GIS Cut Line= 3
      2019296.32     13487507.55      2019012.48     13487918.98
      2017645.31     13488963.24
#Sta/Elev= 30
  4112.1   531.2  4175.9  528.78  4196.9   529.4  4262.5  525.98  4420.7  520.98
  4649.7  517.44  4664.7   515.1    4685  513.21  4699.6  513.87  4707.8  517.12
  4728.6  516.48  4734.9  511.39  4743.2  514.57  4749.4  512.49  4757.7  514.64
  4772.2  509.86  4799.3   516.4  4878.3   517.5  4957.2  516.71  4986.3   513.7
  4995.2  509.57  4995.7  508.77  5002.6  509.57  5021.6  515.03 5032.03515.1008
  5071.5  518.14  5121.4  519.29  5464.2  520.07  5913.1  526.47  6332.3  536.43
#Mann= 3 ,-1 , 0
  4112.1      .1       0  4995.2     .07       0  5002.6      .1       0
Bank Sta=4664.7,5032.03
XS Rating Curve= 0 ,0
Exp/Cntr=0.3,0.1

Type RM Length L Ch R = 1 ,25862   ,446,446,446
BEGIN DESCRIPTION:
UNT 015 in RCW 52.0
END DESCRIPTION:
XS GIS Cut Line= 3
        2019025.       13487375.        2018725.       13487775.
      2017524.97     13488975.03
#Sta/Elev= 30
  4525.9  535.81  4539.4   534.4  4568.6  534.38  4689.4  528.61  4718.6  525.77
  4775.9   523.1  4789.4  521.47 4945.89514.1223    4954  515.29  4975.9  515.12
  4983.2  510.38  4985.2  506.58    4986  505.78  4992.9  505.78  4993.6  506.58
  4997.8  506.69    5004  510.83  5012.4  511.59  5018.6   513.8    5036514.1219
  5054.2  514.97    5139  514.87  5266.3  517.39    5696  519.42  5853.7  521.31
  6086.6  524.91  6114.8  526.53    6129  525.44  6256.3  527.32    6723  538.16
#Mann= 5 ,-1 , 0
  4525.9      .1       0  4985.2     .07       0  4993.6      .1       0
    5696     .05       0  5853.7      .1       0
Bank Sta=4945.89,5036
XS Rating Curve= 0 ,0
Exp/Cntr=0.3,0.1

Type RM Length L Ch R = 1 ,25416   ,283,283,283
BEGIN DESCRIPTION:
UNT 015 in RCW 51.0
END DESCRIPTION:
XS GIS Cut Line= 3
      2018824.98     13487125.02        2018425.       13487475.
      2017225.03     13488674.97
#Sta/Elev= 30
  4471.1  538.79  4541.8  534.62  4570.3  533.74  4591.1  532.04  4648.1  529.56
  4669.9  527.66  4697.4  526.98  4733.5  524.26  4754.4  523.98  4846.4  519.44
  4908.3  515.22 4946.33512.9976  4974.6   512.7  4988.8  509.42  4991.3  505.27
    4992  504.47    4999  504.47  4999.7  505.27  5002.6  506.83  5006.1  506.83
  5016.7  511.99  5043.9  512.39 5069.22512.9979  5200.6  515.92    5540  516.17
  5680.6  517.72  6063.2  522.24  6247.1  525.31  6540.7  533.53  6699.6  539.18
#Mann= 7 ,-1 , 0
  4471.1      .1       0  4908.3     .16       0  4991.3     .07       0
  4999.7     .16       0  5043.9      .1       0  5680.6     .05       0
  6540.7      .1       0
Bank Sta=4946.33,5069.22
XS Rating Curve= 0 ,0
Exp/Cntr=0.3,0.1

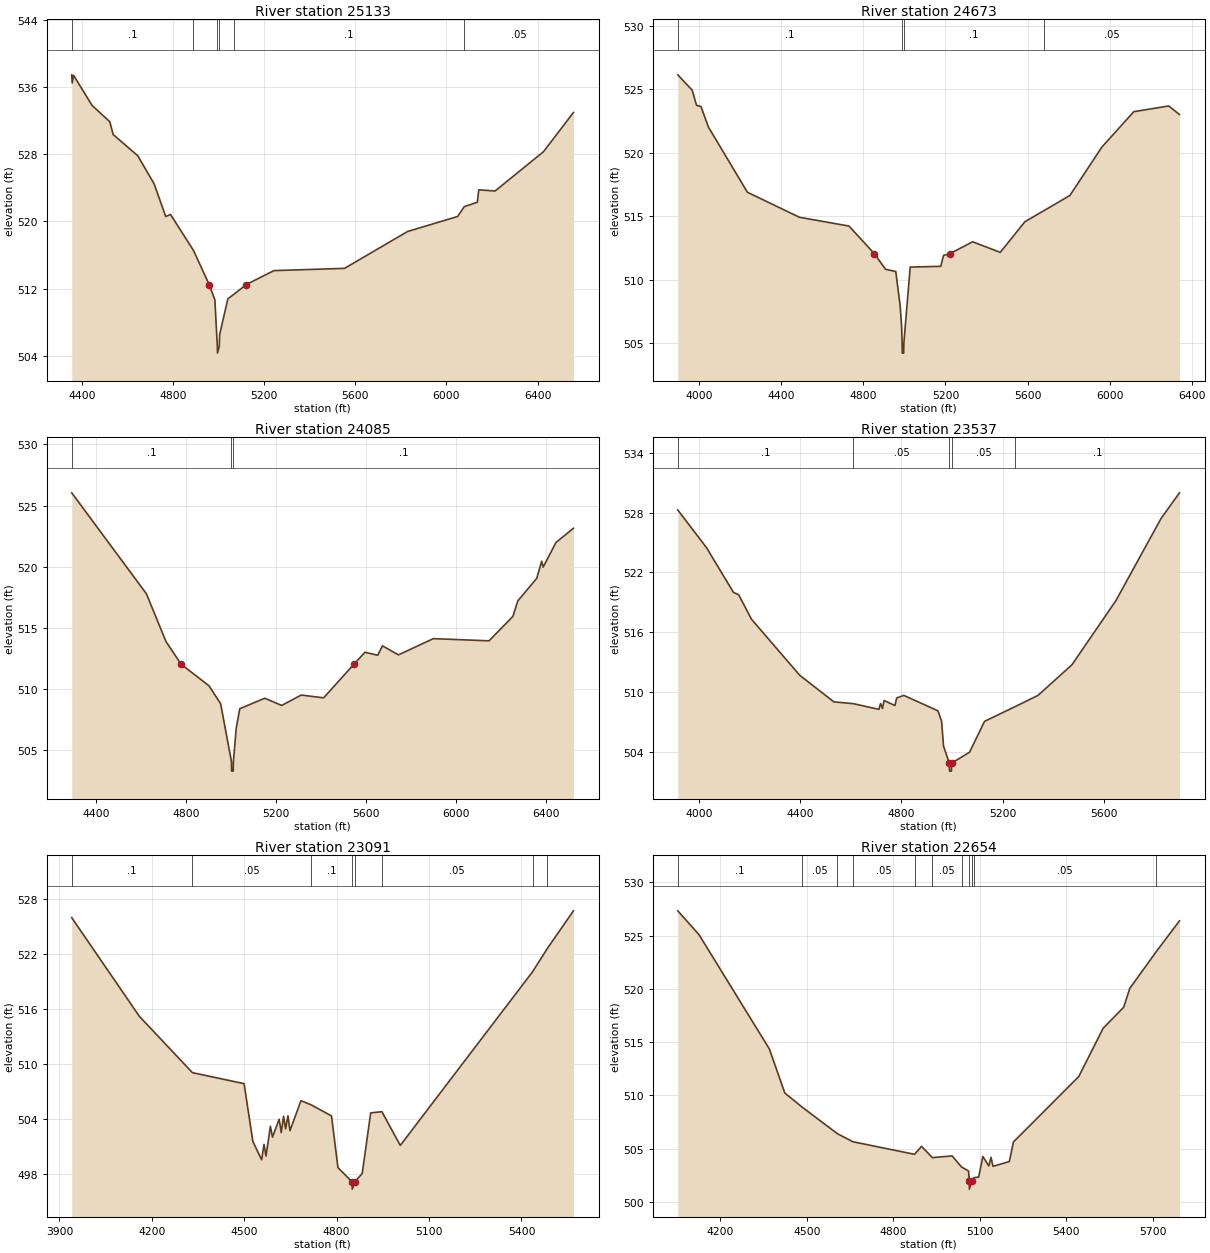
Type RM Length L Ch R = 1 ,25133   ,460,460,460
BEGIN DESCRIPTION:
UNT 015 in RCW 50.0
END DESCRIPTION:
XS GIS Cut Line= 3
      2018780.73     13486898.14      2017765.09     13487583.91
      2017144.43     13488339.11
#Sta/Elev= 30
  4354.4  537.43  4356.5  536.46  4362.5  537.37  4443.4   533.8  4521.4  531.86
  4536.3  530.33  4644.3  527.81  4716.2  524.46  4767.1  520.58  4788.1  520.83
    4889  516.55 4957.74512.4964  4982.9  510.68  4993.7  505.14  4994.4  504.34
  5002.1  505.14  5003.9  506.55  5039.9   510.8  5065.6  511.32    5121512.4963
  5242.1  514.15  5552.4  514.42  5828.9   518.8  6049.2  520.59  6077.7  521.75
  6135.3  522.28  6141.7  523.75  6213.5  523.62  6425.9  528.29  6557.4  532.95
#Mann= 6 ,-1 , 0
  4354.4      .1       0    4889     .16       0  4993.7     .07       0
  5002.1     .16       0  5065.6      .1       0  6077.7     .05       0
Bank Sta=4957.74,5121
XS Rating Curve= 0 ,0
Exp/Cntr=0.3,0.1

Type RM Length L Ch R = 1 ,24673   ,588,588,588
BEGIN DESCRIPTION:
UNT 015 in RCW 49.0
END DESCRIPTION:
XS GIS Cut Line= 3
      2018568.05     13485982.34      2018086.27     13486772.28
      2017057.63     13487892.07
#Sta/Elev= 30
  3894.9  526.13  3965.2  524.92  3986.5  523.73  4007.8  523.64  4044.6  522.01
  4234.3  516.89    4488  514.92  4729.6  514.23 4853.47512.0499  4907.7  510.83
  4957.7  510.65  4978.6  508.01    4986  506.39  4988.6  505.03  4989.3  504.23
  4996.3  504.23  4997.1  505.03    5028     511  5176.9  511.06  5190.7  511.92
 5220.48512.0499  5332.5  512.99    5467  512.16  5587.2  514.57  5678.8  515.43
  5806.7  516.64  5962.7  520.45    6118  523.23  6288.2  523.68  6340.7  523.01
#Mann= 4 ,-1 , 0
  3894.9      .1       0  4988.6     .07       0  4997.1      .1       0
  5678.8     .05       0
Bank Sta=4853.47,5220.48
XS Rating Curve= 0 ,0
Exp/Cntr=0.3,0.1

Type RM Length L Ch R = 1 ,24085   ,548,548,548
BEGIN DESCRIPTION:
UNT 015 in RCW 48.0
END DESCRIPTION:
XS GIS Cut Line= 3
      2017938.71     13485921.56      2017509.01     13486885.13
       2016620.8     13487660.69
#Sta/Elev= 30
  4290.1  526.04  4622.3  517.78  4709.9  513.86 4777.18512.0032  4901.2  510.24
  4953.1  508.77  5001.2  504.05    5002  503.25  5009.2  503.25    5010  504.05
  5022.8  506.79  5038.4  508.36  5149.8  509.22    5225  508.63  5312.1  509.48
  5411.8  509.25 5546.69512.0031  5595.9  512.98  5652.9  512.74  5673.8  513.51
    5745  512.77  5900.6   514.1  6148.4  513.92  6254.7  515.92  6276.6  517.19
    6361  519.04  6382.9  520.44  6389.5  519.96  6446.5  521.97  6524.3  523.14
#Mann= 3 ,-1 , 0
  4290.1      .1       0  5001.2     .07       0    5010      .1       0
Bank Sta=4777.18,5546.69
XS Rating Curve= 0 ,0
Exp/Cntr=0.3,0.1

Type RM Length L Ch R = 1 ,23537   ,446,446,446
BEGIN DESCRIPTION:
UNT 015 in RCW 47.0
END DESCRIPTION:
XS GIS Cut Line= 3
      2017875.01     13485824.99        2017175.       13486625.
      2016375.01     13487074.99
#Sta/Elev= 30
  3916.7  528.28  4030.1  524.49  4136.4     520  4157.3  519.75  4207.6   517.3
  4398.4  511.66  4533.2  508.99  4610.1  508.81  4710.7  508.24  4717.3  508.83
  4724.9  508.33  4731.5  509.13  4774.2  508.62  4780.9  509.38  4809.4  509.64
  4944.1  508.09  4958.4  507.04    4966  504.55  4988.9  502.83  4989.8  502.03
  4997.1  502.03  4997.9  502.83  5068.7  503.93  5127.9  507.03    5250  508.53
  5338.9  509.64  5473.1  512.72  5646.8  519.17  5824.6  527.41  5897.6     530
#Mann= 5 ,-1 , 0
  3916.7      .1       0  4610.1     .05       0  4988.9     .03       0
  4997.9     .05       0    5250      .1       0
Bank Sta=4988.9,4997.9
XS Rating Curve= 0 ,0
Exp/Cntr=0.3,0.1

Type RM Length L Ch R = 1 ,23091   ,437,437,437
BEGIN DESCRIPTION:
UNT 015 in RCW 46.0
END DESCRIPTION:
XS GIS Cut Line= 3
      2017475.01     13485624.99        2016775.       13486425.
      2016375.01     13486824.99
#Sta/Elev= 30
    3940  525.94  4159.7  515.17  4331.8  509.03  4499.5  507.83    4528  501.52
  4556.5  499.52  4564.1   501.2  4570.7  499.93  4584.9  503.18  4591.6  501.99
  4613.4  503.95  4620.1  502.48  4627.7  504.27  4634.3   502.9  4641.9  504.32
  4648.5   502.7  4684.1  505.97  4717.1  505.52  4783.3  504.31  4804.2  498.67
  4849.8  497.12  4850.7  496.32  4859.1  497.12    4883  498.03  4910.5  504.64
  4946.9  504.77  5006.6  501.09    5436  520.04  5483.8  522.57  5568.7  526.69
#Mann= 8 ,-1 , 0
    3940      .1       0  4331.8     .05       0  4717.1      .1       0
  4849.8     .03       0  4859.1      .1       0  4946.9     .05       0
    5436      .1       0  5483.8     .05       0
Bank Sta=4849.8,4859.1
XS Rating Curve= 0 ,0
Exp/Cntr=0.3,0.1

Type RM Length L Ch R = 1 ,22654   ,72,72,72
BEGIN DESCRIPTION:
UNT 015 in RCW 45.0
END DESCRIPTION:
XS GIS Cut Line= 3
      2017435.23     13485543.98      2017109.71     13485648.15
      2016055.04     13486568.27
#Sta/Elev= 30
  4051.8  527.33  4125.5  525.09  4369.6  514.36  4423.3  510.22  4482.7  508.91
  4605.7   506.4  4659.6  505.64  4873.7  504.46  4897.9  505.21  4935.4  504.15
  5004.2  504.31  5036.7  503.27  5061.2  502.89  5063.2  501.99    5064  501.19
  5072.5  501.99  5080.2  502.27  5096.3  502.32  5110.6  504.26  5131.4  503.37
  5139.1  504.18  5145.7  503.33  5202.7  503.78  5216.9  505.62  5443.8  511.77
  5528.3   516.3  5599.5  518.27  5620.7  520.04  5711.9  523.47  5793.2  526.39
#Mann= 11 ,-1 , 0
  4051.8      .1       0  4482.7     .05       0  4605.7      .1       0
  4659.6     .05       0  4873.7      .1       0  4935.4     .05       0
  5036.7      .1       0  5063.2    .033       0  5072.5      .1       0
  5080.2     .05       0  5711.9      .1       0
Bank Sta=5063.2,5072.5
XS Rating Curve= 0 ,0
Exp/Cntr=0.3,0.1

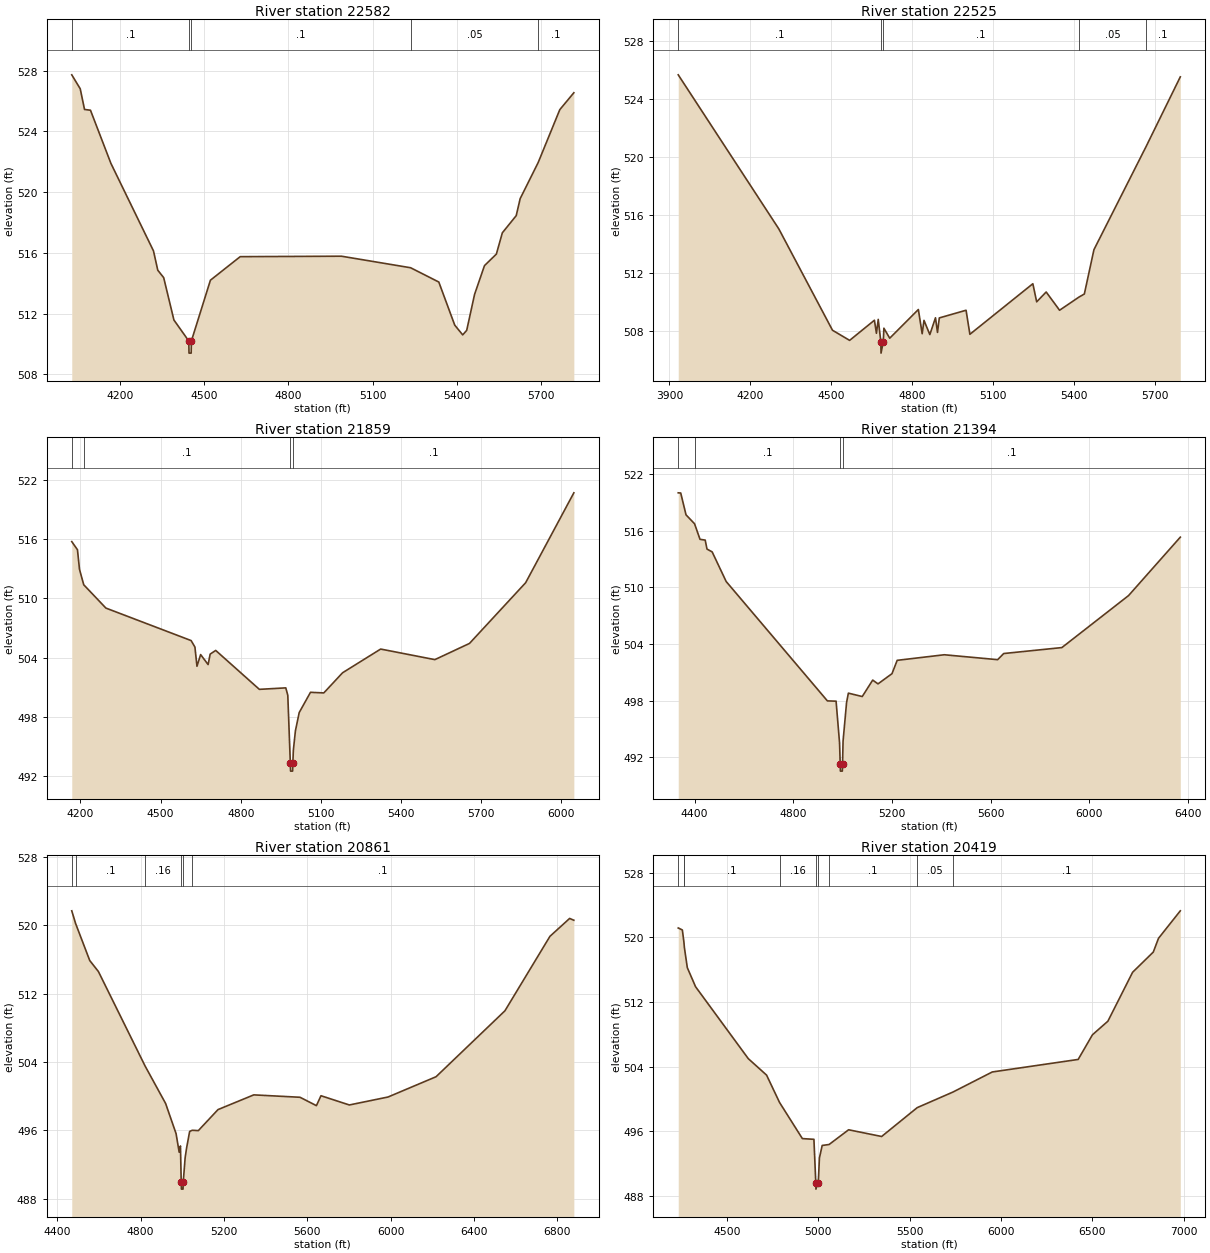
Type RM Length L Ch R = 1 ,22582   ,57,57,57
BEGIN DESCRIPTION:
Mapping XS 36d16c45
END DESCRIPTION:
XS GIS Cut Line= 4
      2017387.46     13485405.11      2016975.16     13485665.51
      2016276.37     13486286.17      2016015.92     13486546.62
#Sta/Elev= 30
  4027.1  527.72  4057.3   526.8  4072.6  525.44  4093.8  525.39  4166.7  521.89
  4318.5  516.13  4333.8  514.86  4354.9  514.37  4391.4  511.58  4444.4   510.2
  4445.3   509.4  4452.9   509.4  4453.7   510.2  4521.6   514.2  4627.8  515.75
    4989  515.78  5235.6  515.02  5336.1  514.08    5393  511.24  5421.4   510.6
  5435.6   510.9  5463.7  513.27    5499  515.16  5541.4  515.92  5562.7  517.32
  5612.2  518.45  5626.3  519.57  5690.6  521.95  5767.7  525.43  5817.7  526.54
#Mann= 5 ,-1 , 0
  4027.1      .1       0  4444.4     .07       0  4453.7      .1       0
  5235.6     .05       0  5690.6      .1       0
Bank Sta=4444.4,4453.7
XS Rating Curve= 0 ,0
Exp/Cntr=0.3,0.1

Type RM Length L Ch R = 1 ,22525   ,666,666,666
BEGIN DESCRIPTION:
UNT 015 in RCW 44.0
END DESCRIPTION:
XS GIS Cut Line= 3
      2017370.14     13485222.78      2016640.96     13485882.52
      2016002.96      13486485.8
#Sta/Elev= 30
  3932.6  525.67  4305.7  515.03  4504.5  508.04    4568  507.34  4659.9  508.73
  4667.4  507.83  4674.1  508.79  4683.6  507.26  4684.5  506.46  4692.9  507.26
    4695  508.18  4716.7  507.49  4822.8  509.47    4837   507.8  4843.7  508.72
  4865.4  507.74  4886.3   508.9  4893.8  507.89  4900.5  508.89  4999.7  509.42
  5013.9  507.76  5247.3  511.25  5261.5     510  5296.7  510.68  5346.4  509.42
  5418.4  510.33  5438.2  510.54  5473.8   513.6  5666.9  520.71    5794  525.53
#Mann= 5 ,-1 , 0
  3932.6      .1       0  4683.6     .07       0  4692.9      .1       0
  5418.4     .05       0  5666.9      .1       0
Bank Sta=4683.6,4692.9
XS Rating Curve= 0 ,0
Exp/Cntr=0.3,0.1

Type RM Length L Ch R = 1 ,21859   ,465,465,465
BEGIN DESCRIPTION:
UNT 015 in RCW 43.0
END DESCRIPTION:
XS GIS Cut Line= 3
      2016891.85     13484731.45      2015998.59     13485756.65
        2016025.     13486275.02
#Sta/Elev= 30
  4167.8  515.76  4189.1  514.94  4196.7  512.95  4212.6  511.39  4295.5  509.03
  4614.4  505.74  4628.7  505.08  4636.3  503.14    4650  504.32    4678  503.31
  4685.7  504.37  4706.5  504.74  4869.8   500.8  4968.6  500.95  4976.2   500.2
  4985.7  493.32  4986.6  492.52  4994.2  492.52  4995.1  493.32    4997  494.64
  5004.7   496.6  5018.9  498.45  5061.1   500.5    5111  500.44  5181.2  502.48
  5323.7  504.88  5526.5  503.81  5656.1  505.45  5866.3   511.6  6046.6   520.7
#Mann= 4 ,-1 , 0
  4167.8     .05       0  4212.6      .1       0  4985.7     .07       0
  4995.1      .1       0
Bank Sta=4985.7,4995.1
XS Rating Curve= 0 ,0
Exp/Cntr=0.3,0.1

Type RM Length L Ch R = 1 ,21394   ,533,533,533
BEGIN DESCRIPTION:
Mapping XS 4039dfad
END DESCRIPTION:
XS GIS Cut Line= 3
      2016573.26     13484528.77      2015788.53     13485372.54
      2015743.39      13486254.5
#Sta/Elev= 30
  4333.8  519.99  4343.9  519.97  4365.4  517.66  4399.9  516.72  4422.1  515.07
  4443.1  514.99  4450.4  514.04  4471.4  513.74  4528.1  510.61  4938.5  497.98
  4973.7  497.95  4987.8  493.54  4990.4  491.35  4991.3  490.55    4999  490.55
    5000  491.35    5002  493.72  5016.2   497.8  5023.5   498.8  5079.8  498.44
  5122.2  500.18  5143.7  499.78  5200.4  500.86  5221.4  502.27  5412.4  502.86
  5628.7  502.34  5653.3  502.99  5889.1  503.62  6159.4  509.12  6369.2   515.3
#Mann= 4 ,-1 , 0
  4333.8     .05       0  4399.9      .1       0  4990.4     .07       0
    5000      .1       0
Bank Sta=4990.4,5000
XS Rating Curve= 0 ,0
Exp/Cntr=0.3,0.1

Type RM Length L Ch R = 1 ,20861   ,442,442,442
BEGIN DESCRIPTION:
UNT 015 in RCW 42.0
END DESCRIPTION:
XS GIS Cut Line= 3
      2016043.71     13484254.52      2015220.82      13485389.9
      2015163.52     13486395.15
#Sta/Elev= 30
  4469.6  521.67  4488.1  520.18  4555.8  515.86  4597.5  514.57  4821.3  503.53
    4920  499.14  4970.2  495.61  4984.9  493.45  4991.1  494.18  4994.8  489.93
  4995.7  489.13  5003.5  489.13  5004.4  489.93  5013.6   492.8  5020.5  493.93
  5035.2  495.87  5047.4  496.01  5076.9  495.97  5171.3  498.43  5342.9  500.15
  5564.8  499.87  5643.5  498.89  5665.4  500.05  5801.4  498.97  5987.1   499.9
  6217.5  502.27    6548  509.98  6764.1  518.69  6858.5  520.78  6878.7  520.57
#Mann= 6 ,-1 , 0
  4469.6     .05       0  4488.1      .1       0  4821.3     .16       0
  4994.8     .07       0  5004.4     .16       0  5047.4      .1       0
Bank Sta=4994.8,5004.4
XS Rating Curve= 0 ,0
Exp/Cntr=0.3,0.1

Type RM Length L Ch R = 1 ,20419   ,482,482,482
BEGIN DESCRIPTION:
UNT 015 in RCW 41.0
END DESCRIPTION:
XS GIS Cut Line= 3
      2015725.01     13483974.99      2014741.65     13485468.03
      2014008.61     13486086.69
#Sta/Elev= 30
  4233.5  521.14  4256.1  520.89  4264.5  519.41  4267.2  518.72  4283.2  516.23
  4328.4  513.87  4616.7  504.98  4716.9  502.94  4787.8  499.56  4912.7  495.09
  4975.9     495  4986.1  489.64    4987  488.84  4995.8  489.64  4999.9  489.68
    5006   492.7  5021.1  494.24  5058.9  494.36  5165.7  496.18  5346.4  495.35
  5541.1  498.92    5736  500.84  5951.7  503.33  6421.7  504.88  6499.8  507.93
  6584.3  509.61  6719.5  515.66  6832.7  518.16  6861.2  519.86  6980.5  523.26
#Mann= 9 ,-1 , 0
  4233.5     .08       0  4264.5     .05       0  4267.2      .1       0
  4787.8     .16       0  4986.1     .07       0  4995.8     .16       0
  5058.9      .1       0  5541.1     .05       0    5736      .1       0
Bank Sta=4986.1,4995.8
XS Rating Curve= 0 ,0
Exp/Cntr=0.3,0.1