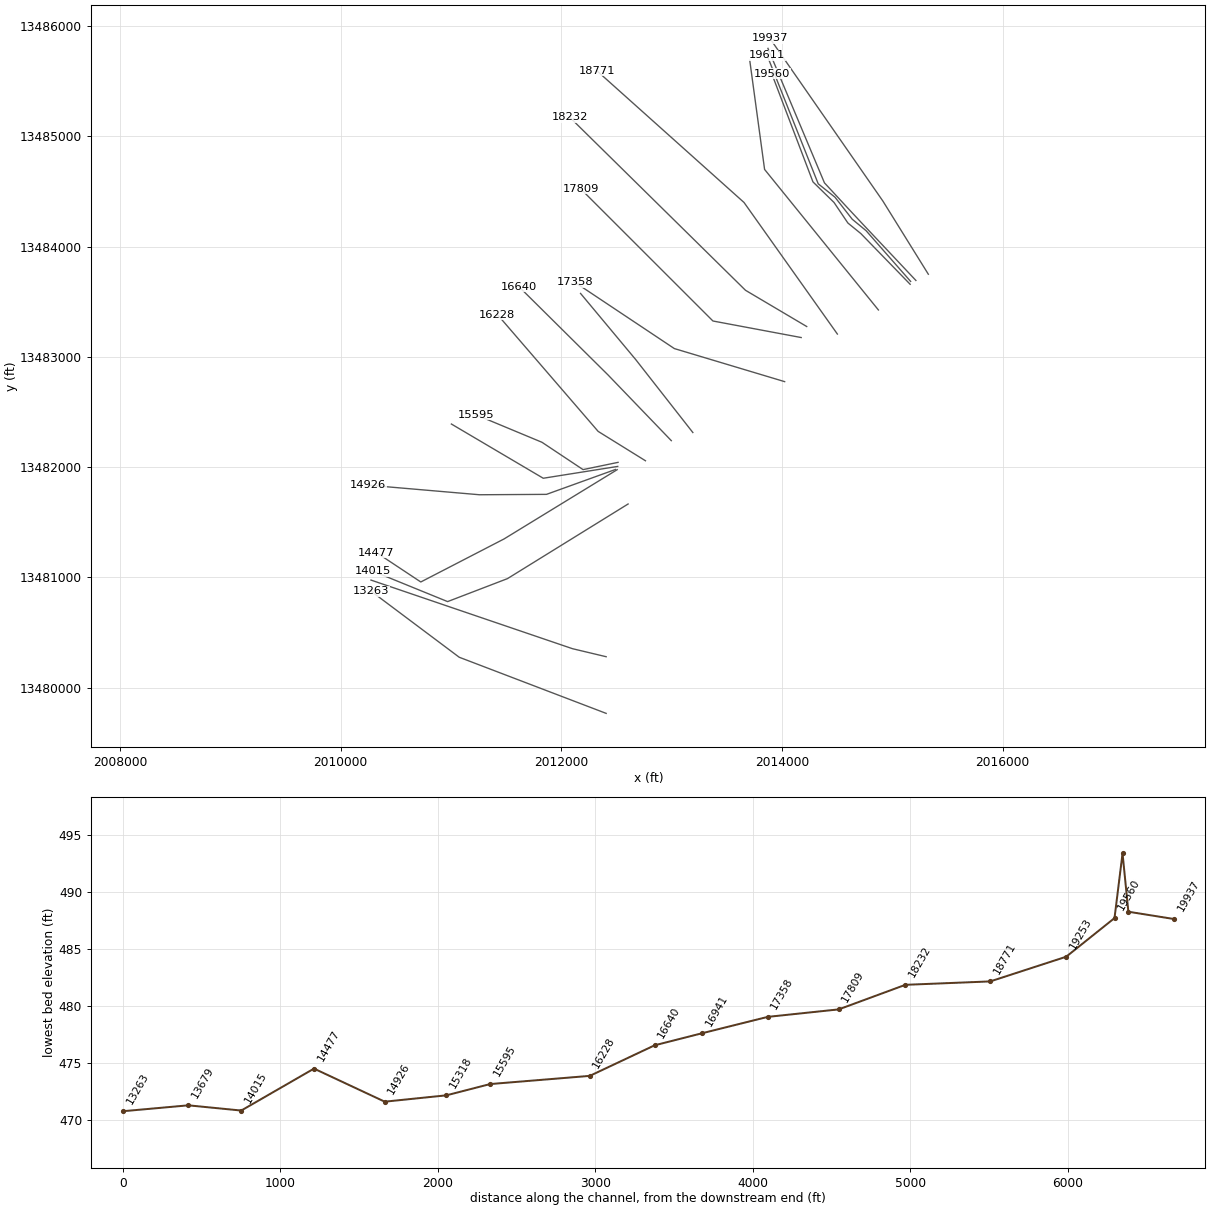
HEC-RAS study UNT 015 in RCW.prj: UNT 015 in RCW Base Level Engineering

--- UNT 015 in RCW.g01 (geometry) --- (continued)

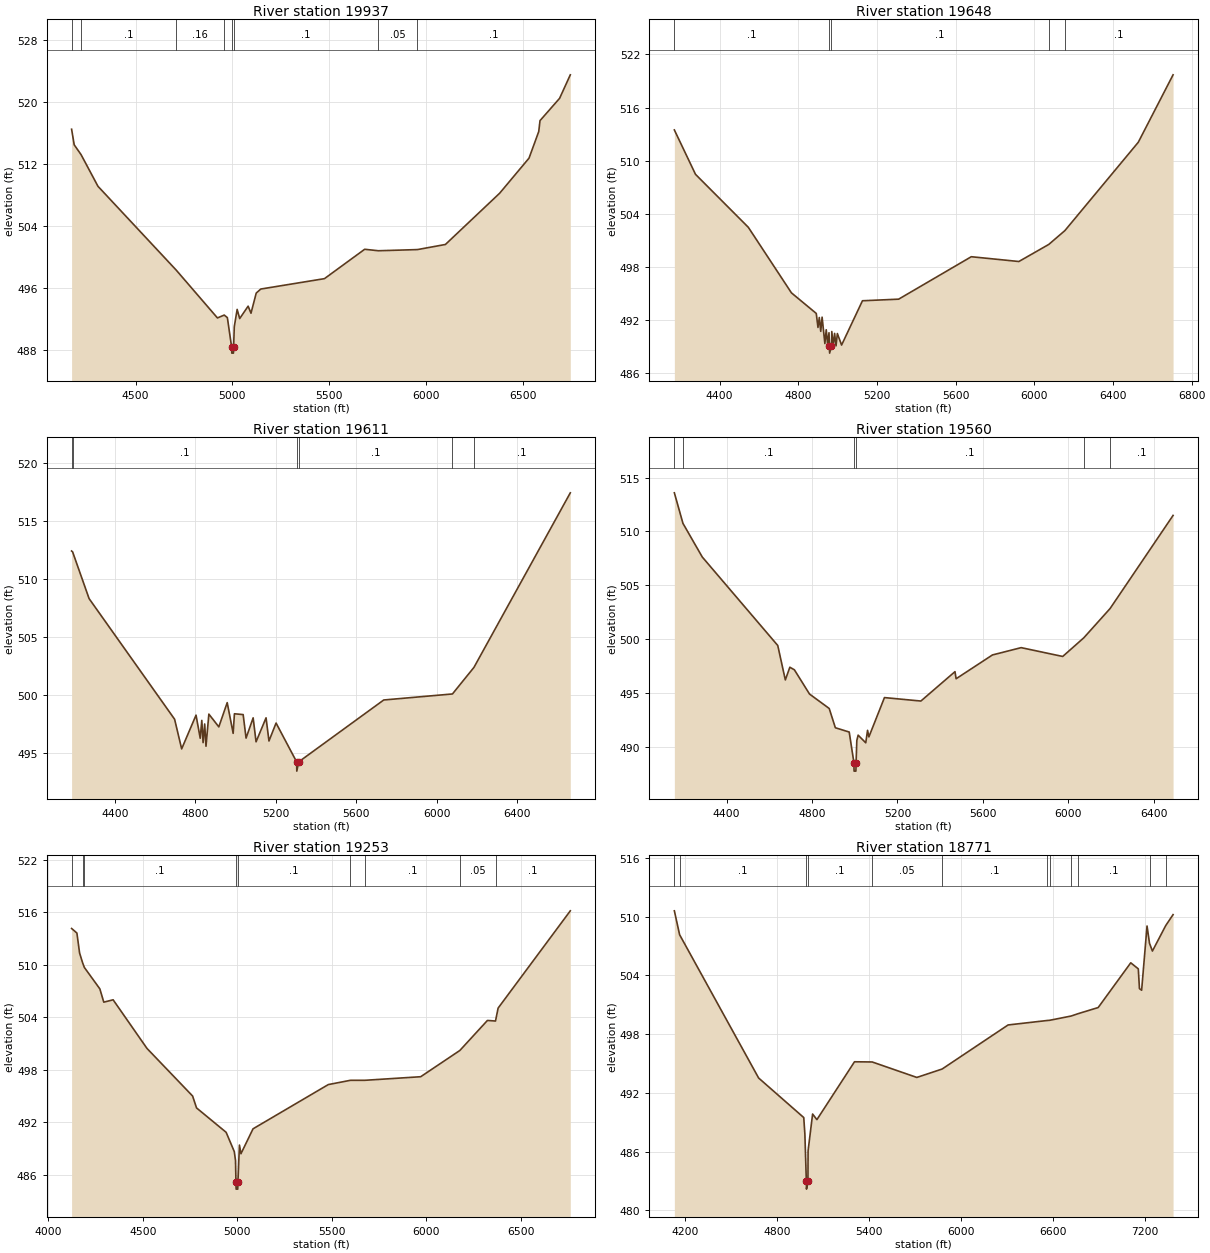
Type RM Length L Ch R = 1 ,19937   ,289,289,289
BEGIN DESCRIPTION:
UNT 015 in RCW 40.0
END DESCRIPTION:
XS GIS Cut Line= 3
      2015327.58     13483749.29      2014915.26     13484413.34
      2013890.95     13485889.04
#Sta/Elev= 30
  4169.1  516.54  4182.6  514.53  4218.1  513.26  4305.3  509.18  4709.6  498.37
    4923  492.19  4958.1  492.56  4974.3  492.23  4996.3  488.45  4997.2  487.65
  5005.7  487.65  5006.6  488.45  5010.1  491.06  5024.9  493.29    5038  492.11
  5081.7  493.71  5096.5   492.8  5123.5   495.4  5147.2  495.92  5476.2  497.26
  5684.1  501.05  5754.9  500.86  5956.9  501.01  6101.5  501.67  6381.8  508.28
  6533.7  512.81  6583.9  516.24  6590.5  517.65  6691.8  520.53  6747.1  523.56
#Mann= 8 ,-1 , 0
  4169.1     .05       0  4218.1      .1       0  4709.6     .16       0
  4958.1      .1       0  4996.3     .07       0  5006.6      .1       0
  5754.9     .05       0  5956.9      .1       0
Bank Sta=4996.3,5006.6
XS Rating Curve= 0 ,0
Exp/Cntr=0.3,0.1

Type RM Length L Ch R = 1 ,19648   ,37,37,37
BEGIN DESCRIPTION:
Mapping XS deb34727
END DESCRIPTION:
XS GIS Cut Line= 5
      2015214.72     13483692.87      2014719.95     13484218.03
      2014598.42     13484348.23      2014385.75     13484578.27
      2013873.59     13485797.89
#Sta/Elev= 30
  4169.8  513.48  4277.3  508.47  4545.9  502.49  4765.2  495.09  4891.3  492.77
    4900  491.19  4906.8  492.31  4914.1  490.75    4921  492.35  4935.1  489.37
    4942  490.93  4949.3  489.26  4956.1  490.59  4958.3  489.09  4959.2  488.29
  4968.6  489.09  4970.3  490.73  4977.6  489.13  4984.5  490.52  4991.8  489.11
  4998.6   490.5  5020.1   489.2  5126.2   494.2  5310.2  494.38  5679.5  499.17
  5921.5  498.63  6073.7  500.56  6155.5  502.12  6528.7  512.09  6705.5   519.7
#Mann= 5 ,-1 , 0
  4169.8      .1       0  4958.3     .07       0  4968.6      .1       0
  6073.7     .05       0  6155.5      .1       0
Bank Sta=4958.3,4968.6
XS Rating Curve= 0 ,0
Exp/Cntr=0.3,0.1

Type RM Length L Ch R = 1 ,19611   ,51,51,51
BEGIN DESCRIPTION:
Mapping XS 7af9908f
END DESCRIPTION:
XS GIS Cut Line= 6
      2015167.02     13483684.14      2014763.35     13484144.24
      2014637.48     13484248.41      2014481.23     13484448.06
      2014329.32     13484569.59      2013864.93     13485737.09
#Sta/Elev= 30
  4184.8  512.42  4189.9  512.34  4271.8  508.31    4697   497.9  4732.1  495.34
  4803.6  498.25  4824.4  496.26  4832.2   497.8  4838.7  495.88  4846.6  497.49
  4853.1  495.57  4867.4  498.34  4916.9  497.24  4958.6  499.33  4988.2  496.68
  4994.5  498.37  5037.9   498.3  5052.4  496.27  5087.6  498.02  5102.1  495.95
  5151.8  498.02  5166.3  496.02  5201.6  497.57  5303.8  494.22  5304.7  493.42
  5314.1  494.22    5737  499.56  6078.7  500.08  6185.5  502.37  6664.8  517.44
#Mann= 6 ,-1 , 0
  4184.8     .05       0  4189.9      .1       0  5303.8     .07       0
  5314.1      .1       0  6078.7     .05       0  6185.5      .1       0
Bank Sta=5303.8,5314.1
XS Rating Curve= 0 ,0
Exp/Cntr=0.3,0.1

Type RM Length L Ch R = 1 ,19560   ,307,307,307
BEGIN DESCRIPTION:
Mapping XS 632aabcf
END DESCRIPTION:
XS GIS Cut Line= 6
      2015162.67     13483658.11      2014715.61      13484118.2
      2014598.42     13484213.69      2014472.55     13484400.32
      2014281.58     13484586.95      2013908.31     13485567.86
#Sta/Elev= 30
  4155.8  513.58  4196.1  510.74  4286.4  507.62  4639.8   499.4  4675.3   496.2
  4696.4  497.38  4717.7  497.14  4788.5  494.89  4880.6  493.55  4909.4  491.76
  4974.3  491.36  4996.2  488.53  4997.1  487.73  5005.6  487.73  5006.5  488.53
  5009.9  490.57  5016.1  491.07  5051.7  490.36  5060.2  491.52  5066.4  490.91
  5139.3  494.56  5309.8  494.24  5469.4  496.97  5474.7  496.31  5644.7  498.52
  5779.2   499.2  5973.7  498.38  6072.3  500.11  6195.4  502.83  6490.3  511.48
#Mann= 6 ,-1 , 0
  4155.8     .05       0  4196.1      .1       0  4996.2     .07       0
  5006.5      .1       0  6072.3     .05       0  6195.4      .1       0
Bank Sta=4996.2,5006.5
XS Rating Curve= 0 ,0
Exp/Cntr=0.3,0.1

Type RM Length L Ch R = 1 ,19253   ,482,482,482
BEGIN DESCRIPTION:
UNT 015 in RCW 39.0
END DESCRIPTION:
XS GIS Cut Line= 3
      2014874.99     13483425.01      2013843.21      13484699.8
      2013708.66     13485689.38
#Sta/Elev= 30
  4122.8  514.15  4150.8  513.63  4165.2  511.33  4181.2  510.22  4190.4  509.69
  4272.3  507.24  4293.1  505.72  4342.6  505.99  4521.6  500.43  4763.1  494.98
  4783.9  493.62  4940.5  490.83  4983.7  488.62  4990.1   487.6  4992.5  485.13
  4993.4  484.33  5001.9  484.33  5002.8  485.13  5010.9  489.37  5018.9  488.38
  5082.8  491.23  5480.9  496.29  5598.1  496.78  5674.5  496.78  5969.9  497.19
  6176.9  500.19  6323.1  503.63  6365.7  503.56  6379.5  505.04  6761.5  516.17
#Mann= 9 ,-1 , 0
  4122.8     .08       0  4181.2     .05       0  4190.4      .1       0
  4992.5     .07       0  5002.8      .1       0  5598.1     .05       0
  5674.5      .1       0  6176.9     .05       0  6365.7      .1       0
Bank Sta=4992.5,5002.8
XS Rating Curve= 0 ,0
Exp/Cntr=0.3,0.1

Type RM Length L Ch R = 1 ,18771   ,539,539,539
BEGIN DESCRIPTION:
UNT 015 in RCW 38.0
END DESCRIPTION:
XS GIS Cut Line= 3
      2014502.96     13483206.71      2013656.58     13484400.32
      2012324.13     13485593.88
#Sta/Elev= 30
  4132.1  510.59  4166.3  508.15  4681.7  493.51  4975.9  489.47  4983.2  487.79
  4992.8  482.96  4993.7  482.16  5003.1  482.96  5004.1  486.07  5033.6  489.83
  5061.7  489.26  5306.8  495.17  5422.2  495.15  5713.2  493.57  5878.3  494.43
  6308.3  498.93  6559.8  499.38  6580.3  499.41    6719  499.84  6762.3  500.07
  6895.9  500.71  7108.2  505.28  7157.5  504.66    7165  502.64  7179.2  502.48
  7214.4  509.04  7230.6  507.27  7249.5  506.48  7336.6  509.09  7384.2   510.2
#Mann= 12 ,-1 , 0
  4132.1     .05       0  4166.3      .1       0  4992.8     .07       0
  5003.1      .1       0  5422.2     .05       0  5878.3      .1       0
  6559.8     .07       0  6580.3      .1       0    6719     .07       0
  6762.3      .1       0  7230.6     .05       0  7336.6      .1       0
Bank Sta=4992.8,5003.1
XS Rating Curve= 0 ,0
Exp/Cntr=0.3,0.1

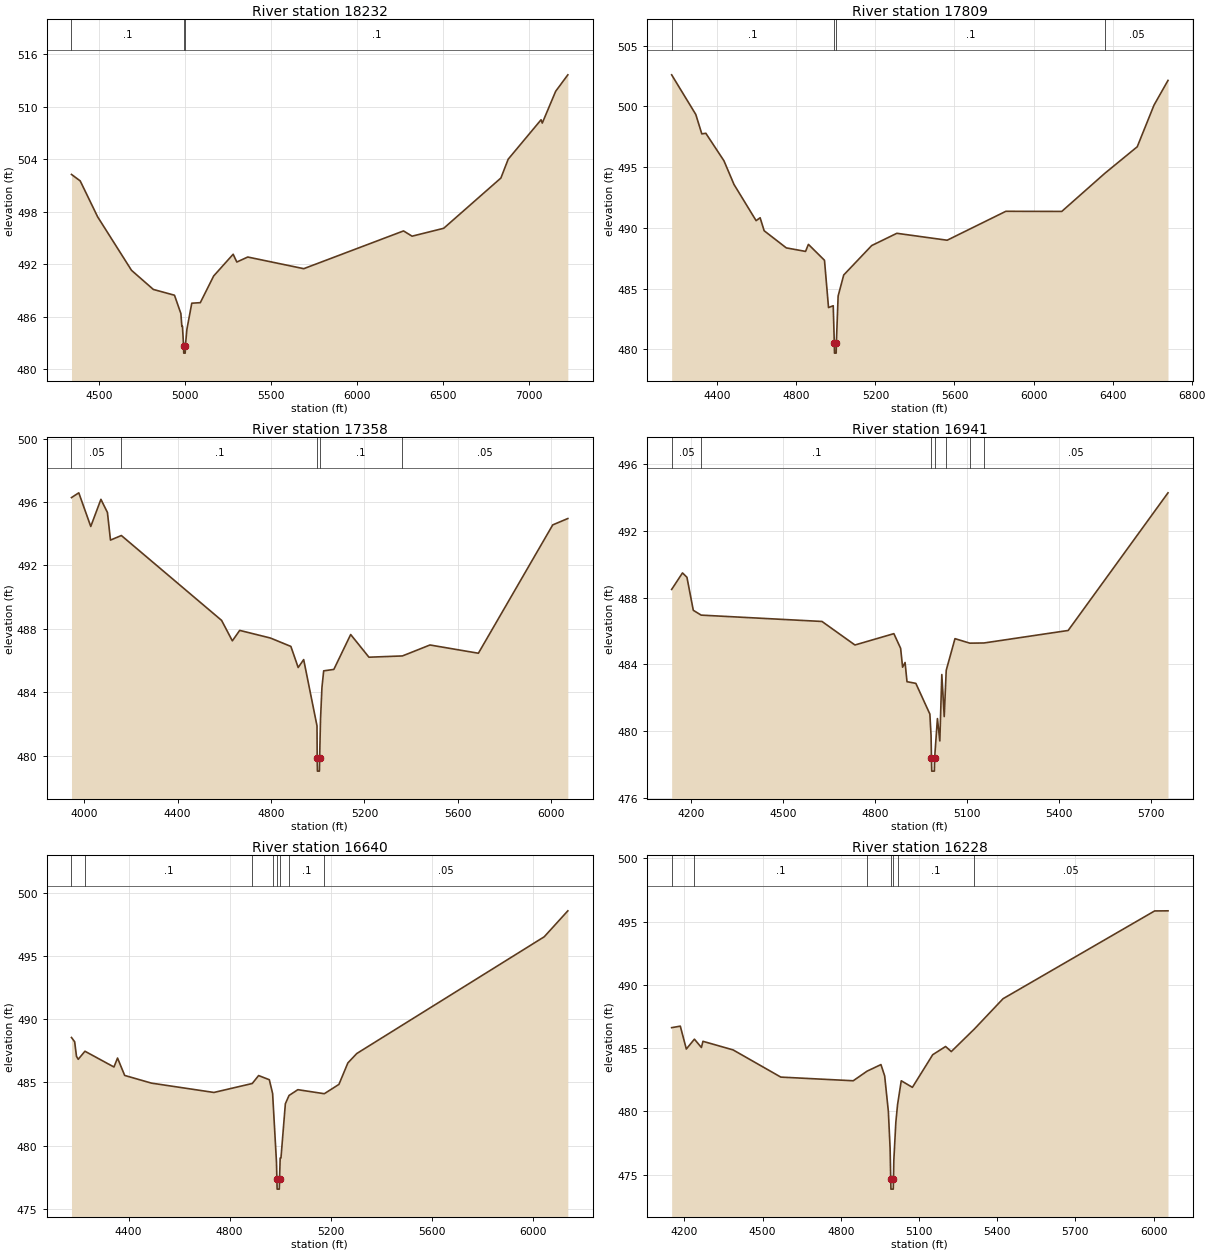
Type RM Length L Ch R = 1 ,18232   ,423,423,423
BEGIN DESCRIPTION:
UNT 015 in RCW 37.0
END DESCRIPTION:
XS GIS Cut Line= 3
      2014224.99       13483275.      2013670.13     13483603.59
        2012075.       13485175.
#Sta/Elev= 30
  4340.8  502.26  4391.5  501.52  4492.8  497.42  4689.7  491.31  4816.5  489.13
  4939.3  488.47  4976.4  486.38  4982.1  484.92  4985.7  484.92  4992.2  482.66
  4993.1  481.86  5001.6  481.86  5002.5  482.66  5011.5  484.59  5039.8  487.56
  5089.3  487.62  5167.1  490.67  5280.2  493.15  5301.5  492.26  5365.1  492.83
  5690.4   491.5  6270.2  495.81  6319.7  495.21  6503.5  496.11  6835.9  501.85
  6878.3     504  7069.3   508.5  7076.3  508.12  7154.1  511.75  7224.8  513.63
#Mann= 3 ,-1 , 0
  4340.8      .1       0  4992.2     .07       0  5002.5      .1       0
Bank Sta=4992.2,5002.5
XS Rating Curve= 0 ,0
Exp/Cntr=0.3,0.1

Type RM Length L Ch R = 1 ,17809   ,451,451,451
BEGIN DESCRIPTION:
UNT 015 in RCW 36.0
END DESCRIPTION:
XS GIS Cut Line= 3
      2014174.97     13483175.01        2013375.       13483325.
      2012174.98     13484525.02
#Sta/Elev= 30
  4169.3   502.6  4291.4  499.34  4321.9  497.74  4342.2  497.79  4433.8  495.53
  4484.7  493.58  4596.6   490.6  4616.9  490.84  4637.3  489.77  4749.2  488.36
  4846.7  488.07  4861.1  488.65  4942.5  487.34  4962.9  483.45  4986.7   483.6
  4992.2   480.5  4993.1   479.7  5001.6   479.7  5002.5   480.5  5011.5   484.4
  5039.8  486.13  5181.2  488.55  5308.5  489.56    5563  488.99    5860  491.37
  6142.9  491.36  6360.3  494.49  6524.7  496.68  6609.6  500.11  6680.3  502.14
#Mann= 4 ,-1 , 0
  4169.3      .1       0  4992.2     .07       0  5002.5      .1       0
  6360.3     .05       0
Bank Sta=4992.2,5002.5
XS Rating Curve= 0 ,0
Exp/Cntr=0.3,0.1

Type RM Length L Ch R = 1 ,17358   ,417,417,417
BEGIN DESCRIPTION:
UNT 015 in RCW 35.0
END DESCRIPTION:
XS GIS Cut Line= 3
      2014024.99       13482775.        2013025.       13483075.
      2012124.98     13483675.01
#Sta/Elev= 30
  3945.6  496.28  3976.9  496.58  4028.2  494.46  4071.7  496.17  4099.6  495.34
  4112.6   493.6  4159.2  493.89  4588.5  488.54  4634.6  487.25    4666  487.91
  4797.3  487.43  4885.2   486.9  4916.5  485.57    4940  486.07  4997.1  481.89
  4997.9  479.84  4998.9  479.04  5007.4  479.04  5008.3  479.84  5012.1  482.29
  5018.2   484.3  5025.7  485.36  5069.2  485.45  5141.3  487.65  5219.5  486.22
    5363   486.3  5480.9  486.99  5688.2  486.47  6006.7  494.56  6071.3  494.96
#Mann= 5 ,-1 , 0
  3945.6     .05       0  4159.2      .1       0  4997.9     .07       0
  5008.3      .1       0    5363     .05       0
Bank Sta=4997.9,5008.3
XS Rating Curve= 0 ,0
Exp/Cntr=0.3,0.1

Type RM Length L Ch R = 1 ,16941   ,301,301,301
BEGIN DESCRIPTION:
UNT 015 in RCW 34.0
END DESCRIPTION:
XS GIS Cut Line= 3
      2013192.89     13482313.46        2012675.       13482975.
      2012174.98     13483575.02
#Sta/Elev= 30
  4135.9  488.49  4171.3  489.48  4185.8  489.22  4206.6  487.24  4232.3  486.95
    4627  486.57  4734.6  485.16  4861.7  485.84  4883.8  484.96  4890.2  483.83
  4898.3  484.11  4904.6  482.96  4933.5  482.86  4979.3  481.02  4983.2  479.72
  4984.5   478.4  4985.4   477.6    4994   477.6  4994.9   478.4    5004  480.75
  5011.8  479.41  5018.3  483.39  5026.2  480.87  5030.8  482.83  5032.7  483.64
  5061.3  485.54  5109.8  485.27  5155.9  485.28    5431  486.03  5757.1  494.28
#Mann= 7 ,-1 , 0
  4135.9     .05       0  4232.3      .1       0  4984.5     .07       0
  4994.9      .1       0  5030.8     .12       0  5109.8      .1       0
  5155.9     .05       0
Bank Sta=4984.5,4994.9
XS Rating Curve= 0 ,0
Exp/Cntr=0.3,0.1

Type RM Length L Ch R = 1 ,16640   ,412,412,412
BEGIN DESCRIPTION:
UNT 015 in RCW 33.0
END DESCRIPTION:
XS GIS Cut Line= 3
      2012997.54     13482239.72      2012424.33     13482835.34
      2011615.29     13483637.45
#Sta/Elev= 30
  4173.8  488.57  4186.4  488.23  4193.6  487.08  4200.5  486.84  4227.1  487.48
    4342  486.23  4356.2  486.94  4384.5  485.56  4490.5  484.95  4737.9  484.21
  4889.7  484.92    4915  485.55  4957.4  485.22  4970.4  484.13  4985.7  478.69
  4987.4  477.34  4988.3  476.54  4996.9  476.54  4997.8  477.34  5000.4  479.01
  5003.5  479.01  5020.9  483.31  5035.4  483.97  5070.4  484.43  5175.1  484.11
  5233.1  484.85  5268.4  486.55  5303.8   487.3  6046.2  496.56  6139.7  498.62
#Mann= 8 ,-1 , 0
  4173.8     .05       0  4227.1      .1       0  4889.7     .07       0
  4970.4     .12       0  4987.4     .07       0  4997.8     .12       0
  5035.4      .1       0  5175.1     .05       0
Bank Sta=4987.4,4997.8
XS Rating Curve= 0 ,0
Exp/Cntr=0.3,0.1

Type RM Length L Ch R = 1 ,16228   ,633,633,633
BEGIN DESCRIPTION:
UNT 015 in RCW 32.0
END DESCRIPTION:
XS GIS Cut Line= 3
      2012763.18     13482057.41      2012334.49     13482323.63
      2011420.84     13483383.97
#Sta/Elev= 30
  4151.3  486.62  4184.5  486.74  4207.6  484.93  4238.6  485.71  4265.5  485.05
  4271.4  485.54  4387.1  484.86  4570.1  482.71  4847.9  482.42  4901.1  483.18
  4954.3   483.7  4968.6   482.8  4982.8  479.98  4989.4  477.08  4991.8  474.65
  4992.6  473.85  5001.5  473.85  5002.4  474.65  5003.7  476.13  5011.4  479.13
  5017.9  480.51  5032.2  482.42    5075   481.9  5152.9  484.48  5202.3  485.13
  5224.2  484.73    5313  486.52  5422.8  488.91  6004.2  495.85  6055.6  495.86
#Mann= 7 ,-1 , 0
  4151.3     .05       0  4238.6      .1       0  4901.1     .07       0
  4991.8     .07       0  5002.4     .07       0  5017.9      .1       0
    5313     .05       0
Bank Sta=4991.8,5002.4
XS Rating Curve= 0 ,0
Exp/Cntr=0.3,0.1

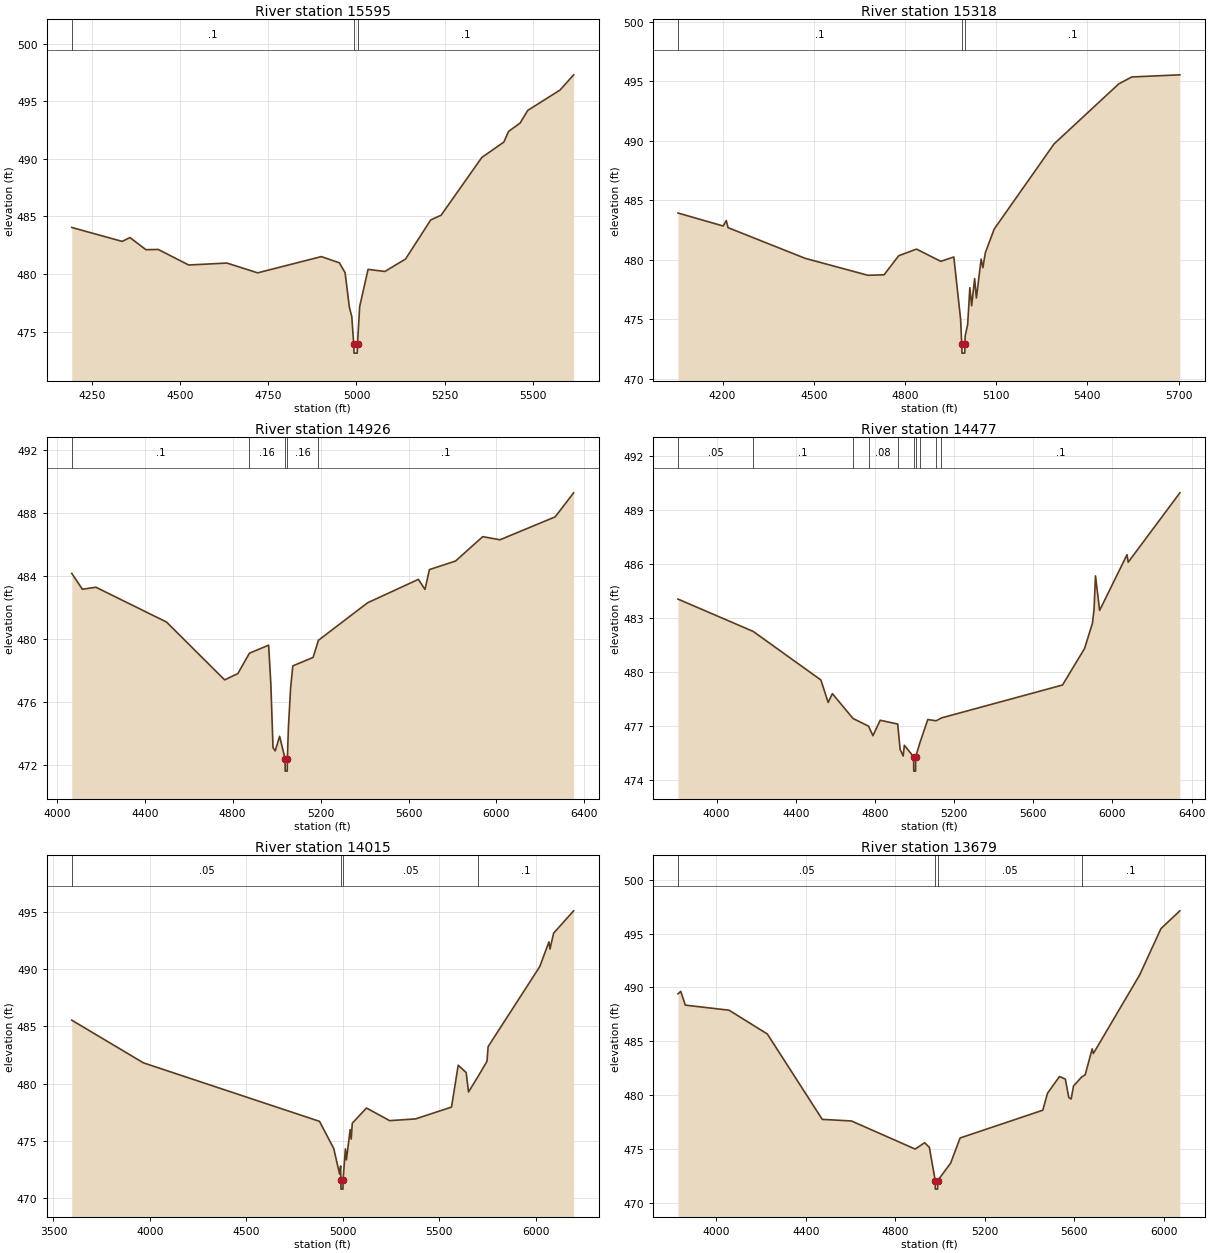
Type RM Length L Ch R = 1 ,15595   ,277,277,277
BEGIN DESCRIPTION:
UNT 015 in RCW 31.0
END DESCRIPTION:
XS GIS Cut Line= 4
      2012514.87     13482042.82      2012197.58     13481977.05
        2011825.       13482225.      2011224.98     13482475.01
#Sta/Elev= 30
  4193.6  484.04  4336.4  482.83  4358.6  483.16  4403.7  482.11  4438.6  482.13
  4524.9  480.78  4633.1  480.95  4720.2   480.1  4900.6  481.51  4951.7  480.97
  4967.9  480.11  4979.8  477.15  4986.8   476.3  4992.3  473.93  4993.1  473.13
  5002.2  473.13    5003  473.93  5009.1  477.16  5032.9   480.4  5080.6  480.22
  5139.1   481.3  5210.6   484.7  5239.8   485.1  5355.2  490.12  5417.5  491.45
    5431  492.38  5463.5   493.1  5485.2   494.2  5576.7  495.97  5615.2  497.29
#Mann= 3 ,-1 , 0
  4193.6      .1       0  4992.3     .07       0    5003      .1       0
Bank Sta=4992.3,5003
XS Rating Curve= 0 ,0
Exp/Cntr=0.3,0.1

Type RM Length L Ch R = 1 ,15318   ,392,392,392
BEGIN DESCRIPTION:
UNT 015 in RCW 30.0
END DESCRIPTION:
XS GIS Cut Line= 3
      2012511.81     13482005.93      2011836.66     13481898.71
      2011004.05     13482390.47
#Sta/Elev= 30
  4053.5  483.91  4202.1  482.82  4212.3  483.28  4218.1  482.68  4472.2   480.1
    4678  478.68  4731.3  478.72  4779.3  480.32  4837.9  480.88  4917.8  479.85
  4960.7  480.22  4982.9  475.01  4986.7  472.94  4987.5  472.14  4996.6  472.14
  4997.4  472.94  4997.8  473.54  5006.2  474.56  5013.4  477.64  5019.3  476.12
  5029.1   478.4  5034.9  476.77  5050.5  480.04  5056.3  479.32  5064.2  480.56
  5093.4  482.56  5290.5  489.72  5503.1  494.76    5546  495.34  5704.1  495.52
#Mann= 3 ,-1 , 0
  4053.5      .1       0  4986.7     .07       0  4997.4      .1       0
Bank Sta=4986.7,4997.4
XS Rating Curve= 0 ,0
Exp/Cntr=0.3,0.1

Type RM Length L Ch R = 1 ,14926   ,449,449,449
BEGIN DESCRIPTION:
Mapping XS b252af53
END DESCRIPTION:
XS GIS Cut Line= 4
      2012490.99     13481978.15      2011865.99     13481752.46
      2011258.36     13481748.99      2010251.44     13481835.79
#Sta/Elev= 30
  4068.1  484.17  4116.6  483.16    4178  483.29  4499.4  481.07  4763.6  477.39
  4823.6  477.79  4876.3  479.09  4963.6   479.6  4973.6  477.15  4983.6  473.07
  4993.6  472.87  5013.6   473.8  5038.2  472.38    5039  471.58  5048.1  471.58
  5048.9  472.38  5053.6  474.38  5063.6  476.88  5073.6  478.28  5165.8  478.82
    5190  479.91  5413.9   482.3  5644.7  483.79  5674.8  483.15  5694.9  484.41
  5814.1  484.96  5937.5  486.51  6016.1  486.31    6267  487.77  6350.9   489.3
#Mann= 5 ,-1 , 0
  4068.1      .1       0  4876.3     .16       0  5038.2     .07       0
  5048.9     .16       0    5190      .1       0
Bank Sta=5038.2,5048.9
XS Rating Curve= 0 ,0
Exp/Cntr=0.3,0.1

Type RM Length L Ch R = 1 ,14477   ,462,462,462
BEGIN DESCRIPTION:
UNT 015 in RCW 29.0
END DESCRIPTION:
XS GIS Cut Line= 4
      2012507.06     13481976.42      2011481.88     13481348.38
      2010726.67     13480957.75      2010323.68     13481225.07
#Sta/Elev= 30
  3804.6  484.06  4184.8  482.26  4526.7  479.56  4563.4  478.31  4584.7   478.8
    4689  477.42  4767.6  476.99  4789.7  476.46  4826.4  477.32  4914.8  477.11
  4927.1   475.7  4942.5  475.33  4948.4  475.93  4995.1  475.29  4995.9  474.49
  5005.1  474.49  5005.9  475.29  5027.1  476.07  5066.9  477.36  5109.2  477.29
    5136  477.45  5747.7  479.28  5859.1  481.31  5899.2  482.73  5907.1   483.5
  5914.3  485.35  5935.3  483.43  6073.7  486.53  6079.7  486.11  6340.7  489.97
#Mann= 10 ,-1 , 0
  3804.6     .05       0  4184.8      .1       0    4689     .16       0
  4767.6     .08       0  4914.8     .05       0  4995.1     .04       0
  5005.9     .05       0  5027.1     .16       0  5109.2     .05       0
    5136      .1       0
Bank Sta=4995.1,5005.9
XS Rating Curve= 0 ,0
Exp/Cntr=0.3,0.1

Type RM Length L Ch R = 1 ,14015   ,336,336,336
BEGIN DESCRIPTION:
UNT 015 in RCW 28.0
END DESCRIPTION:
XS GIS Cut Line= 4
        2012606.     13481665.21      2011512.26     13480988.14
      2010969.73      13480779.8      2010289.11     13481057.25
#Sta/Elev= 30
    3595  485.53  3966.3  481.81  4879.6  476.71  4953.4  474.35    4984  472.11
  4989.3  472.82  4990.5   471.6  4991.2   470.8  5001.3   470.8  5001.9   471.6
    5014  474.31  5019.3  473.35  5038.6  475.99    5044  475.16  5049.8  476.55
  5123.3  477.87  5243.4  476.77  5377.4  476.92  5564.2  477.95    5599   481.6
  5640.4  480.96  5652.5  479.27  5701.9  480.62  5748.4  481.95  5754.1  483.22
  6021.6  490.19  6069.6  492.35    6075  491.73  6093.7  493.11  6197.5  495.06
#Mann= 4 ,-1 , 0
    3595     .05       0  4990.5    .035       0  5001.9     .05       0
  5701.9      .1       0
Bank Sta=4990.5,5001.9
XS Rating Curve= 0 ,0
Exp/Cntr=0.3,0.1

Type RM Length L Ch R = 1 ,13679   ,416,416,416
BEGIN DESCRIPTION:
UNT 015 in RCW 27.0
END DESCRIPTION:
XS GIS Cut Line= 3
      2012406.92      13480279.8      2012101.42     13480352.71
      2010275.01       13480975.
#Sta/Elev= 30
    3829   489.4  3841.3  489.63  3861.8  488.35  4057.2  487.88  4228.4  485.67
  4473.9  477.74  4604.6  477.59  4889.4  474.98  4931.6  475.57  4952.8  475.14
  4978.8  472.06  4979.4  471.26  4989.5  471.26  4990.2  472.06  5047.8  473.67
  5090.1  476.01  5459.9  478.59    5481  480.17  5534.5  481.72  5560.6  481.48
  5576.1  479.77  5586.6  479.63  5597.2  480.84  5633.3  481.67  5649.4  481.88
  5680.7  484.29    5686  483.86    5893  491.16  5988.1  495.46  6072.6  497.11
#Mann= 4 ,-1 , 0
    3829     .05       0  4978.8    .035       0  4990.2     .05       0
  5633.3      .1       0
Bank Sta=4978.8,4990.2
XS Rating Curve= 0 ,0
Exp/Cntr=0.3,0.1

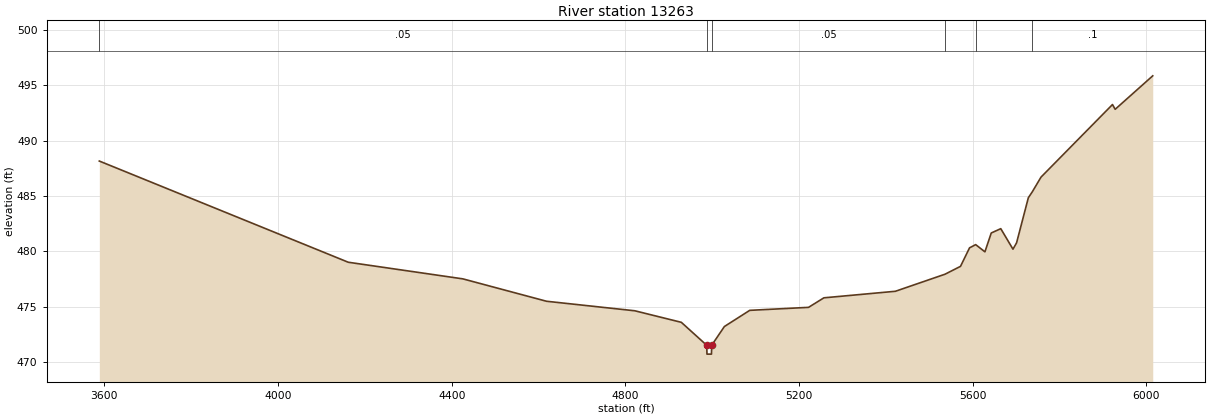
Type RM Length L Ch R = 1 ,13263   ,430,430,430
BEGIN DESCRIPTION:
UNT 015 in RCW 26.0
END DESCRIPTION:
XS GIS Cut Line= 3
        2012407.     13479765.89        2011075.       13480275.
      2010274.99     13480875.01
#Sta/Elev= 30
  3588.5  488.16  4161.8  479.03  4425.7  477.53  4618.4  475.51  4821.8  474.65
  4928.8  473.61  4987.3  471.54  4987.9  470.74  4998.2  470.74  4998.8  471.54
    5028  473.23  5086.4  474.69  5221.8  474.96  5257.2  475.82  5421.8  476.41
  5536.1  477.95  5571.8  478.66  5592.6  480.33  5606.7  480.62    5628  479.97
  5642.6  481.67  5664.5  482.06  5692.6  480.21  5700.9  480.78    5728  484.85
  5736.9  485.37  5757.2  486.71  5921.8  493.26    5928  492.83  6014.5  495.85
#Mann= 6 ,-1 , 0
  3588.5     .05       0  4987.3    .035       0  4998.8     .05       0
  5536.1      .1       0  5606.7     .05       0  5736.9      .1       0
Bank Sta=4987.3,4998.8
XS Rating Curve= 0 ,0
Exp/Cntr=0.3,0.1