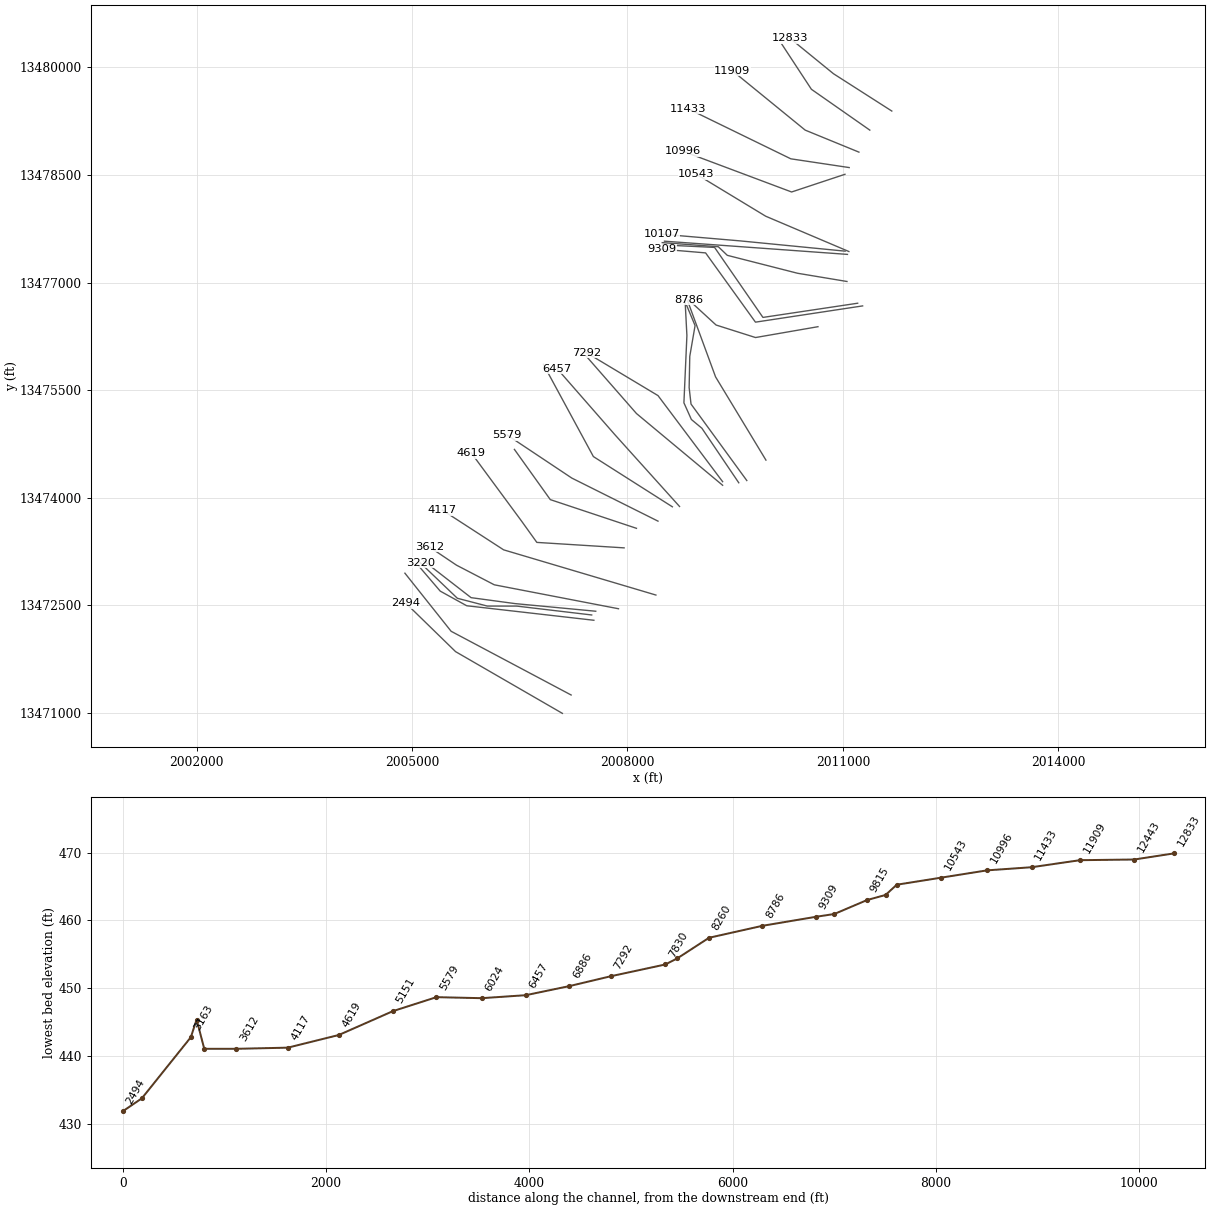
HEC-RAS study UNT 015 in RCW.prj: UNT 015 in RCW Base Level Engineering

--- UNT 015 in RCW.g01 (geometry) --- (continued)

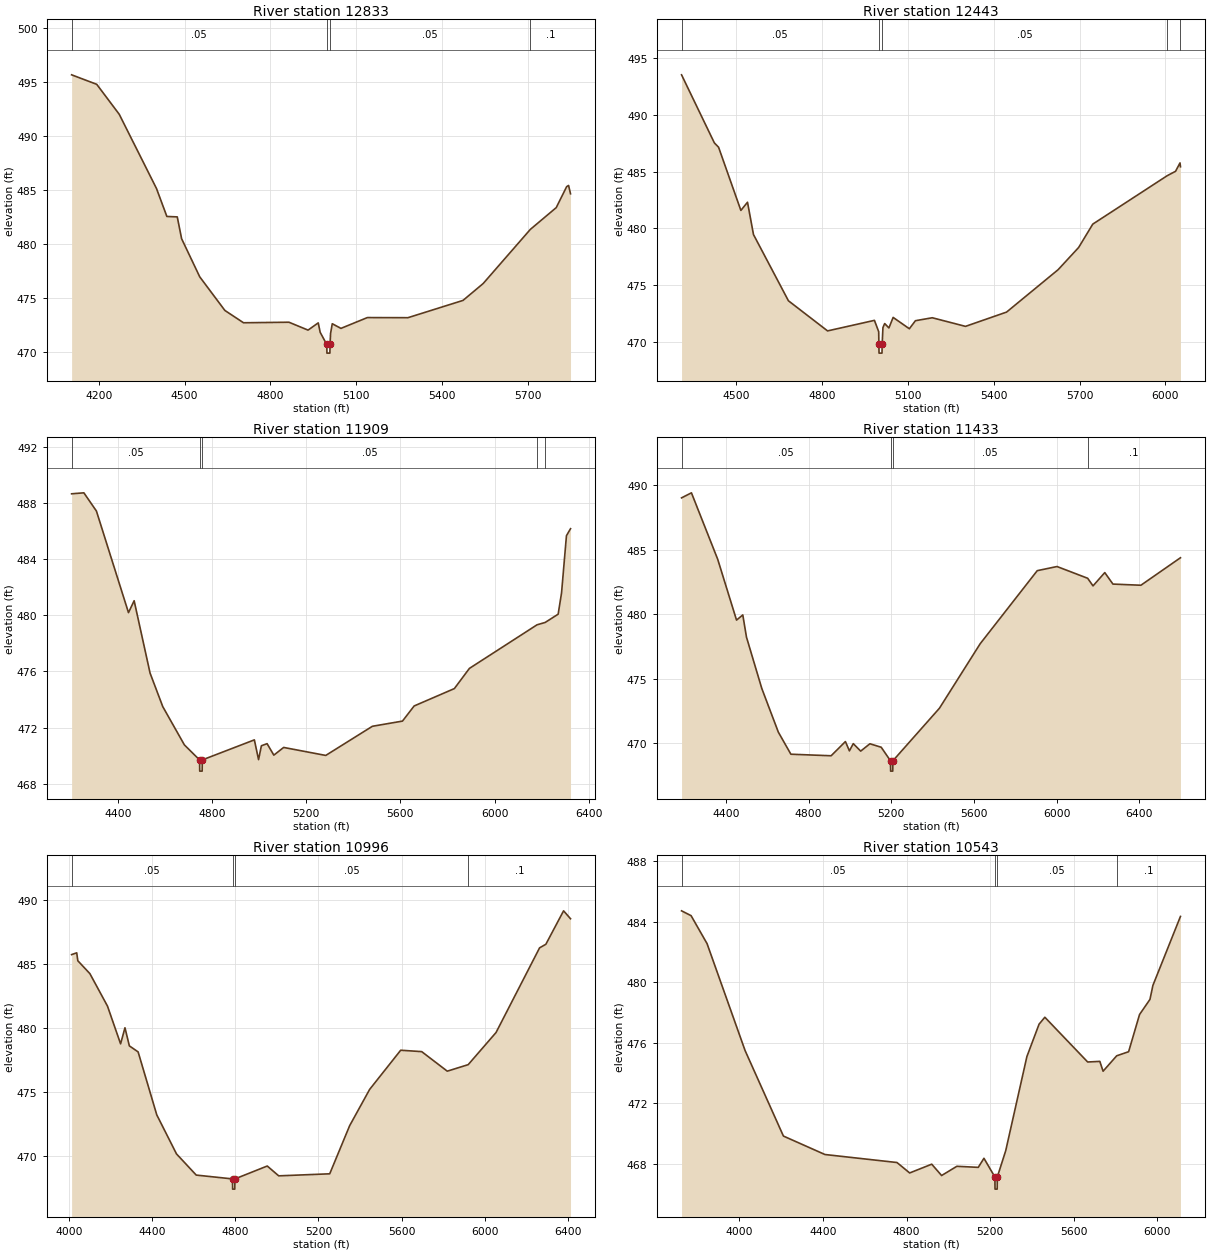
Type RM Length L Ch R = 1 ,12833   ,390,390,390
BEGIN DESCRIPTION:
UNT 015 in RCW 25.0
END DESCRIPTION:
XS GIS Cut Line= 3
      2011681.32     13479390.87      2010868.78     13479911.15
      2010264.58     13480404.24
#Sta/Elev= 30
  4105.2  495.65  4193.1  494.77  4271.7     492    4402  485.13  4438.3  482.54
  4474.7   482.5  4489.9  480.48  4553.3  476.95  4641.2  473.84  4706.4   472.7
  4865.3  472.75    4932  472.02  4967.7  472.69  4974.4  471.82  4997.5  470.69
  4998.1  469.89  5008.4  469.89    5009  470.69  5010.7  471.69  5016.7  472.61
  5047.1  472.18  5139.4  473.18  5281.4  473.17    5474  474.77  5544.4  476.33
  5709.3  481.34    5800  483.36  5836.4   485.3  5843.1  485.41  5849.9  484.64
#Mann= 4 ,-1 , 0
  4105.2     .05       0  4997.5    .035       0    5009     .05       0
  5709.3      .1       0
Bank Sta=4997.5,5009
XS Rating Curve= 0 ,0
Exp/Cntr=0.3,0.1

Type RM Length L Ch R = 1 ,12443   ,534,534,534
BEGIN DESCRIPTION:
UNT 015 in RCW 24.0
END DESCRIPTION:
XS GIS Cut Line= 3
      2011374.98     13479125.02      2010561.49     13479694.14
      2010149.59     13480322.82
#Sta/Elev= 30
    4308  493.54  4422.6  487.54  4437.5  487.15  4515.4  481.58  4538.6   482.3
  4559.5  479.45  4681.6  473.61  4818.5  470.95  4982.4  471.88  4997.3  470.88
  4997.9  469.79  4998.5  468.99  5008.8  468.99  5009.4  469.79  5012.1  471.24
  5018.2   471.6    5033  471.21  5047.8  472.14  5104.5  471.14  5125.7  471.85
  5184.7  472.11  5300.8  471.35  5444.4  472.61  5624.6  476.35  5696.4  478.31
  5745.8  480.37  6005.9  484.64  6035.2  485.03  6050.8  485.77  6052.4  485.43
#Mann= 5 ,-1 , 0
    4308     .05       0  4997.9    .035       0  5009.4     .05       0
  6005.9      .1       0  6050.8     .05       0
Bank Sta=4997.9,5009.4
XS Rating Curve= 0 ,0
Exp/Cntr=0.3,0.1

Type RM Length L Ch R = 1 ,11909   ,476,476,476
BEGIN DESCRIPTION:
UNT 015 in RCW 23.0
END DESCRIPTION:
XS GIS Cut Line= 3
      2011223.35     13478818.28        2010475.       13479125.
      2009459.71     13479953.51
#Sta/Elev= 30
  4203.7  488.68  4255.8  488.75  4309.1  487.45  4445.3   480.2  4469.3  481.05
  4536.9  475.89    4591  473.49  4682.8  470.76  4747.3  469.69  4747.9  468.89
  4758.2  468.89  4758.8  469.69    4980  471.12  4997.8  469.71  5009.8   470.7
    5034  470.85  5062.7  470.03  5104.4  470.58  5283.2  470.01  5481.3  472.09
  5609.1  472.46  5658.7  473.54  5829.5  474.78  5893.4  476.22  6180.5  479.33
  6215.3   479.5  6270.4  480.09  6284.8  481.61  6305.6  485.69  6322.9  486.19
#Mann= 5 ,-1 , 0
  4203.7     .05       0  4747.3    .035       0  4758.8     .05       0
  6180.5      .1       0  6215.3     .05       0
Bank Sta=4747.3,4758.8
XS Rating Curve= 0 ,0
Exp/Cntr=0.3,0.1

Type RM Length L Ch R = 1 ,11433   ,437,437,437
BEGIN DESCRIPTION:
UNT 015 in RCW 22.0
END DESCRIPTION:
XS GIS Cut Line= 3
      2011087.92       13478603.        2010275.       13478725.
      2008844.92     13479422.43
#Sta/Elev= 30
  4185.8  489.02  4233.6  489.41  4360.7  484.26  4451.7  479.55    4482  479.95
  4499.8  478.23    4574  474.25  4653.9  470.87  4714.6  469.16  4909.3  469.04
  4978.3  470.14  4997.7  469.42  5016.3  469.98  5052.3   469.4  5096.8  469.97
  5151.5   469.7  5196.4  468.65    5197  467.85  5207.3  467.85  5207.9  468.65
    5433  472.72  5630.2  477.72  5906.2  483.38  6001.9   483.7  6150.1  482.79
    6176   482.2  6232.8  483.23  6272.3  482.34  6407.5  482.25  6598.9  484.38
#Mann= 4 ,-1 , 0
  4185.8     .05       0  5196.4    .035       0  5207.9     .05       0
  6150.1      .1       0
Bank Sta=5196.4,5207.9
XS Rating Curve= 0 ,0
Exp/Cntr=0.3,0.1

Type RM Length L Ch R = 1 ,10996   ,453,453,453
BEGIN DESCRIPTION:
UNT 015 in RCW 21.0
END DESCRIPTION:
XS GIS Cut Line= 3
      2011028.92     13478509.24      2010285.88     13478262.72
      2008769.23     13478831.89
#Sta/Elev= 30
    4011  485.76  4035.6   485.9  4040.9  485.28    4099  484.27  4183.7  481.73
  4246.9  478.77    4268  480.03  4289.1  478.61  4331.3  478.14  4421.1  473.21
  4516.1  470.15  4611.2  468.49  4785.9  468.19  4786.5  467.39  4796.8  467.39
  4797.4  468.19  4953.3   469.2  5008.4  468.43  5254.1  468.59  5350.1  472.36
  5446.3   475.2  5595.9  478.27  5697.1  478.16  5820.2  476.63    5921  477.14
  6055.2  479.66  6264.8  486.29    6295  486.57  6380.4  489.19  6413.8  488.57
#Mann= 4 ,-1 , 0
    4011     .05       0  4785.9    .035       0  4797.4     .05       0
    5921      .1       0
Bank Sta=4785.9,4797.4
XS Rating Curve= 0 ,0
Exp/Cntr=0.3,0.1

Type RM Length L Ch R = 1 ,10543   ,436,436,436
BEGIN DESCRIPTION:
UNT 015 in RCW 20.0
END DESCRIPTION:
XS GIS Cut Line= 3
      2011083.65     13477432.85        2009925.       13477925.
      2008960.16     13478510.05
#Sta/Elev= 30
  3723.2  484.72  3768.8   484.4  3845.2  482.55  4027.1  475.48  4210.6  469.82
  4409.1   468.6  4753.9  468.07  4814.7  467.38  4920.2  467.96  4967.5  467.21
  5040.5  467.82  5142.9  467.75  5170.1  468.35  5222.5  467.11  5223.1  466.31
  5233.4  466.31    5234  467.11  5274.4  468.86  5375.6  475.08  5433.8  477.22
  5461.5  477.68  5666.4  474.72  5724.6  474.76  5740.1  474.11  5805.3  475.13
  5862.3   475.4  5914.6  477.86  5964.4  478.86  5978.6  479.79  6110.4  484.35
#Mann= 4 ,-1 , 0
  3723.2     .05       0  5222.5    .035       0    5234     .05       0
  5805.3      .1       0
Bank Sta=5222.5,5234
XS Rating Curve= 0 ,0
Exp/Cntr=0.3,0.1

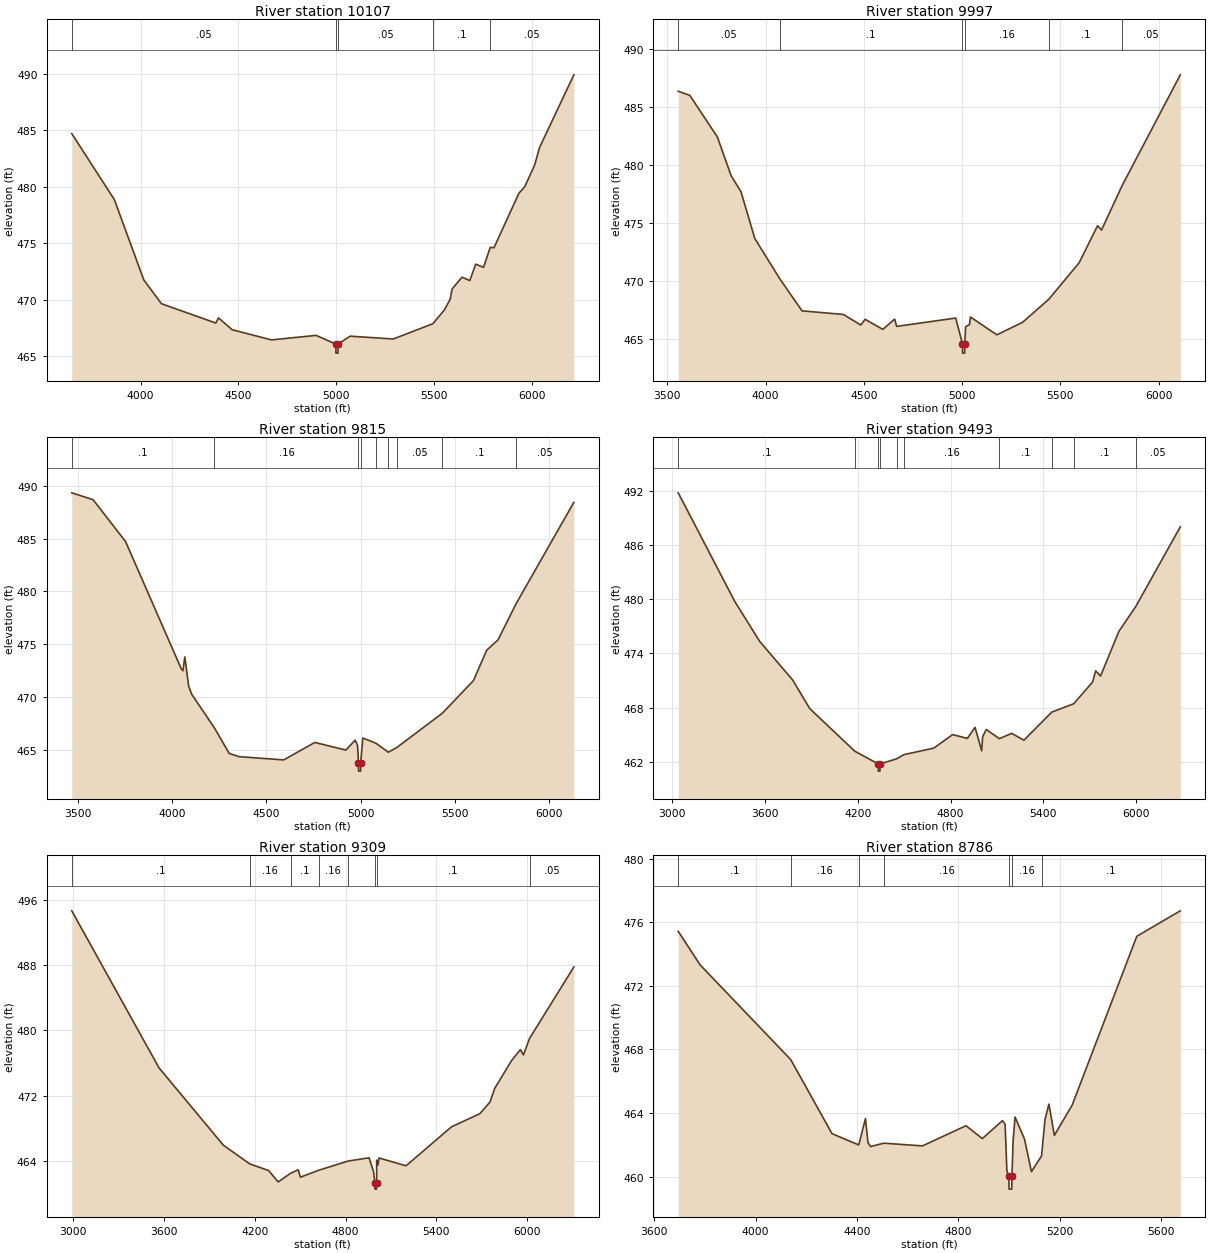
Type RM Length L Ch R = 1 ,10107   ,110,110,110
BEGIN DESCRIPTION:
UNT 015 in RCW 19.0
END DESCRIPTION:
XS GIS Cut Line= 3
      2011031.58     13477438.06        2009568.     13477581.29
      2008474.98       13477675.
#Sta/Elev= 30
    3648  484.69  3865.6  478.86  4016.3  471.75  4106.8  469.64  4384.8  467.93
  4398.1  468.39  4468.5  467.34  4669.4  466.44  4897.7  466.84  4998.5  466.07
  4999.1  465.27  5009.5  465.27  5010.1  466.07  5071.3  466.77  5292.2  466.52
  5494.5  467.87  5553.2  469.08  5583.3  470.04  5593.3  470.95  5643.5  471.99
  5683.6  471.69  5713.7  473.14  5753.9  472.86  5787.9  474.62  5807.5   474.6
  5934.6  479.41  5964.7     480  6014.8  481.89    6040  483.45  6215.6  489.89
#Mann= 5 ,-1 , 0
    3648     .05       0  4998.5    .035       0  5010.1     .05       0
  5494.5      .1       0  5787.9     .05       0
Bank Sta=4998.5,5010.1
XS Rating Curve= 0 ,0
Exp/Cntr=0.3,0.1

Type RM Length L Ch R = 1 ,9997    ,182,182,182
BEGIN DESCRIPTION:
Mapping XS dd292157
END DESCRIPTION:
XS GIS Cut Line= 2
      2011063.65     13477392.93      2008515.08     13477576.95
#Sta/Elev= 30
  3555.8  486.38  3614.6  486.03    3755  482.43  3825.1  479.08  3875.3   477.7
  3945.5  473.66  4072.3  470.19  4186.1  467.41  4396.6   467.1  4484.5  466.19
  4506.9  466.68  4597.2  465.81  4657.3   466.7  4667.3  466.07  4968.1  466.79
  5002.4  464.56    5003  463.76  5013.4  463.76    5014  464.56  5018.2  466.04
  5037.9  466.22  5042.9  466.88  5177.5  465.34    5309  466.43  5442.1  468.42
  5596.3  471.57    5690  474.77    5710  474.39  5814.3  478.21    6111   487.8
#Mann= 6 ,-1 , 0
  3555.8     .05       0  4072.3      .1       0  5002.4     .07       0
    5014     .16       0  5442.1      .1       0  5814.3     .05       0
Bank Sta=5002.4,5014
XS Rating Curve= 0 ,0
Exp/Cntr=0.3,0.1

Type RM Length L Ch R = 1 ,9815    ,322,322,322
BEGIN DESCRIPTION:
Mapping XS 8f79f321
END DESCRIPTION:
XS GIS Cut Line= 5
       2011056.7     13477015.32      2010369.21      13477129.9
      2009390.04      13477379.9      2009265.04      13477499.7
      2008483.83     13477556.99
#Sta/Elev= 30
  3466.9  489.32  3580.1  488.67  3752.5  484.71  4047.2  472.71  4056.6   472.5
  4066.8  473.81    4087  471.05  4102.9  470.29  4224.1  467.09  4302.4  464.68
    4354  464.38  4591.4  464.07  4756.5  465.72  4921.6     465  4970.4  465.94
  4983.6  465.42    4988  463.81  4988.6  463.01  4999.1  463.01  4999.7  463.81
  5011.3  466.14  5080.5  465.65  5146.6   464.8  5191.9  465.25  5433.6  468.49
  5598.3  471.57  5668.5  474.44  5728.6  475.42  5825.6  478.87  6130.9  488.42
#Mann= 9 ,-1 , 0
  3466.9      .1       0  4224.1     .16       0    4988     .07       0
  4999.7     .16       0  5080.5      .1       0  5146.6     .16       0
  5191.9     .05       0  5433.6      .1       0  5825.6     .05       0
Bank Sta=4988,4999.7
XS Rating Curve= 0 ,0
Exp/Cntr=0.3,0.1

Type RM Length L Ch R = 1 ,9493    ,184,184,184
BEGIN DESCRIPTION:
UNT 015 in RCW 18.0
END DESCRIPTION:
XS GIS Cut Line= 4
      2011206.06     13476712.38      2009886.57     13476514.45
      2009212.96     13477490.15      2008488.67      13477524.8
#Sta/Elev= 30
  3040.1  491.82  3405.2  479.78    3567  475.33  3779.3  471.07  3890.6  467.88
  4181.3  463.16  4332.8  461.75  4333.4  460.95  4344.1  460.95  4344.6  461.75
    4451  462.31  4498.7  462.78  4691.1   463.5  4813.4     465  4908.8  464.58
  4958.3  465.81  5001.4   463.2  5007.5  464.76  5031.1  465.57  5115.5  464.55
  5195.4  465.14  5274.2  464.38  5454.6   467.5  5595.6  468.42  5718.1  470.83
  5738.1  472.07  5769.7   471.5  5888.3  476.46    5998  479.23  6285.1  488.05
#Mann= 10 ,-1 , 0
  3040.1      .1       0  4181.3     .16       0  4332.8     .07       0
  4344.6     .16       0    4451      .1       0  4498.7     .16       0
  5115.5      .1       0  5454.6     .05       0  5595.6      .1       0
    5998     .05       0
Bank Sta=4332.8,4344.6
XS Rating Curve= 0 ,0
Exp/Cntr=0.3,0.1

Type RM Length L Ch R = 1 ,9309    ,523,523,523
BEGIN DESCRIPTION:
UNT 015 in RCW 17.0
END DESCRIPTION:
XS GIS Cut Line= 4
      2011275.01       13476675.      2009782.41     13476448.48
      2009087.96     13477413.76      2008473.38     13477465.84
#Sta/Elev= 30
  2992.3  494.63  3568.8  475.38  3993.6  465.91    4168  463.62    4292  462.81
  4355.6  461.41  4436.9  462.47    4488   462.9    4502  461.99  4622.2  462.84
  4817.2  463.97  4955.5  464.37  4984.9  462.69  4993.8  461.33  4994.3  460.53
    5005  460.53  5005.6  461.33  5005.8  464.09  5014.4  463.49  5020.5  464.35
  5199.9  463.39  5500.5  468.17  5687.1  469.77  5754.3   471.2  5784.4  472.84
  5894.8  476.23    5955  477.63  5975.1  476.97  6015.2  478.99  6307.9  487.75
#Mann= 8 ,-1 , 0
  2992.3      .1       0    4168     .16       0  4436.9      .1       0
  4622.2     .16       0  4817.2      .1       0  4993.8     .07       0
  5005.6      .1       0  6015.2     .05       0
Bank Sta=4993.8,5005.6
XS Rating Curve= 0 ,0
Exp/Cntr=0.3,0.1

Type RM Length L Ch R = 1 ,8786    ,526,526,526
BEGIN DESCRIPTION:
UNT 015 in RCW 16.0
END DESCRIPTION:
XS GIS Cut Line= 4
      2010653.08     13476385.11      2009783.27     13476234.07
      2009233.79     13476408.55      2008849.16     13476761.99
#Sta/Elev= 30
  3694.9  475.43  3781.2  473.32  4138.9  467.36  4301.9   462.7  4407.4  461.99
  4433.9  463.65    4444  462.13  4454.2  461.89  4506.6   462.1    4659  461.93
  4830.8   463.2  4895.3  462.39  4974.6  463.52  4985.1  463.29  4992.1  460.35
  5000.2  460.01  5000.7  459.21  5011.4  459.21    5012  460.01  5016.6  462.23
  5024.3  463.75  5061.8  462.35  5088.9  460.31  5128.8  461.29  5142.5  463.58
  5157.9  464.56  5179.5  462.59  5249.8   464.5    5505  475.12  5676.6  476.72
#Mann= 7 ,-1 , 0
  3694.9      .1       0  4138.9     .16       0  4407.4      .1       0
  4506.6     .16       0  5000.2     .07       0    5012     .16       0
  5128.8      .1       0
Bank Sta=5000.2,5012
XS Rating Curve= 0 ,0
Exp/Cntr=0.3,0.1

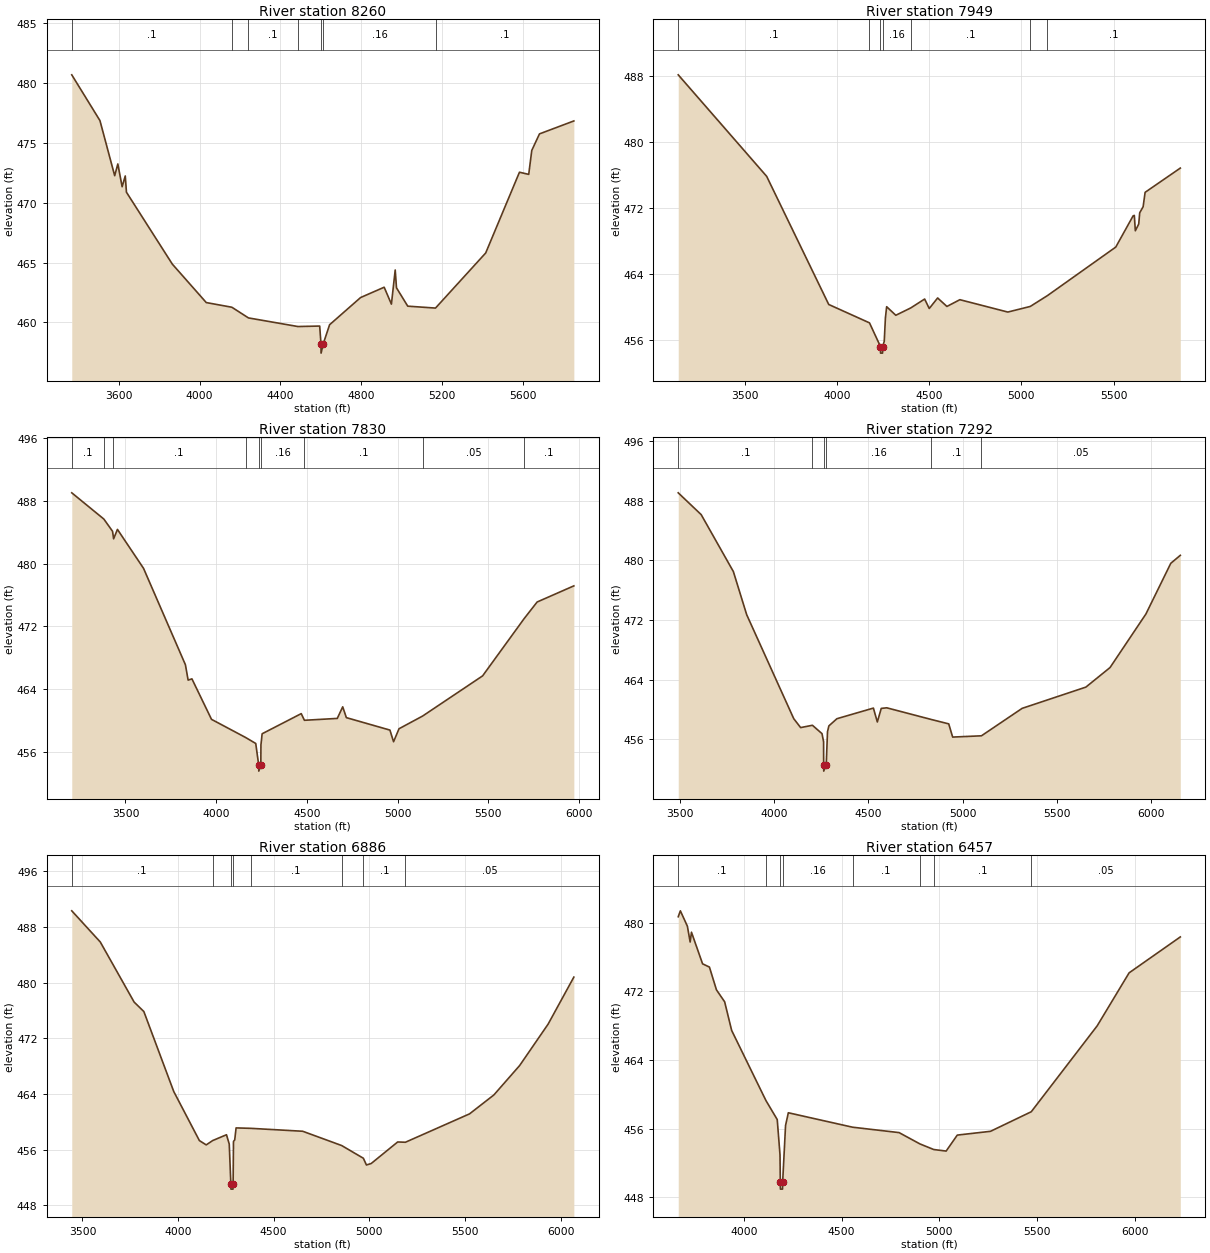
Type RM Length L Ch R = 1 ,8260    ,311,311,311
BEGIN DESCRIPTION:
UNT 015 in RCW 15.0
END DESCRIPTION:
XS GIS Cut Line= 3
      2009928.25     13474525.72      2009226.85     13475685.46
      2008837.97     13476744.47
#Sta/Elev= 30
  3367.9  480.67  3507.3  476.85  3580.2  472.25  3595.7  473.23    3617  471.33
  3632.5  472.23  3638.4  470.87  3865.3  464.87  4033.2  461.66  4159.8  461.27
  4241.8  460.38  4486.4  459.66  4594.2   459.7  4600.5  458.24  4601.1  457.44
  4612.3  458.24  4643.3  459.81  4796.6  462.08  4913.2  462.94    4949  461.53
  4967.8  464.38  4974.1  462.89  5029.8  461.36  5167.1   461.2  5415.4   465.8
  5582.4  472.54  5628.2  472.36  5643.3  474.36  5681.5  475.74  5851.4  476.82
#Mann= 7 ,-1 , 0
  3367.9      .1       0  4159.8     .12       0  4241.8      .1       0
  4486.4     .16       0  4600.5     .07       0  4612.3     .16       0
  5167.1      .1       0
Bank Sta=4600.5,4612.3
XS Rating Curve= 0 ,0
Exp/Cntr=0.3,0.1

Type RM Length L Ch R = 1 ,7949    ,119,119,119
BEGIN DESCRIPTION:
Mapping XS 5a6e885c
END DESCRIPTION:
XS GIS Cut Line= 6
      2009661.77     13474240.98      2008884.84     13475306.99
      2008858.79     13475537.02      2008867.47     13475971.05
      2008941.26     13476400.74      2008824.67      13476681.4
#Sta/Elev= 30
  3137.6  488.16  3617.5  475.85  3954.3  460.31  4175.5  458.08    4235  455.21
  4235.6  454.41  4246.3  454.41  4246.8  455.21  4255.6  455.84  4261.8  458.65
  4268.6  460.04  4318.2     459  4399.4  459.89  4474.8  460.97  4499.8  459.82
  4545.3   461.1  4595.6  460.07    4666  460.89  4926.2  459.39  5047.8  460.07
  5140.9  461.38  5511.9  467.27  5606.2  471.06  5612.7  471.11  5618.1  469.25
  5636.5  470.06  5641.9  471.43  5660.4  472.16  5671.2  473.91  5862.2  476.85
#Mann= 7 ,-1 , 0
  3137.6      .1       0  4175.5     .16       0    4235     .07       0
  4246.8     .16       0  4399.4      .1       0  5047.8     .05       0
  5140.9      .1       0
Bank Sta=4235,4246.8
XS Rating Curve= 0 ,0
Exp/Cntr=0.3,0.1

Type RM Length L Ch R = 1 ,7830    ,538,538,538
BEGIN DESCRIPTION:
UNT 015 in RCW 14.0
END DESCRIPTION:
XS GIS Cut Line= 6
      2009549.77     13474209.77      2009035.88     13474970.18
      2008890.04     13475091.71      2008785.88     13475324.35
      2008827.54     13476261.85      2008803.24     13476727.13
#Sta/Elev= 30
  3204.2  489.03    3381  485.68  3428.9  484.12  3434.9  483.16  3455.9  484.36
  3599.7  479.39  3830.5  467.08  3845.4  465.12  3866.4  465.28  3974.3  460.11
  4161.8   457.8  4218.1  457.03  4234.3   454.3  4234.9   453.5  4246.1   454.3
  4246.7  456.84  4253.3  458.27  4468.8  460.84  4486.3  459.99  4667.4  460.23
  4697.4  461.71  4717.4  460.33  4957.6  458.74  4977.6  457.25  5007.6  458.91
  5137.6  460.53  5468.3  465.66  5696.9  472.96  5768.7  475.09  5971.1  477.15
#Mann= 9 ,-1 , 0
  3204.2      .1       0    3381     .08       0  3428.9      .1       0
  4161.8     .16       0  4234.3     .07       0  4246.1     .16       0
  4486.3      .1       0  5137.6     .05       0  5696.9      .1       0
Bank Sta=4234.3,4246.1
XS Rating Curve= 0 ,0
Exp/Cntr=0.3,0.1

Type RM Length L Ch R = 1 ,7292    ,406,406,406
BEGIN DESCRIPTION:
UNT 015 in RCW 13.0
END DESCRIPTION:
XS GIS Cut Line= 3
      2009324.99     13474225.01        2008425.       13475425.
      2007424.98     13476025.01
#Sta/Elev= 30
    3490  489.03  3611.9  486.11  3782.7  478.49  3853.5  472.71  4103.5  458.78
    4140  457.59  4202.5   457.9  4253.5  456.78  4261.9   455.7  4262.2  452.56
  4262.8  451.76    4274  452.56  4276.4  452.93  4282.7  457.04    4290  457.82
  4332.7  458.78  4526.4   460.2  4547.3  458.34  4568.1  460.16  4597.3  460.24
  4834.7  458.67  4926.4  458.09  4947.3  456.32  5100.2  456.49  5316.5  460.17
  5654.7  463.01    5783  465.63  5973.5   472.8  6105.6  479.59  6156.2  480.66
#Mann= 6 ,-1 , 0
    3490      .1       0  4202.5     .16       0  4262.2     .07       0
    4274     .16       0  4834.7      .1       0  5100.2     .05       0
Bank Sta=4262.2,4274
XS Rating Curve= 0 ,0
Exp/Cntr=0.3,0.1

Type RM Length L Ch R = 1 ,6886    ,429,429,429
BEGIN DESCRIPTION:
UNT 015 in RCW 12.0
END DESCRIPTION:
XS GIS Cut Line= 3
      2009325.02     13474174.98        2008125.       13475175.
        2007425.     13475975.01
#Sta/Elev= 30
  3444.3  490.32  3593.4  485.84  3770.4   477.2  3821.2  475.84  3977.4  464.35
  4111.5  457.29  4147.3  456.67  4180.9  457.29  4253.3  458.13  4267.7  456.78
    4276  451.11  4276.6  450.31  4287.4  450.31  4287.9  451.11  4289.8  457.16
  4296.3  457.39  4303.5  459.11  4380.1  459.05  4651.7  458.63  4855.2  456.58
  4968.9  454.75  4984.9  453.78  5009.7  453.99  5148.3  457.09  5188.8  457.05
  5524.1  461.13  5651.3  463.85  5786.1  468.08  5935.1  474.04  6069.4  480.79
#Mann= 8 ,-1 , 0
  3444.3      .1       0  4180.9     .16       0    4276     .07       0
  4287.9     .16       0  4380.1      .1       0  4855.2     .16       0
  4968.9      .1       0  5188.8     .05       0
Bank Sta=4276,4287.9
XS Rating Curve= 0 ,0
Exp/Cntr=0.3,0.1

Type RM Length L Ch R = 1 ,6457    ,433,433,433
BEGIN DESCRIPTION:
UNT 015 in RCW 11.0
END DESCRIPTION:
XS GIS Cut Line= 3
      2008724.99     13473879.35        2007825.     13474879.34
      2007020.11     13475800.08
#Sta/Elev= 30
  3663.9  480.68  3674.8  481.37  3710.7  479.58  3724.9  477.74  3731.6  478.88
  3788.4   475.2  3823.5  474.82  3859.4  472.17  3901.3  470.78  3937.1  467.45
  4112.6  459.28  4170.3  457.07  4184.5  452.96  4186.1  449.77  4186.6  448.97
  4197.4  448.97    4198  449.77  4212.9  456.38  4227.1  457.86  4555.4  456.18
  4793.7  455.55  4899.6  454.24  4970.9  453.58  5034.4   453.4  5091.3  455.26
  5261.2   455.7  5469.9  457.98    5807  467.98  5970.3  474.15  6232.2  478.33
#Mann= 8 ,-1 , 0
  3663.9      .1       0  4112.6     .16       0  4186.1     .07       0
    4198     .16       0  4555.4      .1       0  4899.6     .16       0
  4970.9      .1       0  5469.9     .05       0
Bank Sta=4186.1,4198
XS Rating Curve= 0 ,0
Exp/Cntr=0.3,0.1

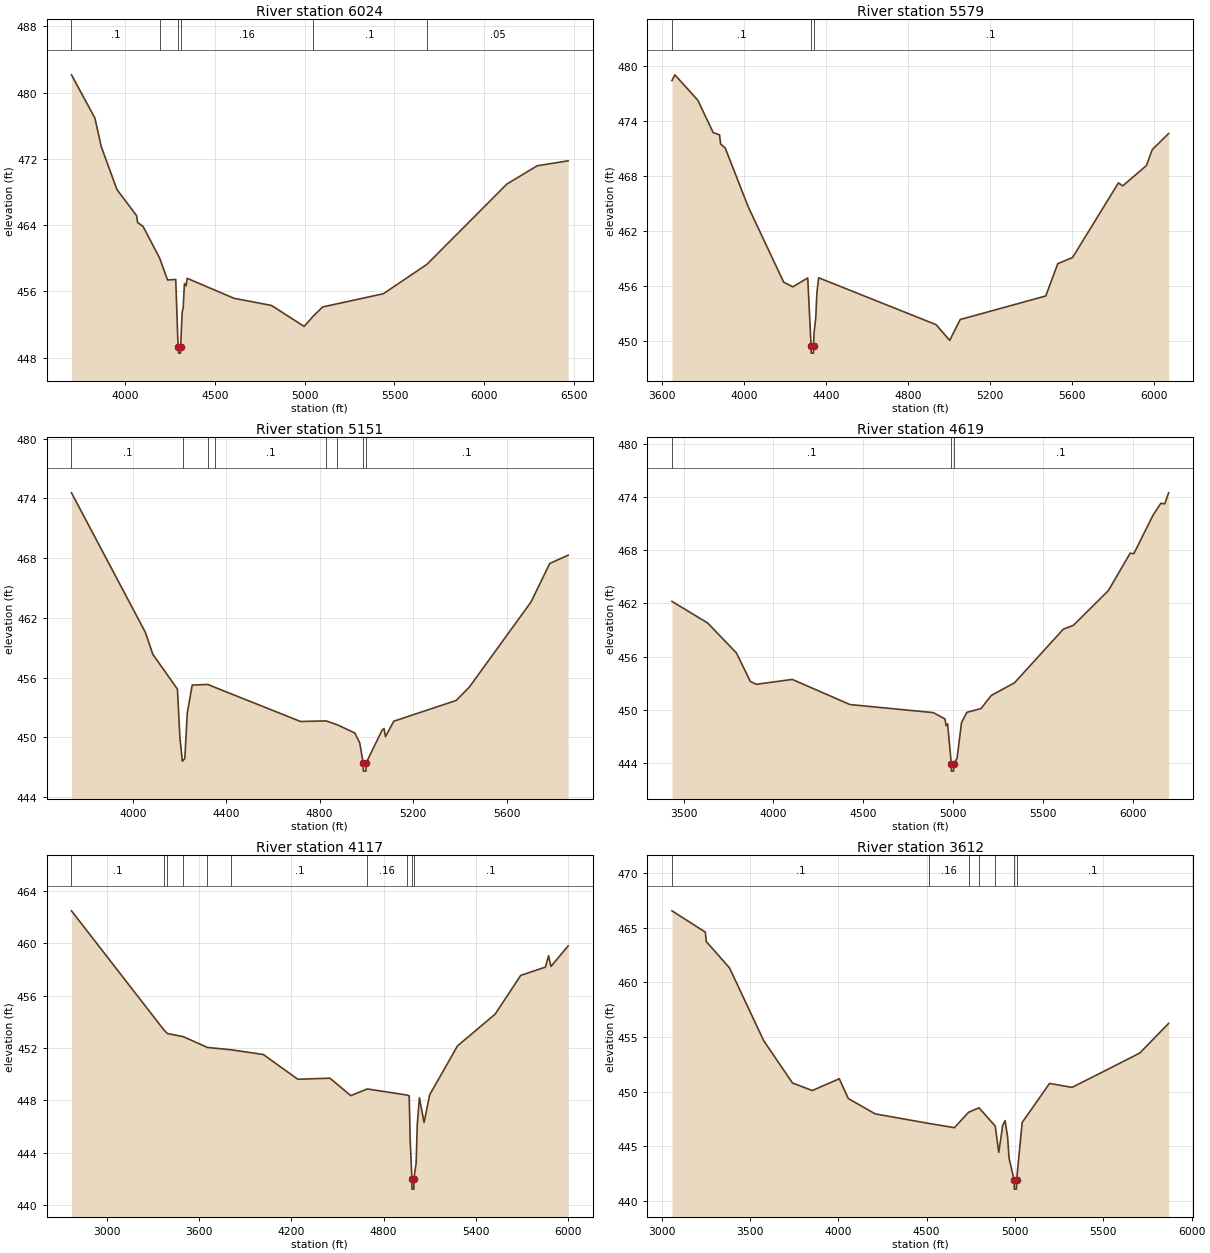
Type RM Length L Ch R = 1 ,6024    ,445,445,445
BEGIN DESCRIPTION:
UNT 015 in RCW 10.0
END DESCRIPTION:
XS GIS Cut Line= 3
        2008625.       13473875.        2007525.       13474575.
       2006828.4      13475861.7
#Sta/Elev= 30
  3700.7  482.16  3831.1  476.93  3866.6  473.48  3953.8   468.3  4063.1  465.15
    4069  464.32  4099.5  463.84  4191.6  460.02  4235.8  457.37  4281.5  457.43
  4293.3     450  4296.7  449.33  4297.3  448.53  4308.1  448.53  4308.6  449.33
  4317.1  453.42    4323  454.02  4329.8  456.93  4339.1  456.67    4345  457.57
  4605.8  455.16  4814.9  454.29  4996.9  451.76  5046.7  452.98  5100.1  454.11
  5438.7  455.71  5680.4  459.25  6126.4  468.96  6295.7  471.17  6467.7  471.77
#Mann= 6 ,-1 , 0
  3700.7      .1       0  4191.6     .16       0  4296.7     .07       0
  4308.6     .16       0  5046.7      .1       0  5680.4     .05       0
Bank Sta=4296.7,4308.6
XS Rating Curve= 0 ,0
Exp/Cntr=0.3,0.1

Type RM Length L Ch R = 1 ,5579    ,428,428,428
BEGIN DESCRIPTION:
UNT 015 in RCW 9.0
END DESCRIPTION:
XS GIS Cut Line= 3
      2008424.96     13473675.02        2007225.       13474275.
      2006324.97     13474875.02
#Sta/Elev= 30
  3648.5  478.44  3662.4  479.07  3774.2  476.31  3849.7  472.76  3880.4  472.52
    3886  471.51  3908.4  471.07  4020.2  464.67  4193.5  456.43  4238.2  455.92
  4310.9  456.89  4327.2  449.48  4327.7  448.68  4338.7  448.68  4339.2  449.48
  4341.6  450.86    4350  452.53  4355.6  455.27    4364  456.91    4937  451.79
  5003.6  450.07  5054.7  452.35  5472.3  454.92  5530.9  458.45    5603  459.12
  5826.9  467.27  5847.9  466.94  5963.6  469.17  5992.1  470.91  6071.8  472.66
#Mann= 3 ,-1 , 0
  3648.5      .1       0  4327.2     .07       0  4339.2      .1       0
Bank Sta=4327.2,4339.2
XS Rating Curve= 0 ,0
Exp/Cntr=0.3,0.1

Type RM Length L Ch R = 1 ,5151    ,532,532,532
BEGIN DESCRIPTION:
UNT 015 in RCW 8.0
END DESCRIPTION:
XS GIS Cut Line= 3
      2008125.03     13473574.99        2006925.       13473975.
      2006424.99     13474675.02
#Sta/Elev= 30
  3738.1  474.55  4054.4  460.54    4086  458.35  4191.4  454.85  4201.9  450.05
  4212.5  447.62  4216.7  447.72    4223  447.87  4233.6  452.46  4254.6  455.26
  4321.4  455.32  4352.5  455.02  4718.4   451.6  4827.9  451.66  4876.3  451.26
  4950.3  450.45  4971.4  449.47  4986.5  447.42    4987  446.62    4998  446.62
  4998.5  447.42  5066.9  450.72  5075.6   450.9  5081.7  450.08  5117.3  451.63
    5384  453.71  5440.5  455.05  5704.8  463.61  5784.6  467.46  5863.3  468.29
#Mann= 8 ,-1 , 0
  3738.1      .1       0  4216.7     .12       0  4321.4     .07       0
  4352.5      .1       0  4827.9     .12       0  4876.3      .1       0
  4986.5     .07       0  4998.5      .1       0
Bank Sta=4986.5,4998.5
XS Rating Curve= 0 ,0
Exp/Cntr=0.3,0.1

Type RM Length L Ch R = 1 ,4619    ,502,502,502
BEGIN DESCRIPTION:
UNT 015 in RCW 7.0
END DESCRIPTION:
XS GIS Cut Line= 4
      2007952.94     13473302.63      2006737.51      13473378.8
        2006525.       13473675.        2005825.       13474625.
#Sta/Elev= 30
  3435.8  462.22  3634.1  459.79  3794.4  456.41  3871.5  453.21  3904.7  452.88
    4105  453.43  4425.7   450.6  4889.2  449.69  4954.3  448.98  4960.4  448.22
  4968.9  448.42  4989.5   443.9  4990.1   443.1  5002.1   443.1  5002.7   443.9
  5021.3  444.54  5046.3  448.57  5075.6  449.72  5154.8  450.15  5211.4  451.62
  5340.9  453.05  5612.4  459.09  5668.7  459.53  5862.8  463.43  5984.2  467.65
    6005   467.6  6111.5  471.94  6155.4  473.28  6176.2   473.2  6198.2  474.45
#Mann= 3 ,-1 , 0
  3435.8      .1       0  4989.5     .07       0  5002.7      .1       0
Bank Sta=4989.5,5002.7
XS Rating Curve= 0 ,0
Exp/Cntr=0.3,0.1

Type RM Length L Ch R = 1 ,4117    ,505,505,505
BEGIN DESCRIPTION:
UNT 015 in RCW 6.0
END DESCRIPTION:
XS GIS Cut Line= 3
      2008395.64     13472645.07        2006275.       13473275.
      2005422.08     13473828.33
#Sta/Elev= 30
  2770.8  462.48  3373.2  453.36  3394.7  453.11  3498.3  452.87  3653.9  452.05
  3808.8  451.87  4017.7  451.51  4242.4  449.62    4451   449.7  4586.6  448.37
  4694.3  448.88    4953  448.41  4966.4  448.35  4972.6  445.03  4983.9  442.03
  4984.5  441.23  4996.6  441.23  4997.2  442.03  5011.7  443.25  5018.8  446.16
  5032.8  448.21  5063.1  446.31  5099.4  448.43  5280.6  452.17  5525.2  454.59
  5691.3  457.55  5851.5  458.18  5872.6  459.05  5887.8  458.23  5999.7   459.8
#Mann= 10 ,-1 , 0
  2770.8      .1       0  3373.2     .07       0  3394.7     .12       0
  3498.3     .07       0  3653.9     .12       0  3808.8      .1       0
  4694.3     .16       0    4953      .1       0  4983.9     .07       0
  4997.2      .1       0
Bank Sta=4983.9,4997.2
XS Rating Curve= 0 ,0
Exp/Cntr=0.3,0.1

Type RM Length L Ch R = 1 ,3612    ,317,317,317
BEGIN DESCRIPTION:
UNT 015 in RCW 5.0
END DESCRIPTION:
XS GIS Cut Line= 4
      2007874.82      13472454.1      2006144.93     13472787.69
      2005617.84     13473061.74       2005239.9      13473316.1
#Sta/Elev= 30
  3058.2  466.55  3247.1   464.6  3252.2  463.74  3383.9  461.32  3577.4  454.66
  3740.4  450.78  3852.4  450.09  4005.2  451.17  4056.1  449.36  4208.8  447.95
  4511.6  447.08  4656.9  446.69  4737.2   448.1  4796.1  448.51  4888.2  446.83
    4908  444.42  4930.2  446.89  4943.9  447.33  4957.9  445.88  4966.4  443.89
  4995.5  441.86  4996.1  441.06  5008.2  441.06  5008.8  441.86  5040.7  447.17
  5195.5  450.74  5322.5  450.38  5489.8  451.74  5706.8  453.53  5869.6  456.24
#Mann= 7 ,-1 , 0
  3058.2      .1       0  4511.6     .16       0  4737.2      .1       0
  4796.1     .12       0  4888.2      .1       0  4995.5     .07       0
  5008.8      .1       0
Bank Sta=4995.5,5008.8
XS Rating Curve= 0 ,0
Exp/Cntr=0.3,0.1

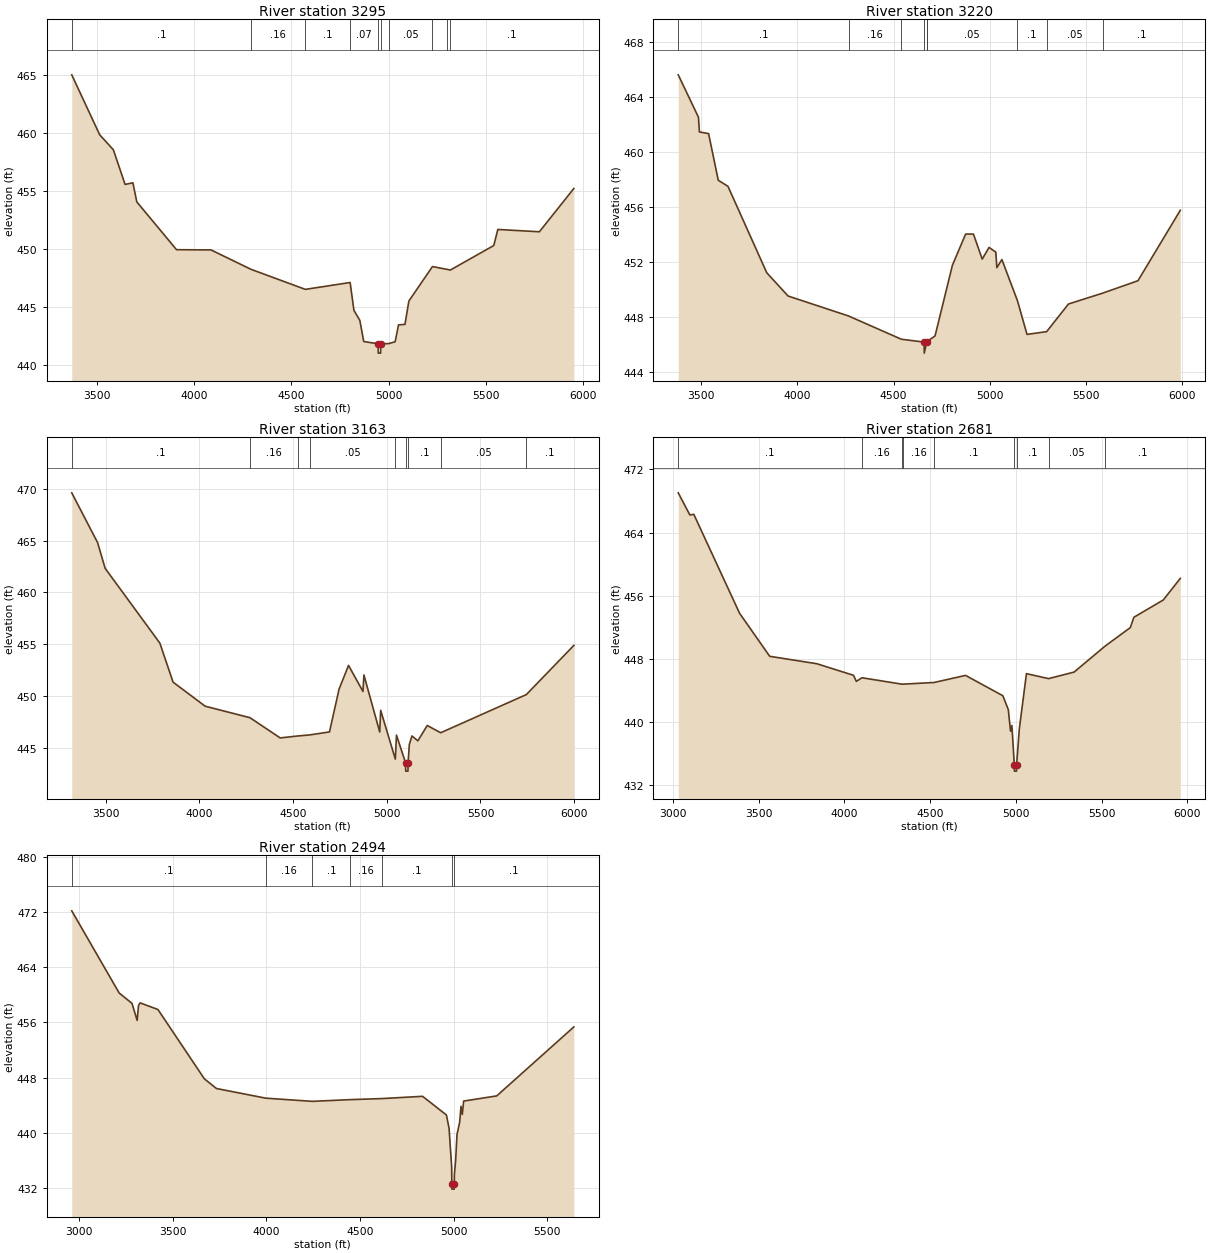
Type RM Length L Ch R = 1 ,3295    ,75,75,75
BEGIN DESCRIPTION:
Mapping XS d8d17827
END DESCRIPTION:
XS GIS Cut Line= 4
      2007557.91     13472419.39      2006434.11     13472525.78
      2005821.41     13472608.69      2005162.24     13473120.42
#Sta/Elev= 30
  3370.8  464.98  3514.3  459.83  3584.6  458.54  3644.9  455.56  3685.1   455.7
  3705.2  454.06  3909.5  449.95  4086.9  449.93  4291.5  448.27  4571.8  446.54
  4802.1  447.13  4821.6  444.74  4851.9  443.88  4872.1  442.06  4946.2  441.86
  4946.8  441.06  4958.9  441.06  4959.5  441.86  5001.4  441.88  5033.6  442.04
  5050.9  443.49    5084  443.53  5104.2  445.54  5225.4   448.5  5300.1  448.26
  5317.3   448.2  5540.7  450.31  5561.6  451.69  5775.2  451.49  5952.4  455.21
#Mann= 10 ,-1 , 0
  3370.8      .1       0  4291.5     .16       0  4571.8      .1       0
  4802.1     .07       0  4946.2     .07       0  4959.5     .07       0
  5001.4     .05       0  5225.4      .1       0  5300.1     .05       0
  5317.3      .1       0
Bank Sta=4946.2,4959.5
XS Rating Curve= 0 ,0
Exp/Cntr=0.3,0.1

Type RM Length L Ch R = 1 ,3220    ,57,57,57
BEGIN DESCRIPTION:
Mapping XS f19ca786
END DESCRIPTION:
XS GIS Cut Line= 5
      2007501.49      13472367.3      2006459.86     13472490.84
       2006047.1     13472491.51      2005630.44     13472600.01
      2005113.95      13473094.8
#Sta/Elev= 30
  3381.3   465.6  3486.3  462.52  3491.3  461.45  3538.9  461.33  3589.2  457.94
  3639.6   457.5    3841  451.22  3951.8  449.53  4265.6  448.08  4539.9  446.39
  4658.4  446.18    4659  445.38  4671.7  446.18  4672.3  446.21  4715.1  446.63
  4805.1  451.76  4873.8  454.03  4914.4  454.03    4960  452.21  4995.4  453.06
  5030.7  452.72  5035.9  451.59  5062.2  452.18    5143  449.19  5192.7  446.74
  5294.4  446.94  5408.1  448.95  5585.9  449.74  5768.9  450.64  5988.8  455.76
#Mann= 9 ,-1 , 0
  3381.3      .1       0  4265.6     .16       0  4539.9      .1       0
  4658.4     .03       0  4671.7      .1       0  4672.3     .05       0
    5143      .1       0  5294.4     .05       0  5585.9      .1       0
Bank Sta=4658.4,4671.7
XS Rating Curve= 0 ,0
Exp/Cntr=0.3,0.1

Type RM Length L Ch R = 1 ,3163    ,482,482,482
BEGIN DESCRIPTION:
Mapping XS 8e889c7f
END DESCRIPTION:
XS GIS Cut Line= 4
      2007531.93     13472293.51      2005760.65     13472495.85
      2005391.72     13472699.84      2005083.59     13473060.06
#Sta/Elev= 30
  3319.7   469.6  3457.5   464.8  3497.8  462.32  3789.7  455.11  3860.1  451.35
  4031.2  449.03  4270.5  447.92  4431.5  445.97    4526  446.16  4588.8  446.26
  4694.5  446.55  4745.8  450.68  4796.2  452.96  4873.2  450.45  4878.2  452.04
  4962.6  446.54  4967.6  448.63  5045.8  443.93  5051.9  446.24  5100.5  443.57
  5101.1  442.77  5113.2  442.77  5113.8  443.57  5120.4  445.34  5134.6  446.16
  5166.1  445.69    5216  447.17  5287.8  446.47  5744.8  450.15  5998.1  454.89
#Mann= 9 ,-1 , 0
  3319.7      .1       0  4270.5     .16       0    4526      .1       0
  4588.8     .05       0  5045.8      .1       0  5100.5     .03       0
  5113.8      .1       0  5287.8     .05       0  5744.8      .1       0
Bank Sta=5100.5,5113.8
XS Rating Curve= 0 ,0
Exp/Cntr=0.3,0.1

Type RM Length L Ch R = 1 ,2681    ,187,187,187
BEGIN DESCRIPTION:
UNT 015 in RCW 4.0
END DESCRIPTION:
XS GIS Cut Line= 3
      2007215.08     13471251.84      2005543.63     13472139.94
      2004899.89     13472949.82
#Sta/Elev= 30
  3030.8  469.04  3098.8  466.23  3121.5  466.32  3388.4  453.77  3564.2  448.31
  3838.6  447.37  4052.8   445.9  4069.1  445.13  4102.1  445.59  4337.4  444.77
  4340.6  444.78  4522.6  444.99  4705.9  445.89  4923.5  443.31  4955.3  441.54
  4968.3  438.81  4976.2  439.54  4990.3  434.55  4990.9  433.75    5003  433.75
  5003.6  434.55  5019.4   439.1    5061  446.11  5190.1  445.48  5338.8  446.31
  5519.9  449.61  5666.6  451.95  5687.4  453.26  5858.8  455.45  5958.1  458.19
#Mann= 9 ,-1 , 0
  3030.8      .1       0  4102.1     .16       0  4337.4      .1       0
  4340.6     .16       0  4522.6      .1       0  4990.3     .07       0
  5003.6      .1       0  5190.1     .05       0  5519.9      .1       0
Bank Sta=4990.3,5003.6
XS Rating Curve= 0 ,0
Exp/Cntr=0.3,0.1

Type RM Length L Ch R = 1 ,2494    ,0,0,0
BEGIN DESCRIPTION:
Mapping XS 1559d257
END DESCRIPTION:
XS GIS Cut Line= 3
      2007093.51     13470995.79      2005605.72     13471856.18
      2004916.14     13472528.58
#Sta/Elev= 30
  2960.8  472.15    3214  460.25  3282.5  458.75  3310.1  456.28  3317.2  458.42
  3325.9  458.82  3421.1  457.86  3668.9  447.83  3733.5  446.42  3997.7  445.02
  4245.3  444.56  4449.2  444.81  4616.3  444.96  4834.6  445.29  4961.9  442.59
  4976.1  440.68  4990.2  434.99  4990.7  432.65  4991.3  431.85  5003.4  431.85
    5004  432.65  5004.4  433.92  5011.5  436.11  5018.5  439.77  5032.7  441.53
  5039.8  443.84  5046.8  442.67    5054   444.6  5230.7  445.35  5642.6  455.34
#Mann= 7 ,-1 , 0
  2960.8      .1       0  3997.7     .16       0  4245.3      .1       0
  4449.2     .16       0  4616.3      .1       0  4990.7     .07       0
    5004      .1       0
Bank Sta=4990.7,5004
XS Rating Curve= 0 ,0
Exp/Cntr=0.3,0.1
LCMann Table=0

Chan Stop Cuts=-1
Use User Specified Reach Order=0
Composite Channel Slope=5