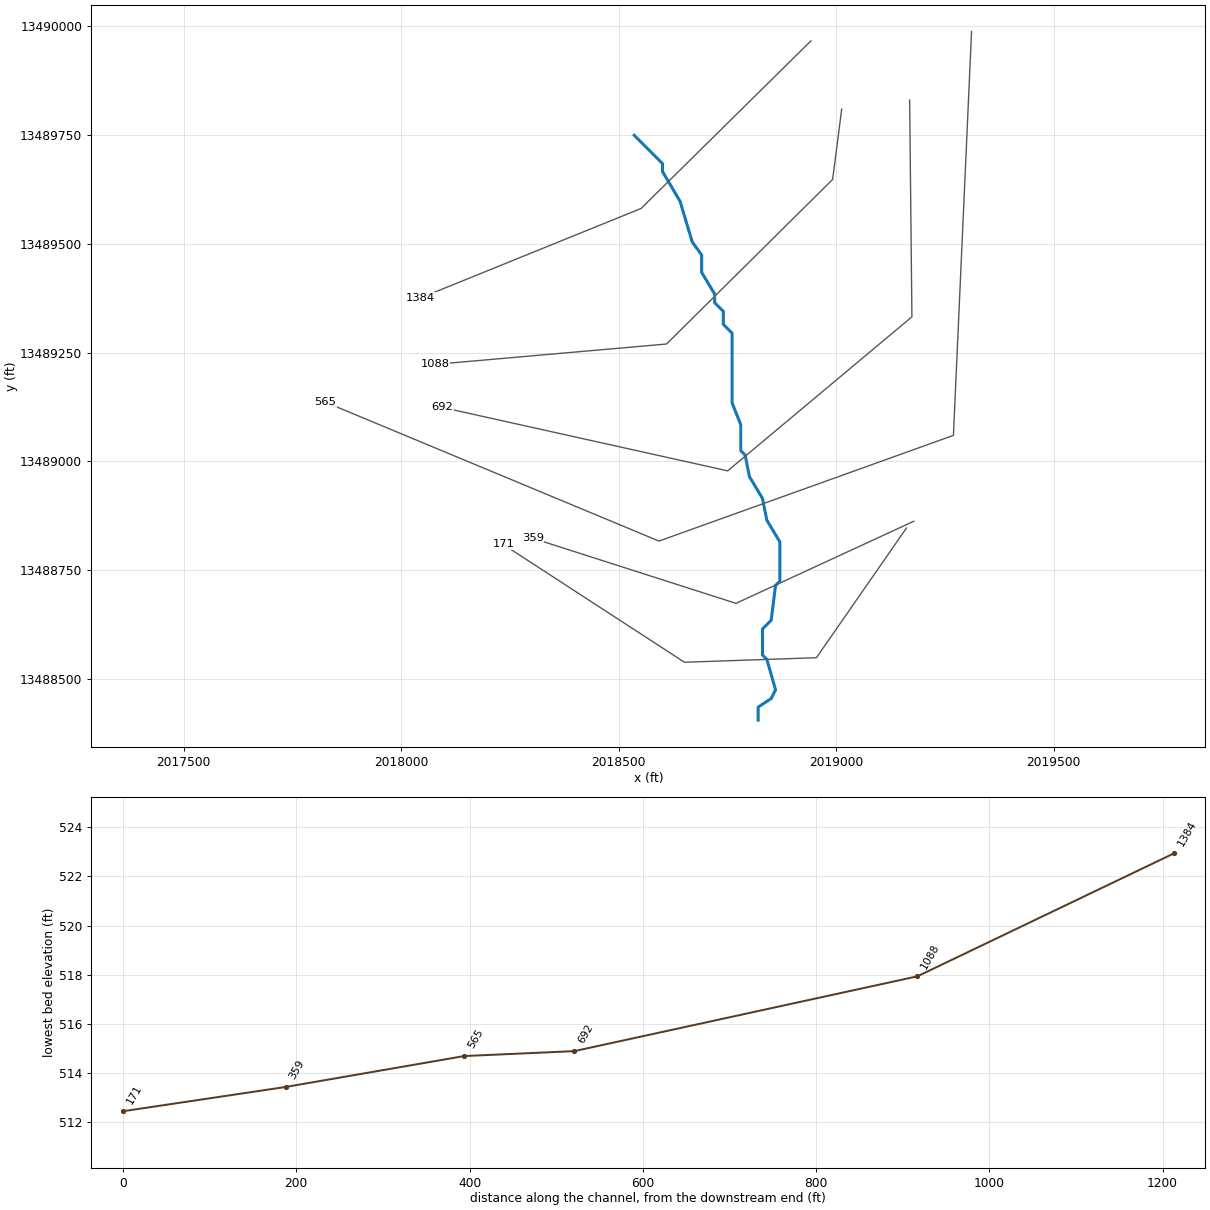
--- UNT 016 in RCW.prj (project) ---

Proj Title=UNT 016 in RCW Base Level Engineering
Current Plan=p01
Default Exp/Contr=0.3,0.1
English Units
Geom File=g01
Flow File=f01
Plan File=p01
BEGIN DESCRIPTION:
UNT 016 in RCW
END DESCRIPTION:

--- UNT 016 in RCW.p01 (plan) ---

Plan Title=Multiple Run
Short Identifier=Multiple
Geom File=g01
Flow File=f01
Subcritical Flow
K Sum by GR= 0
Std Step Tol= 0.01
Critical Tol= 0.01
Num of Std Step Trials= 20
Max Error Tol= 0.3
Flow Tol Ratio= 0.001
Split Flow NTrial= 30
Split Flow Tol= 0.02
Split Flow Ratio= 0.02
Log Output Level= 0
Friction Slope Method= 1
Unsteady Friction Slope Method= 2
Unsteady Bridges Friction Slope Method= 1
Parabolic Critical Depth
Global Vel Dist=  1 , 1 , 1
Global Log Level= 0
CheckData=True
Encroach Param= -1, 0, 0, 0
BEGIN DESCRIPTION:
Multiple Run
END DESCRIPTION:

--- UNT 016 in RCW.f01 (steady flow) ---

Flow Title=Multiple
Number of Profiles=7
Profile Names=10-year,25-year,50-year,1pct_min,100-year,1pct_plu,500-year
River Rch & RM= UNT 016 in RCW,Reach-1,1384
     154     206     248     149     297     593     434
Boundary for River Rch & Prof#=UNT 016 in RCW,Reach-1,1
Up Type=0
Dn Type=3
Dn Slope=0.005
Boundary for River Rch & Prof#=UNT 016 in RCW,Reach-1,2
Up Type=0
Dn Type=3
Dn Slope=0.005
Boundary for River Rch & Prof#=UNT 016 in RCW,Reach-1,3
Up Type=0
Dn Type=3
Dn Slope=0.005
Boundary for River Rch & Prof#=UNT 016 in RCW,Reach-1,4
Up Type=0
Dn Type=3
Dn Slope=0.005
Boundary for River Rch & Prof#=UNT 016 in RCW,Reach-1,5
Up Type=0
Dn Type=3
Dn Slope=0.005
Boundary for River Rch & Prof#=UNT 016 in RCW,Reach-1,6
Up Type=0
Dn Type=3
Dn Slope=0.005
Boundary for River Rch & Prof#=UNT 016 in RCW,Reach-1,7
Up Type=0
Dn Type=3
Dn Slope=0.005

--- UNT 016 in RCW.g01 (geometry) ---

Geom Title=Existing Conditions

River Reach=UNT 016 in RCW,Reach-1
Reach XY= 30
      2018535.80     13489749.54      2018600.80     13489684.54
      2018600.80     13489666.37      2018641.10     13489598.14
      2018669.23     13489504.39      2018690.80     13489474.54
      2018690.80     13489434.54      2018720.80     13489384.54
      2018720.80     13489364.54      2018740.80     13489344.54
      2018740.80     13489314.54      2018760.80     13489294.54
      2018760.80     13489134.54      2018780.80     13489084.54
      2018780.80     13489024.54      2018790.80     13489014.54
      2018800.80     13488964.54      2018830.80     13488914.54
      2018840.80     13488864.54      2018870.80     13488814.54
      2018870.80     13488724.54      2018860.80     13488714.54
      2018850.80     13488634.54      2018830.80     13488614.54
      2018830.80     13488554.54      2018840.80     13488544.54
      2018860.80     13488474.54      2018850.80     13488454.54
      2018820.80     13488434.54      2018820.80     13488404.54

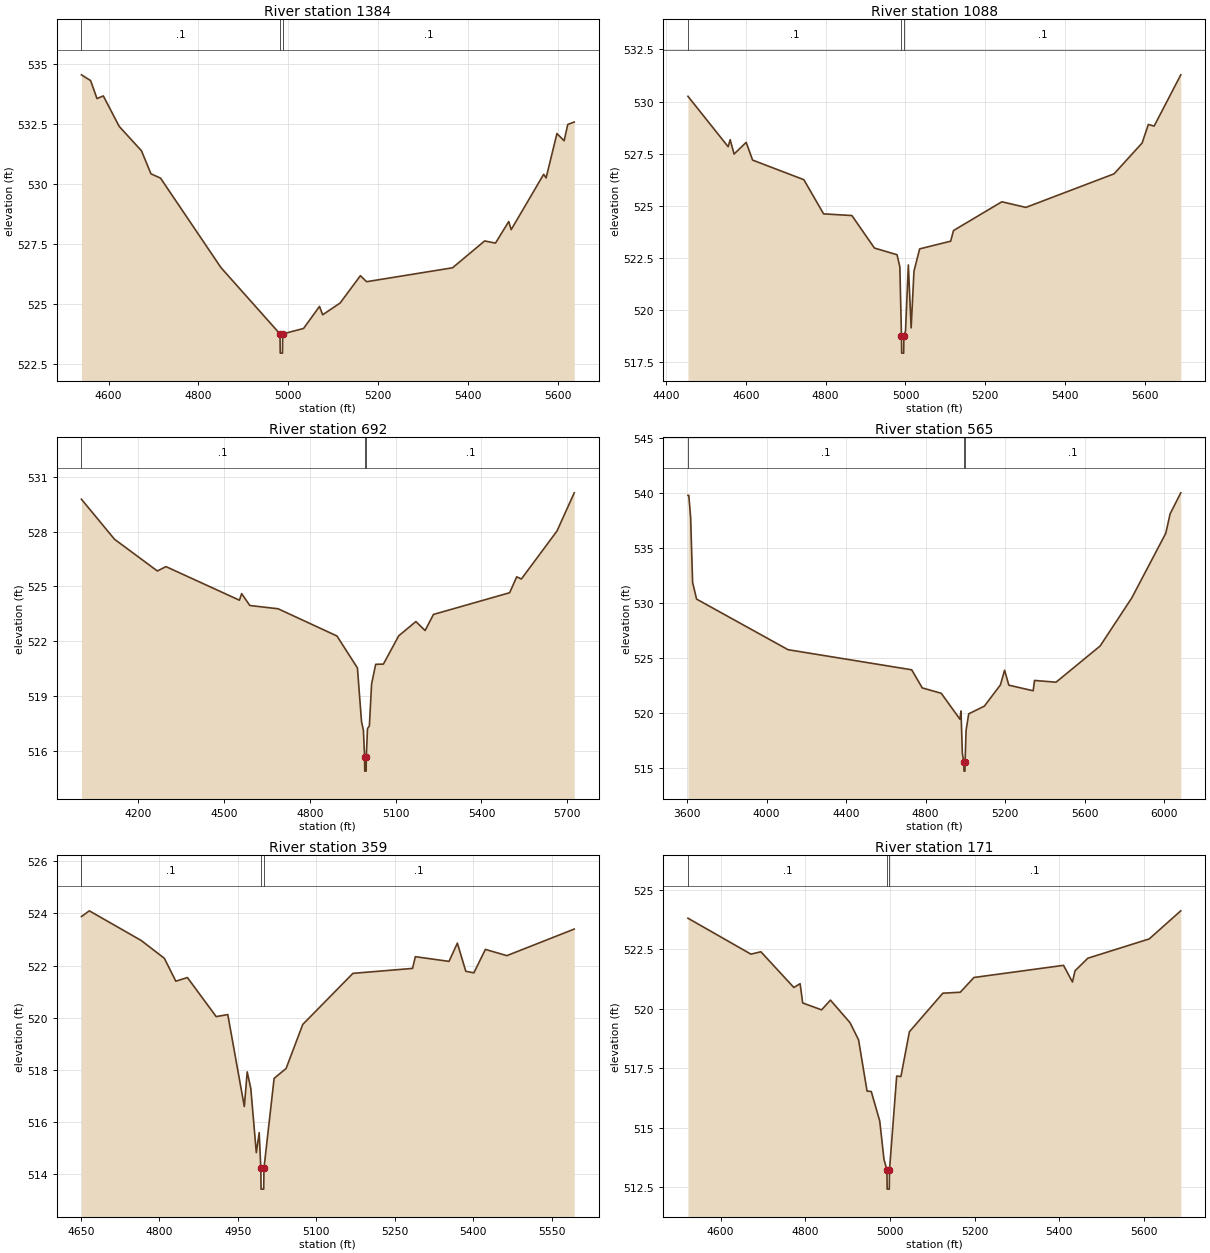
Type RM Length L Ch R = 1,1384,296,296,296
BEGIN DESCRIPTION:
UNT 016 in RCW 1.0
END DESCRIPTION:
XS GIS Cut Line= 3
      2018942.14     13489966.69      2018551.55     13489581.31
      2018044.18     13489375.58
#Sta/Elev= 30
  4539.6  534.55  4560.0  534.31  4574.2  533.56  4588.3  533.67  4623.6  532.40
  4673.2  531.38  4694.3  530.42  4715.6  530.24  4849.9  526.51  4981.3  523.74
  4981.8  522.94  4986.8  522.94  4987.3  523.74  5033.8  523.97  5069.2  524.89
  5076.2  524.54  5115.0  525.03  5160.1  526.17  5174.0  525.92  5365.1  526.50
  5436.5  527.62  5460.6  527.53  5490.1  528.43  5495.5  528.09  5567.8  530.40
  5573.2  530.25  5597.3  532.10  5613.3  531.80  5621.4  532.48  5635.8  532.58
#Mann=3,-1,0
  4539.6     0.1       0  4981.3    0.07       0  4987.3     0.1       0
Bank Sta=4981.3,4987.3
Exp/Cntr=0.3,0.1

Type RM Length L Ch R = 1,1088,396,396,396
BEGIN DESCRIPTION:
UNT 016 in RCW 6.0
END DESCRIPTION:
XS GIS Cut Line= 4
      2019012.92     13489809.59      2018992.08     13489648.15
      2018610.14     13489269.68      2018078.58     13489222.93
#Sta/Elev= 30
  4455.3  530.25  4556.0  527.83  4561.0  528.17  4570.8  527.48  4601.1  528.04
  4617.2  527.19  4745.5  526.25  4795.0  524.61  4865.8  524.53  4922.3  522.97
  4978.9  522.65  4985.9  522.07  4990.0  518.73  4990.5  517.93  4995.5  517.93
  4996.0  518.73  5000.1  518.99  5007.2  522.16  5014.2  519.14  5021.3  521.86
  5035.5  522.93  5113.2  523.30  5120.3  523.81  5241.3  525.19  5301.5  524.92
  5522.3  526.53  5592.6  528.01  5608.2  528.90  5622.7  528.82  5689.4  531.28
#Mann=3,-1,0
  4455.3     0.1       0  4990.0    0.07       0  4996.0     0.1       0
Bank Sta=4990,4996
Exp/Cntr=0.3,0.1

Type RM Length L Ch R = 1,692,127,127,127
BEGIN DESCRIPTION:
UNT 016 in RCW 5.0
END DESCRIPTION:
XS GIS Cut Line= 4
      2019169.17     13489830.47      2019174.38     13489332.18
      2018750.76     13488978.01      2018094.55     13489123.83
#Sta/Elev= 30
  4001.7  529.77  4117.2  527.58  4267.2  525.84  4297.2  526.08  4554.0  524.24
  4561.8  524.60  4590.4  523.95  4689.4  523.77  4895.0  522.28  4966.5  520.53
  4980.8  517.59  4987.4  517.12  4991.5  515.68  4992.0  514.88  4997.0  514.88
  4997.5  515.68  5001.7  517.21  5008.2  517.35  5016.0  519.65  5030.3  520.73
  5057.2  520.74  5110.9  522.29  5170.8  523.07  5203.1  522.58  5232.2  523.46
  5498.6  524.65  5523.3  525.52  5539.6  525.40  5664.1  528.03  5724.4  530.12
#Mann=3,-1,0
  4001.7     0.1       0  4991.5    0.07       0  4997.5     0.1       0
Bank Sta=4991.5,4997.5
Exp/Cntr=0.3,0.1

Type RM Length L Ch R = 1,565,206,206,206
BEGIN DESCRIPTION:
UNT 016 in RCW 4.0
END DESCRIPTION:
XS GIS Cut Line= 4
      2019311.53     13489988.38      2019269.86     13489059.61
      2018592.78     13488816.55      2017825.41     13489136.00
#Sta/Elev= 30
  3603.8  539.80  3608.0  539.80  3617.2  537.81  3627.2  531.87  3647.2  530.35
  4107.7  525.74  4729.9  523.91  4783.0  522.26  4878.7  521.77  4972.6  519.41
  4978.0  520.16  4984.9  516.29  4992.5  515.48  4993.0  514.68  4998.0  514.68
  4998.5  515.48  5003.4  518.37  5016.8  519.90  5095.6  520.60  5176.2  522.53
  5197.4  523.87  5218.7  522.51  5341.2  522.00  5348.0  522.94  5456.3  522.78
  5678.3  526.08  5837.6  530.46  6008.7  536.35  6030.4  538.11  6084.1  540.03
#Mann=3,-1,0
  3603.8     0.1       0  4992.5    0.07       0  4998.5     0.1       0
Bank Sta=4992.5,4998.5
Exp/Cntr=0.3,0.1

Type RM Length L Ch R = 1,359,188,188,188
BEGIN DESCRIPTION:
UNT 016 in RCW 3.0
END DESCRIPTION:
XS GIS Cut Line= 3
      2019178.73     13488862.13      2018769.86     13488673.32
      2018302.41     13488823.06
#Sta/Elev= 30
  4651.4  523.88  4666.5  524.10  4765.7  522.96  4809.7  522.28  4831.7  521.40
  4853.8  521.54  4908.8  520.04  4930.9  520.12  4962.5  516.59  4968.0  517.92
  4974.9  517.28  4985.4  514.82  4990.9  515.59  4994.0  514.22  4994.5  513.42
  4999.5  513.42  5000.0  514.22  5019.4  517.67  5042.3  518.05  5074.1  519.74
  5169.9  521.70  5283.8  521.89  5289.1  522.34  5353.4  522.16  5369.4  522.86
  5385.5  521.78  5400.9  521.72  5422.9  522.62  5463.9  522.38  5592.6  523.40
#Mann=3,-1,0
  4651.4     0.1       0  4994.0    0.07       0  5000.0     0.1       0
Bank Sta=4994,5000
Exp/Cntr=0.3,0.1

Type RM Length L Ch R = 1,171,0,0,0
BEGIN DESCRIPTION:
UNT 016 in RCW 2.0
END DESCRIPTION:
XS GIS Cut Line= 4
      2019161.77     13488846.47      2018954.76     13488548.32
      2018651.37     13488537.90      2018234.70     13488808.74
#Sta/Elev= 30
  4523.0  523.81  4671.7  522.30  4695.2  522.40  4773.0  520.90  4787.8  521.06
  4793.9  520.25  4838.5  519.96  4859.4  520.37  4905.7  519.42  4925.8  518.70
  4945.8  516.55  4955.8  516.53  4975.8  515.29  4985.8  513.68  4992.8  513.23
  4993.3  512.43  4998.3  512.43  4998.8  513.23  5015.8  517.18  5025.8  517.16
  5045.8  519.04  5124.7  520.66  5165.9  520.70  5198.2  521.32  5409.7  521.83
  5430.8  521.13  5436.8  521.60  5467.1  522.13  5612.0  522.94  5686.5  524.12
#Mann=3,-1,0
  4523.0     0.1       0  4992.8    0.07       0  4998.8     0.1       0
Bank Sta=4992.8,4998.8
Exp/Cntr=0.3,0.1

Chan Stop Cuts=-1