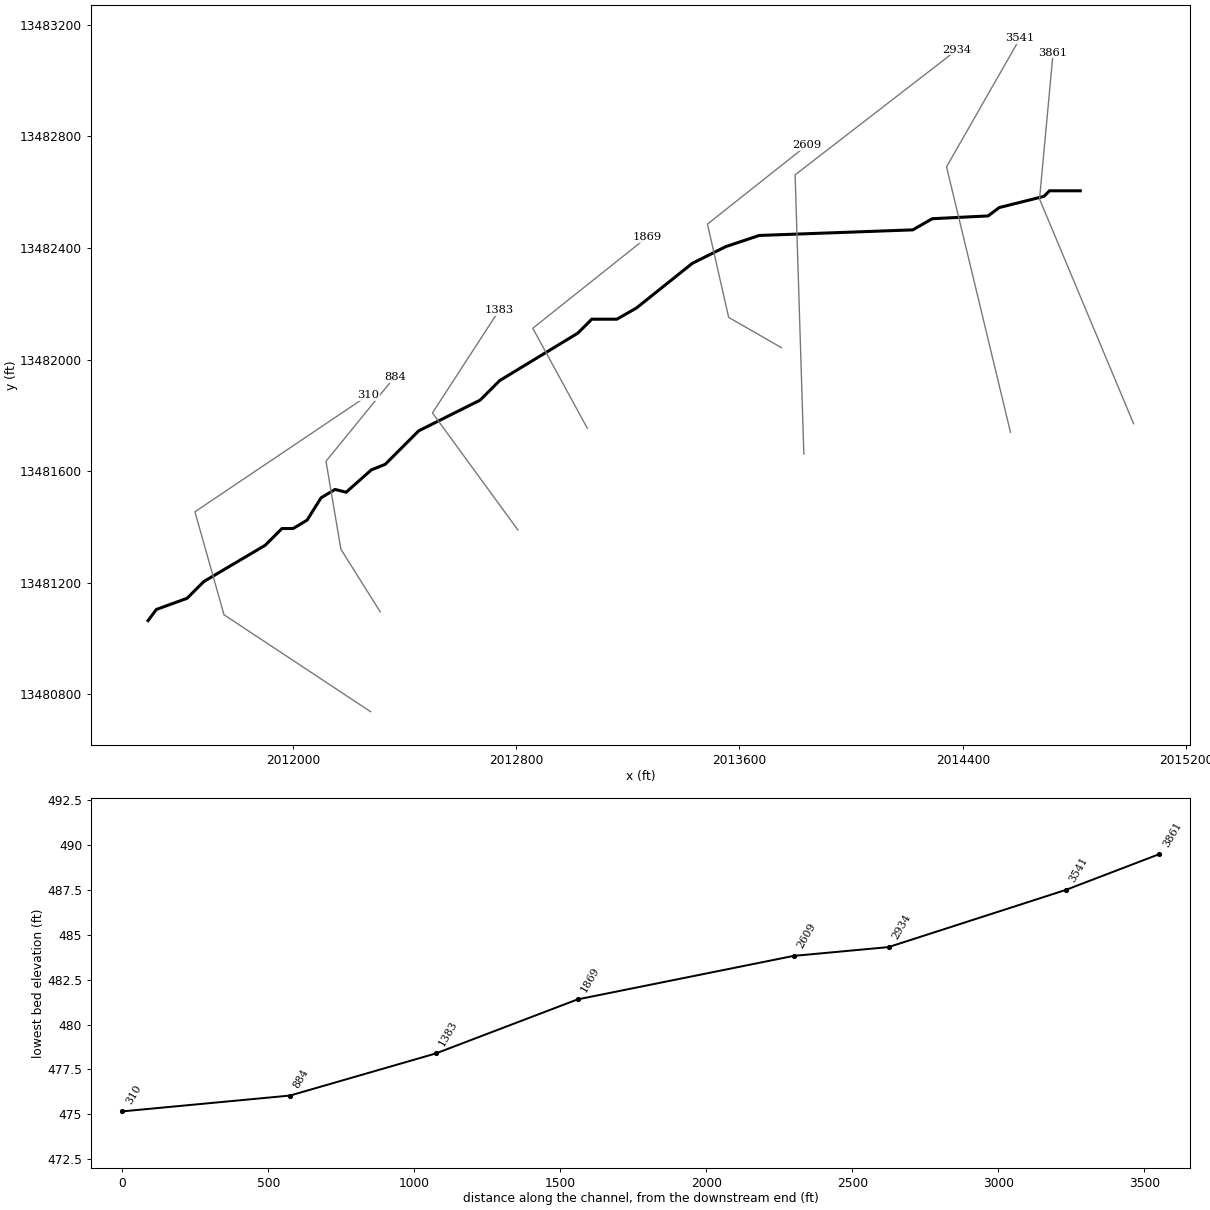
--- UNT 017 in RCW.prj (project) ---

Proj Title=UNT 017 in RCW Base Level Engineering
Current Plan=p01
Default Exp/Contr=0.3,0.1
English Units
Geom File=g01
Flow File=f01
Plan File=p01
BEGIN DESCRIPTION:
UNT 017 in RCW
END DESCRIPTION:

--- UNT 017 in RCW.p01 (plan) ---

Plan Title=Multiple Run
Short Identifier=Multiple
Geom File=g01
Flow File=f01
Subcritical Flow
K Sum by GR= 0
Std Step Tol= 0.01
Critical Tol= 0.01
Num of Std Step Trials= 20
Max Error Tol= 0.3
Flow Tol Ratio= 0.001
Split Flow NTrial= 30
Split Flow Tol= 0.02
Split Flow Ratio= 0.02
Log Output Level= 0
Friction Slope Method= 1
Unsteady Friction Slope Method= 2
Unsteady Bridges Friction Slope Method= 1
Parabolic Critical Depth
Global Vel Dist=  1 , 1 , 1
Global Log Level= 0
CheckData=True
Encroach Param= -1, 0, 0, 0
BEGIN DESCRIPTION:
Multiple Run
END DESCRIPTION:

--- UNT 017 in RCW.f01 (steady flow) ---

Flow Title=Multiple
Number of Profiles=7
Profile Names=10-year,25-year,50-year,1pct_min,100-year,1pct_plu,500-year
River Rch & RM= UNT 017 in RCW,Reach-1,3861
     204     282     345     212     422     843     640
River Rch & RM= UNT 017 in RCW,Reach-1,2609
     203     279     342     209     417     831     628
Boundary for River Rch & Prof#=UNT 017 in RCW,Reach-1,1
Up Type=0
Dn Type=3
Dn Slope=0.005
Boundary for River Rch & Prof#=UNT 017 in RCW,Reach-1,2
Up Type=0
Dn Type=3
Dn Slope=0.005
Boundary for River Rch & Prof#=UNT 017 in RCW,Reach-1,3
Up Type=0
Dn Type=3
Dn Slope=0.005
Boundary for River Rch & Prof#=UNT 017 in RCW,Reach-1,4
Up Type=0
Dn Type=3
Dn Slope=0.005
Boundary for River Rch & Prof#=UNT 017 in RCW,Reach-1,5
Up Type=0
Dn Type=3
Dn Slope=0.005
Boundary for River Rch & Prof#=UNT 017 in RCW,Reach-1,6
Up Type=0
Dn Type=3
Dn Slope=0.005
Boundary for River Rch & Prof#=UNT 017 in RCW,Reach-1,7
Up Type=0
Dn Type=3
Dn Slope=0.005

--- UNT 017 in RCW.g01 (geometry) ---

Geom Title=Existing Conditions

River Reach=UNT 017 in RCW,Reach-1
Reach XY= 30
      2014820.80     13482604.54      2014710.80     13482604.54
      2014690.80     13482584.54      2014530.80     13482544.54
      2014490.80     13482514.54      2014290.80     13482504.54
      2014220.80     13482464.54      2013670.80     13482444.54
      2013550.80     13482404.54      2013430.80     13482344.54
      2013230.80     13482184.54      2013160.80     13482144.54
      2013070.80     13482144.54      2013020.80     13482094.54
      2012740.80     13481924.54      2012670.80     13481854.54
      2012450.80     13481744.54      2012330.80     13481624.54
      2012280.80     13481604.54      2012190.80     13481524.54
      2012150.80     13481534.54      2012100.80     13481504.54
      2012050.80     13481424.54      2012000.80     13481394.54
      2011960.80     13481394.54      2011900.80     13481334.54
      2011680.80     13481204.54      2011620.80     13481144.54
      2011510.80     13481104.54      2011480.80     13481064.54

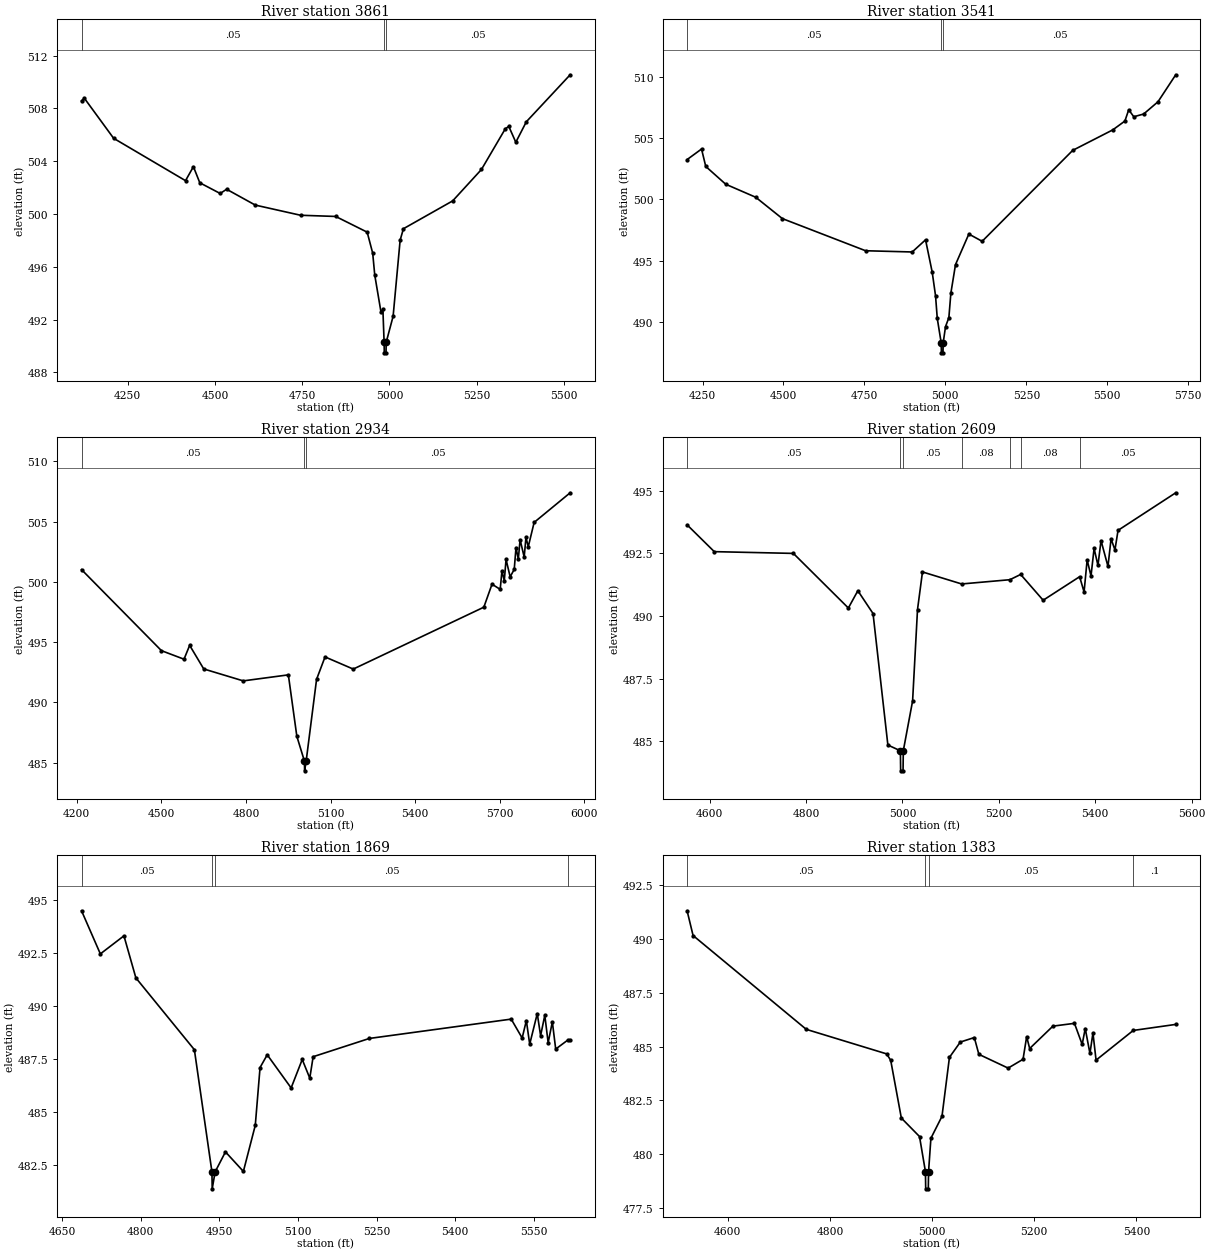
Type RM Length L Ch R = 1,3861,320,320,320
BEGIN DESCRIPTION:
UNT 017 in RCW 2.0
END DESCRIPTION:
XS GIS Cut Line= 3
      2015012.02     13481770.20      2014675.00     13482575.00
      2014723.80     13483100.02
#Sta/Elev= 30
  4117.9  508.56  4125.8  508.77  4209.8  505.73  4415.8  502.52  4438.4  503.58
  4456.7  502.36  4515.1  501.55  4533.5  501.87  4615.7  500.67  4745.5  499.90
  4846.0  499.81  4936.2  498.62  4952.0  497.03  4957.9  495.37  4975.8  492.56
  4981.2  492.77  4984.7  490.28  4985.2  489.48  4990.2  489.48  4990.7  490.28
  5010.5  492.25  5030.6  498.01  5040.0  498.88  5181.2  500.99  5263.6  503.37
  5331.9  506.45  5341.9  506.63  5362.0  505.43  5392.1  506.98  5517.7  510.54
#Mann=3,-1,0
  4117.9    0.05       0  4984.7   0.035       0  4990.7    0.05       0
Bank Sta=4984.7,4990.7
Exp/Cntr=0.3,0.1

Type RM Length L Ch R = 1,3541,607,607,607
BEGIN DESCRIPTION:
Mapping XS 064f9426
END DESCRIPTION:
XS GIS Cut Line= 3
      2014571.03     13481739.02      2014341.87     13482690.38
      2014605.13     13483151.09
#Sta/Elev= 30
  4202.3  503.24  4246.9  504.10  4259.9  502.68  4321.6  501.23  4414.2  500.17
  4496.5  498.43  4753.6  495.81  4897.6  495.71  4938.8  496.70  4959.3  494.07
  4969.6  492.15  4975.0  490.29  4987.2  488.29  4987.7  487.49  4992.7  487.49
  4993.2  488.29  5000.5  489.63  5010.8  490.36  5017.0  492.36  5031.3  494.68
  5072.5  497.17  5113.6  496.58  5393.3  503.99  5517.1  505.66  5554.5  506.38
  5566.3  507.30  5581.9  506.73  5612.3  506.95  5656.7  507.95  5711.5  510.15
#Mann=3,-1,0
  4202.3    0.05       0  4987.2   0.035       0  4993.2    0.05       0
Bank Sta=4987.2,4993.2
Exp/Cntr=0.3,0.1

Type RM Length L Ch R = 1,2934,325,325,325
BEGIN DESCRIPTION:
Mapping XS 0b5ccd08
END DESCRIPTION:
XS GIS Cut Line= 3
      2013830.58     13481661.72      2013799.33     13482661.73
      2014379.18     13483109.64
#Sta/Elev= 30
  4216.8  501.02  4500.2  494.29  4580.3  493.58  4600.3  494.73  4650.3  492.77
  4790.4  491.78  4950.4  492.28  4980.5  487.18  5007.5  485.11  5008.0  484.31
  5013.5  485.11  5050.5  491.91  5080.5  493.77  5180.6  492.76  5643.8  497.90
  5672.8  499.81  5701.8  499.38  5708.1  500.92  5716.3  500.09  5722.6  501.87
  5737.1  500.42  5751.6  501.04  5757.9  502.85  5766.1  501.89  5772.4  503.51
  5786.9  502.06  5793.2  503.69  5801.4  502.92  5822.2  504.94  5950.0  507.40
#Mann=3,-1,0
  4216.8    0.05       0  5007.5   0.035       0  5013.5    0.05       0
Bank Sta=5007.5,5013.5
Exp/Cntr=0.3,0.1

Type RM Length L Ch R = 1,2609,740,740,740
BEGIN DESCRIPTION:
Mapping XS 77f7201b
END DESCRIPTION:
XS GIS Cut Line= 4
      2013750.02     13482042.59      2013561.22     13482151.09
      2013485.27     13482485.29      2013840.60     13482766.95
#Sta/Elev= 30
  4553.1  493.64  4609.5  492.57  4773.6  492.50  4887.7  490.32  4907.4  491.01
  4938.9  490.10  4969.7  484.85  4995.7  484.62  4996.2  483.82  5001.2  483.82
  5001.7  484.62  5021.0  486.61  5031.2  490.26  5041.5  491.76  5122.8  491.28
  5222.9  491.45  5245.2  491.66  5291.9  490.63  5367.6  491.57  5376.8  490.96
  5383.2  492.24  5391.2  491.60  5397.6  492.70  5405.6  492.02  5412.0  493.01
  5426.4  491.98  5432.8  493.08  5440.9  492.64  5447.3  493.42  5567.0  494.92
#Mann=7,-1,0
  4553.1    0.05       0  4995.7   0.035       0  5001.7    0.05       0
  5122.8    0.08       0  5222.9    0.05       0  5245.2    0.08       0
  5367.6    0.05       0
Bank Sta=4995.7,5001.7
Exp/Cntr=0.3,0.1

Type RM Length L Ch R = 1,1869,486,486,486
BEGIN DESCRIPTION:
Mapping XS cb818f1b
END DESCRIPTION:
XS GIS Cut Line= 3
      2013054.72     13481753.94      2012859.40     13482112.03
      2013269.52     13482438.82
#Sta/Elev= 30
  4687.1  494.49  4723.0  492.46  4768.0  493.31  4790.8  491.33  4902.4  487.95
  4935.9  482.20  4936.4  481.40  4942.0  482.20  4961.7  483.14  4995.9  482.22
  5018.6  484.39  5027.7  487.11  5041.4  487.71  5087.0  486.15  5108.2  487.49
  5122.6  486.61  5129.0  487.62  5236.3  488.48  5506.9  489.39  5527.8  488.50
  5535.8  489.32  5542.2  488.21  5556.6  489.65  5563.0  488.61  5571.0  489.57
  5577.4  488.28  5585.4  489.26  5591.8  487.98  5614.7  488.40  5619.4  488.40
#Mann=4,-1,0
  4687.1    0.05       0  4935.9    0.03       0  4942.0    0.05       0
  5614.7     0.1       0
Bank Sta=4935.9,4942
Exp/Cntr=0.3,0.1

Type RM Length L Ch R = 1,1383,499,499,499
BEGIN DESCRIPTION:
Mapping XS 029e28c3
END DESCRIPTION:
XS GIS Cut Line= 3
      2012806.03     13481389.35      2012500.03     13481808.64
      2012738.31     13482175.83
#Sta/Elev= 30
  4520.2  491.31  4531.9  490.16  4753.6  485.80  4911.0  484.66  4918.9  484.36
  4939.7  481.68  4975.3  480.82  4986.9  479.19  4987.4  478.39  4992.5  478.39
  4993.0  479.19  4997.6  480.74  5019.3  481.76  5033.9  484.50  5055.2  485.21
  5082.6  485.42  5091.5  484.64  5148.8  484.00  5178.0  484.41  5185.1  485.46
  5191.0  484.91  5236.5  485.95  5278.7  486.08  5293.8  485.10  5299.8  485.84
  5309.0  484.68  5314.9  485.63  5321.0  484.37  5393.8  485.75  5477.0  486.03
#Mann=4,-1,0
  4520.2    0.05       0  4986.9    0.03       0  4993.0    0.05       0
  5393.8     0.1       0
Bank Sta=4986.9,4993
Exp/Cntr=0.3,0.1

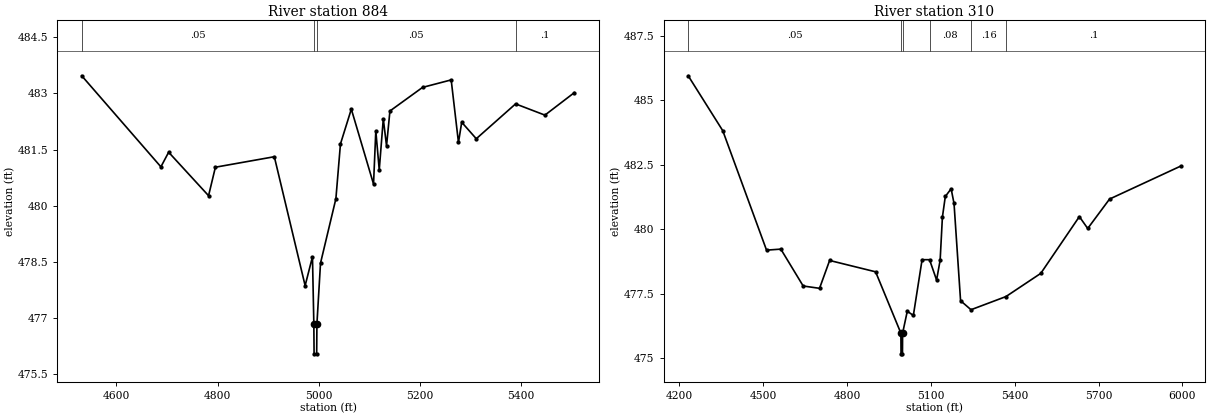
Type RM Length L Ch R = 1,884,574,574,574
BEGIN DESCRIPTION:
Mapping XS cc869dc9
END DESCRIPTION:
XS GIS Cut Line= 4
      2012312.52     13481096.41      2012171.90     13481320.36
      2012118.51     13481635.47      2012364.63     13481937.57
#Sta/Elev= 30
  4531.5  483.47  4688.0  481.04  4703.3  481.43  4782.2  480.27  4795.7  481.03
  4912.2  481.31  4973.1  477.87  4987.6  478.64  4990.3  476.85  4990.8  476.05
  4995.9  476.05  4996.4  476.85  5003.5  478.47  5033.9  480.19  5042.9  481.65
  5064.4  482.58  5108.3  480.58  5112.8  482.00  5119.6  480.96  5127.6  482.32
  5134.0  481.60  5140.7  482.53  5205.2  483.16  5261.8  483.36  5276.2  481.69
  5282.6  482.23  5311.4  481.79  5389.1  482.72  5447.1  482.42  5505.2  483.02
#Mann=4,-1,0
  4531.5    0.05       0  4990.3    0.03       0  4996.4    0.05       0
  5389.1     0.1       0
Bank Sta=4990.3,4996.4
Exp/Cntr=0.3,0.1

Type RM Length L Ch R = 1,310,0,0,0
BEGIN DESCRIPTION:
UNT 017 in RCW 1.0
END DESCRIPTION:
XS GIS Cut Line= 4
      2012278.20     13480738.35      2011753.06     13481085.55
      2011648.90     13481454.48      2012270.86     13481872.73
#Sta/Elev= 30
  4231.7  485.95  4355.4  483.82  4512.0  479.19  4563.1  479.23  4643.1  477.80
  4701.6  477.71  4737.7  478.79  4902.2  478.35  4992.7  475.97  4993.2  475.17
  4998.3  475.17  4998.8  475.97  5015.5  476.82  5037.3  476.66  5068.5  478.82
  5095.2  478.82  5120.4  478.03  5133.1  478.80  5141.2  480.47  5151.6  481.27
  5172.4  481.57  5182.8  481.00  5206.2  477.23  5243.5  476.88  5368.5  477.39
  5493.2  478.29  5631.2  480.49  5661.1  480.03  5739.2  481.17  5994.1  482.45
#Mann=6,-1,0
  4231.7    0.05       0  4992.7    0.03       0  4998.8    0.05       0
  5095.2    0.08       0  5243.5    0.16       0  5368.5     0.1       0
Bank Sta=4992.7,4998.8
Exp/Cntr=0.3,0.1

Chan Stop Cuts=-1