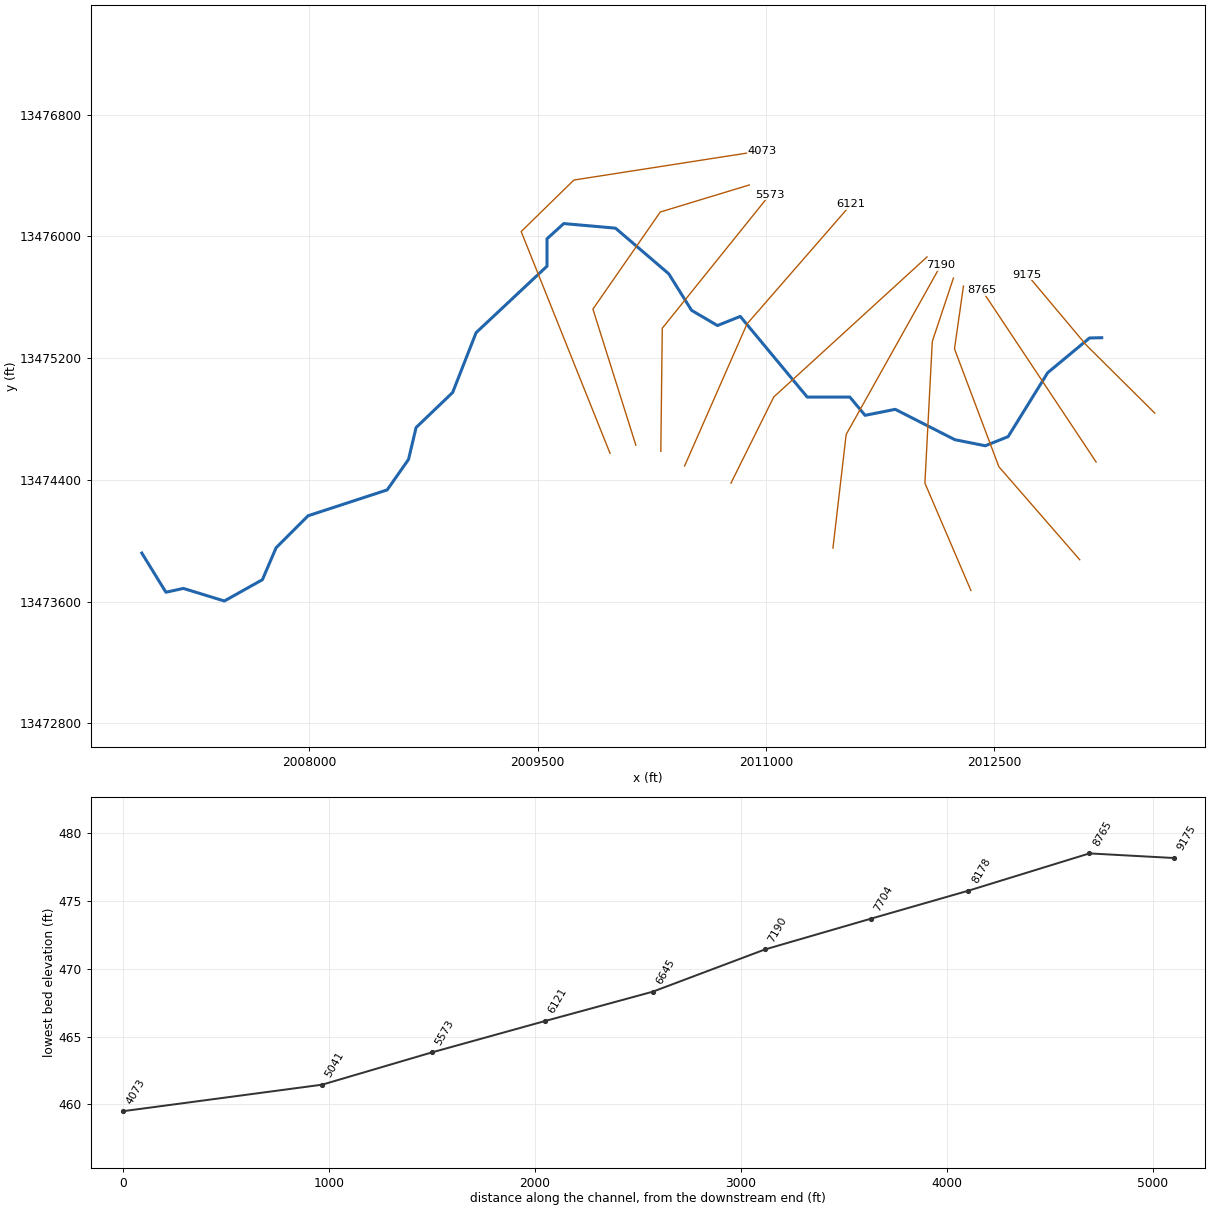
--- UNT 018 in RCW.prj (project) ---

Proj Title=UNT 018 in RCW Base Level Engineering
Current Plan=p01
Default Exp/Contr=0.3,0.1
English Units
Geom File=g01
Flow File=f01
Plan File=p01
BEGIN DESCRIPTION:
UNT 018 in RCW
END DESCRIPTION:

--- UNT 018 in RCW.p01 (plan) ---

Plan Title=Multiple Run
Short Identifier=Multiple
Geom File=g01
Flow File=f01
Subcritical Flow
K Sum by GR= 0
Std Step Tol= 0.01
Critical Tol= 0.01
Num of Std Step Trials= 20
Max Error Tol= 0.3
Flow Tol Ratio= 0.001
Split Flow NTrial= 30
Split Flow Tol= 0.02
Split Flow Ratio= 0.02
Log Output Level= 0
Friction Slope Method= 1
Unsteady Friction Slope Method= 2
Unsteady Bridges Friction Slope Method= 1
Parabolic Critical Depth
Global Vel Dist=  1 , 1 , 1
Global Log Level= 0
CheckData=True
Encroach Param= -1, 0, 0, 0
BEGIN DESCRIPTION:
Multiple Run
END DESCRIPTION:

--- UNT 018 in RCW.f01 (steady flow) ---

Flow Title=Multiple
Number of Profiles=7
Profile Names=10-year,25-year,50-year,1pct_min,100-year,1pct_plu,500-year
River Rch & RM= UNT 018 in RCW,Reach-1,9175
     187     257     314     191     382     762     574
River Rch & RM= UNT 018 in RCW,Reach-1,8178
     290     405     501     309     616    1228     945
River Rch & RM= UNT 018 in RCW,Reach-1,4073
     295     410     506     311     621    1238     948
Boundary for River Rch & Prof#=UNT 018 in RCW,Reach-1,1
Up Type=0
Dn Type=3
Dn Slope=0.005
Boundary for River Rch & Prof#=UNT 018 in RCW,Reach-1,2
Up Type=0
Dn Type=3
Dn Slope=0.005
Boundary for River Rch & Prof#=UNT 018 in RCW,Reach-1,3
Up Type=0
Dn Type=3
Dn Slope=0.005
Boundary for River Rch & Prof#=UNT 018 in RCW,Reach-1,4
Up Type=0
Dn Type=3
Dn Slope=0.005
Boundary for River Rch & Prof#=UNT 018 in RCW,Reach-1,5
Up Type=0
Dn Type=3
Dn Slope=0.005
Boundary for River Rch & Prof#=UNT 018 in RCW,Reach-1,6
Up Type=0
Dn Type=3
Dn Slope=0.005
Boundary for River Rch & Prof#=UNT 018 in RCW,Reach-1,7
Up Type=0
Dn Type=3
Dn Slope=0.005

--- UNT 018 in RCW.g01 (geometry) ---

Geom Title=Existing Conditions

River Reach=UNT 018 in RCW,Reach-1
Reach XY= 30
      2013205.80     13475334.54      2013125.81     13475332.74
      2012850.80     13475104.54      2012590.80     13474684.54
      2012440.80     13474624.54      2012240.80     13474664.54
      2011849.35     13474863.98      2011650.80     13474824.54
      2011550.80     13474944.54      2011270.80     13474944.54
      2010830.80     13475474.54      2010680.80     13475414.54
      2010510.80     13475514.54      2010360.80     13475754.54
      2010010.80     13476054.54      2009670.80     13476084.54
      2009560.80     13475984.54      2009560.80     13475804.54
      2009095.00     13475367.82      2008940.80     13474974.54
      2008700.80     13474744.54      2008650.80     13474534.54
      2008510.80     13474334.54      2007990.80     13474164.54
      2007780.80     13473954.54      2007690.80     13473744.54
      2007440.80     13473604.54      2007171.39     13473687.27
      2007056.80     13473662.09      2006898.46     13473919.53

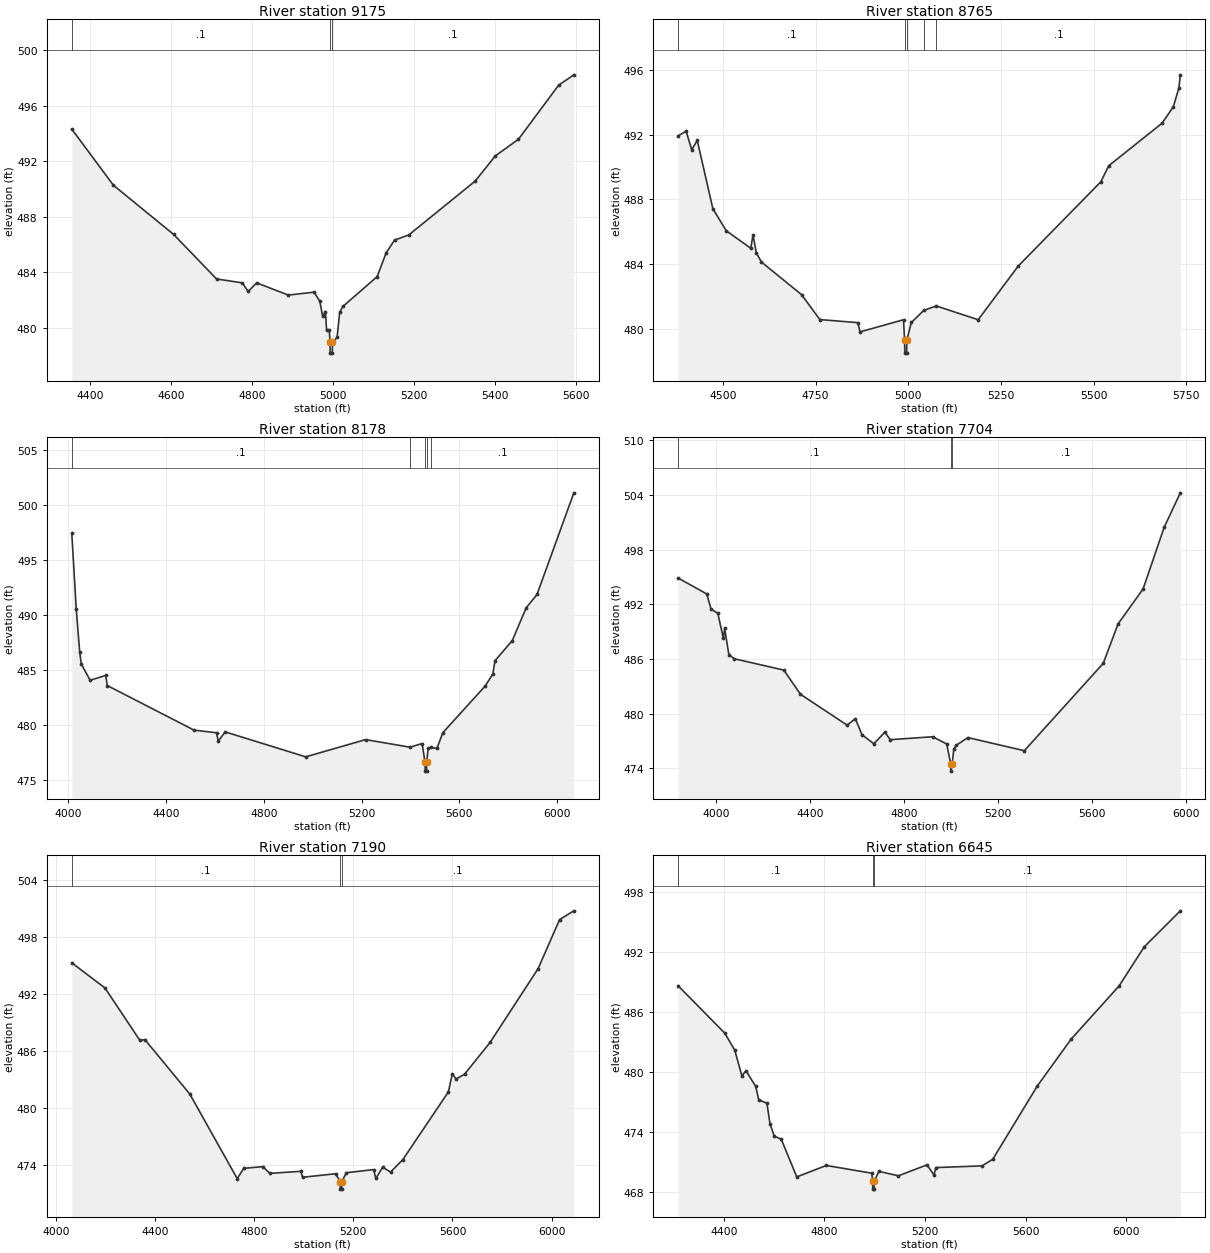
Type RM Length L Ch R = 1,9175,410,410,410
BEGIN DESCRIPTION:
UNT 018 in RCW 9.0
END DESCRIPTION:
XS GIS Cut Line= 3
      2013554.43     13474839.22      2013106.48     13475283.69
      2012715.83     13475749.01
#Sta/Elev= 30
  4355.4  494.31  4458.1  490.27  4606.6  486.73  4712.6  483.52  4776.3  483.24
  4790.4  482.62  4811.6  483.24  4889.4  482.36  4953.1  482.57  4967.2  481.92
  4974.3  480.84  4981.3  481.17  4984.0  479.85  4990.6  479.85  4992.6  478.98
  4993.1  478.18  4998.1  478.18  4998.6  478.98  5009.9  479.31  5016.4  481.13
  5024.2  481.54  5108.8  483.69  5130.9  485.40  5151.7  486.32  5186.8  486.69
  5350.7  490.57  5400.2  492.38  5457.4  493.58  5556.3  497.47  5594.0  498.22
#Mann=3,-1,0
  4355.4     0.1       0  4992.6    0.07       0  4998.6     0.1       0
Bank Sta=4992.6,4998.6
Exp/Cntr=0.3,0.1

Type RM Length L Ch R = 1,8765,587,587,587
BEGIN DESCRIPTION:
Mapping XS 3b4740fc
END DESCRIPTION:
XS GIS Cut Line= 2
      2013168.97     13474518.09      2012419.50     13475645.75
#Sta/Elev= 30
  4379.5  491.93  4400.8  492.21  4415.8  491.07  4430.8  491.64  4472.9  487.43
  4509.0  486.07  4575.1  484.99  4581.1  485.81  4590.2  484.70  4603.9  484.14
  4712.0  482.13  4761.5  480.59  4863.8  480.40  4869.8  479.83  4987.0  480.58
  4990.0  479.32  4990.5  478.52  4995.5  478.52  4996.0  479.32  5008.1  480.41
  5041.9  481.16  5075.5  481.43  5188.4  480.58  5296.7  483.90  5519.1  489.09
  5540.5  490.08  5684.6  492.71  5714.6  493.72  5729.6  494.87  5733.5  495.69
#Mann=5,-1,0
  4379.5     0.1       0  4990.0    0.07       0  4996.0     0.1       0
  5041.9    0.12       0  5075.5     0.1       0
Bank Sta=4990,4996
Exp/Cntr=0.3,0.1

Type RM Length L Ch R = 1,8178,474,474,474
BEGIN DESCRIPTION:
Mapping XS 3062f846
END DESCRIPTION:
XS GIS Cut Line= 4
      2013061.37     13473875.67      2012530.09     13474486.82
      2012238.42     13475261.13      2012297.45     13475674.32
#Sta/Elev= 30
  4014.0  497.43  4032.2  490.57  4046.4  486.63  4053.0  485.52  4089.1  484.04
  4152.8  484.48  4159.4  483.56  4514.5  479.50  4606.6  479.26  4613.3  478.50
  4641.8  479.34  4971.5  477.07  5216.5  478.64  5397.5  477.95  5447.6  478.28
  5459.8  476.57  5460.3  475.77  5465.8  475.77  5466.3  476.57  5472.4  477.85
  5485.5  477.93  5508.0  477.83  5532.9  479.28  5705.6  483.51  5737.0  484.61
  5746.0  485.82  5816.7  487.65  5873.4  490.63  5917.8  491.85  6068.6  501.10
#Mann=5,-1,0
  4014.0     0.1       0  5397.5    0.07       0  5459.8    0.07       0
  5466.3    0.07       0  5485.5     0.1       0
Bank Sta=5459.8,5466.3
Exp/Cntr=0.3,0.1

Type RM Length L Ch R = 1,7704,514,514,514
BEGIN DESCRIPTION:
Mapping XS 86c33d44
END DESCRIPTION:
XS GIS Cut Line= 4
      2012346.08     13473674.28      2012043.98     13474379.18
      2012092.59     13475309.74      2012231.47     13475726.37
#Sta/Elev= 30
  3837.2  494.87  3958.6  493.13  3976.8  491.48  4005.8  491.00  4029.4  488.26
  4034.8  489.35  4052.9  486.46  4076.5  486.02  4286.8  484.78  4357.6  482.13
  4556.0  478.75  4591.5  479.44  4619.9  477.68  4670.0  476.71  4717.3  477.97
  4740.1  477.15  4920.4  477.47  4980.4  476.68  4997.2  474.50  4997.7  473.70
  5003.7  474.50  5010.5  476.09  5020.5  476.53  5070.6  477.38  5310.9  475.94
  5646.9  485.52  5710.1  489.85  5816.6  493.68  5906.2  500.43  5975.1  504.22
#Mann=3,-1,0
  3837.2     0.1       0  4997.2    0.07       0  5003.7     0.1       0
Bank Sta=4997.2,5003.7
Exp/Cntr=0.3,0.1

Type RM Length L Ch R = 1,7190,545,545,545
BEGIN DESCRIPTION:
Mapping XS e2cf8ced
END DESCRIPTION:
XS GIS Cut Line= 3
      2011439.82     13473952.12      2011526.62     13474698.63
      2012148.16     13475809.77
#Sta/Elev= 30
  4064.7  495.29  4198.5  492.64  4339.4  487.11  4359.6  487.19  4540.8  481.45
  4732.0  472.53  4758.1  473.62  4835.0  473.80  4863.9  473.09  4988.4  473.31
  4995.4  472.68  5128.8  473.05  5147.3  472.23  5147.8  471.43  5153.3  471.43
  5153.8  472.23  5172.2  473.16  5281.9  473.49  5290.9  472.56  5318.4  473.74
  5350.3  473.23  5399.4  474.53  5583.3  481.67  5599.3  483.60  5614.2  483.04
  5648.5  483.54  5751.7  486.90  5945.2  494.67  6032.0  499.85  6089.4  500.77
#Mann=3,-1,0
  4064.7     0.1       0  5147.3    0.07       0  5153.8     0.1       0
Bank Sta=5147.3,5153.8
Exp/Cntr=0.3,0.1

Type RM Length L Ch R = 1,6645,524,524,524
BEGIN DESCRIPTION:
Mapping XS 15788ac0
END DESCRIPTION:
XS GIS Cut Line= 3
      2010769.69     13474379.22      2011050.92     13474945.15
      2012057.87     13475865.29
#Sta/Elev= 30
  4219.2  488.59  4404.8  483.86  4444.0  482.16  4472.0  479.63  4488.8  480.11
  4527.2  478.56  4539.2  477.22  4571.8  476.88  4584.0  474.83  4600.8  473.60
  4628.8  473.29  4690.4  469.53  4808.0  470.67  4988.6  469.90  4992.1  469.11
  4992.6  468.31  4998.1  468.31  4998.6  469.11  5016.9  470.08  5094.6  469.64
  5208.1  470.73  5236.0  469.73  5243.3  470.46  5427.0  470.63  5469.6  471.29
  5646.6  478.60  5781.0  483.27  5972.2  488.60  6071.5  492.48  6215.2  496.08
#Mann=3,-1,0
  4219.2     0.1       0  4992.1    0.07       0  4998.6     0.1       0
Bank Sta=4992.1,4998.6
Exp/Cntr=0.3,0.1

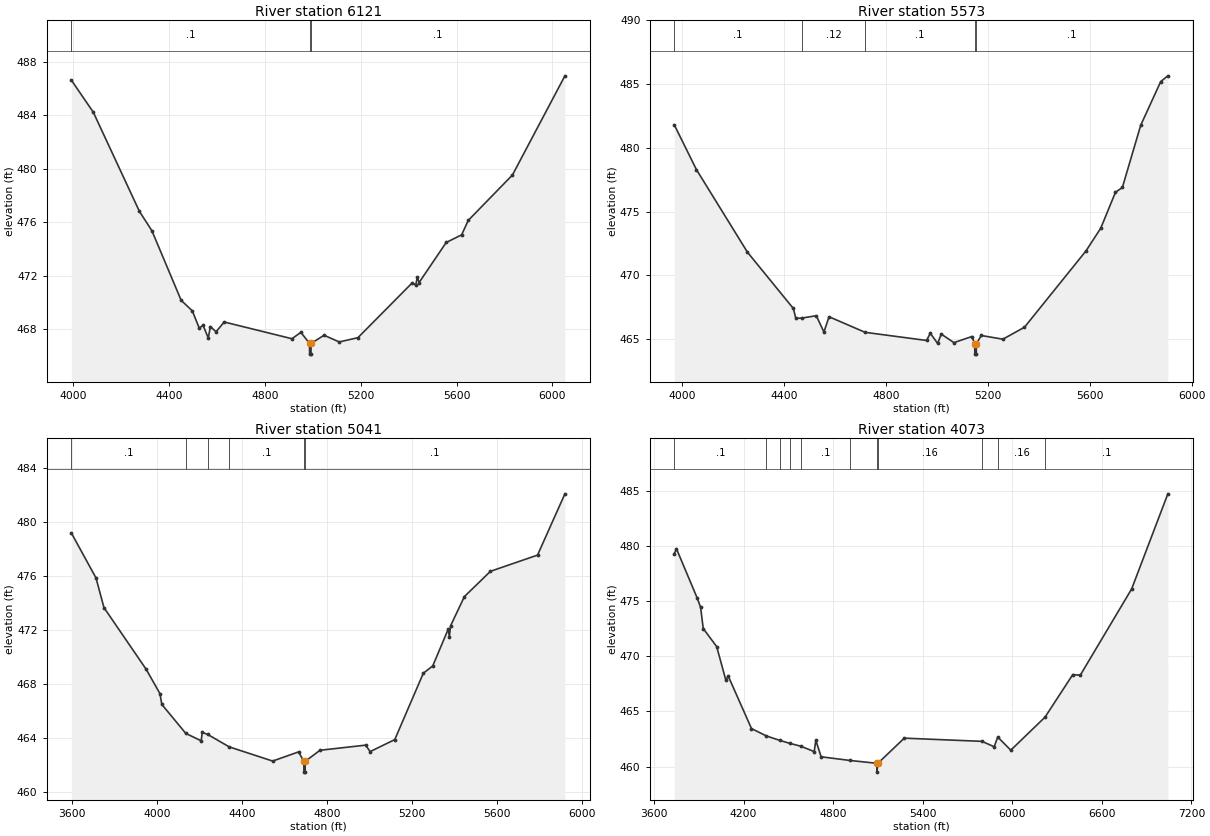
Type RM Length L Ch R = 1,6121,548,548,548
BEGIN DESCRIPTION:
UNT 018 in RCW 3.0
END DESCRIPTION:
XS GIS Cut Line= 3
      2010465.00     13474491.76      2010875.00     13475425.00
      2011558.53     13476210.25
#Sta/Elev= 30
  3991.8  486.61  4083.5  484.21  4275.8  476.81  4328.0  475.36  4450.2  470.16
  4496.9  469.37  4525.7  468.08  4541.5  468.30  4563.3  467.35  4572.4  468.20
  4595.8  467.81  4630.0  468.54  4912.8  467.29  4950.0  467.77  4986.0  466.94
  4986.5  466.14  4992.1  466.14  4992.6  466.94  5046.7  467.55  5110.3  467.05
  5188.2  467.37  5415.1  471.47  5429.4  471.29  5436.0  471.90  5443.6  471.49
  5556.6  474.48  5621.0  475.05  5648.7  476.13  5833.1  479.52  6052.2  486.93
#Mann=3,-1,0
  3991.8     0.1       0  4986.0    0.07       0  4992.6     0.1       0
Bank Sta=4986,4992.6
Exp/Cntr=0.3,0.1

Type RM Length L Ch R = 1,5573,532,532,532
BEGIN DESCRIPTION:
UNT 018 in RCW 2.0
END DESCRIPTION:
XS GIS Cut Line= 3
      2010308.74     13474588.09      2010318.29     13475396.69
      2011025.01     13476275.01
#Sta/Elev= 30
  3970.6  481.80  4057.5  478.29  4257.5  471.82  4437.5  467.41  4447.5  466.63
  4472.3  466.66  4527.6  466.84  4557.6  465.56  4577.6  466.76  4718.9  465.54
  4960.3  464.90  4974.7  465.47  5003.5  464.67  5017.9  465.40  5067.5  464.73
  5137.9  465.21  5149.0  464.63  5149.5  463.83  5155.1  463.83  5155.6  464.63
  5174.7  465.29  5259.5  465.00  5344.3  465.94  5585.9  471.93  5643.4  473.70
  5701.0  476.51  5728.2  476.89  5800.2  481.77  5878.6  485.19  5906.6  485.64
#Mann=5,-1,0
  3970.6     0.1       0  4472.3    0.12       0  4718.9     0.1       0
  5149.0    0.07       0  5155.6     0.1       0
Bank Sta=5149,5155.6
Exp/Cntr=0.3,0.1

Type RM Length L Ch R = 1,5041,968,968,968
BEGIN DESCRIPTION:
Mapping XS c122150b
END DESCRIPTION:
XS GIS Cut Line= 4
      2010144.68     13474628.44      2009862.56     13475522.55
      2010305.26     13476160.58      2010890.62     13476338.35
#Sta/Elev= 30
  3595.2  479.17  3711.3  475.84  3748.9  473.64  3948.2  469.06  4012.9  467.26
  4021.5  466.47  4134.5  464.32  4207.0  463.77  4212.2  464.39  4236.9  464.25
  4339.3  463.32  4543.8  462.27  4666.1  462.95  4690.7  462.25  4691.2  461.45
  4696.8  461.45  4697.3  462.25  4767.0  463.07  4982.2  463.45  5003.1  462.97
  5119.3  463.86  5253.9  468.78  5298.3  469.32  5371.4  472.05  5376.6  471.49
  5382.2  472.29  5447.6  474.46  5570.3  476.33  5792.1  477.53  5921.1  482.07
#Mann=6,-1,0
  3595.2     0.1       0  4134.5    0.07       0  4236.9    0.12       0
  4339.3     0.1       0  4690.7    0.07       0  4697.3     0.1       0
Bank Sta=4690.7,4697.3
Exp/Cntr=0.3,0.1

Type RM Length L Ch R = 1,4073,0,0,0
BEGIN DESCRIPTION:
UNT 018 in RCW 1.0
END DESCRIPTION:
XS GIS Cut Line= 4
      2009974.99     13474575.03      2009391.20     13476032.10
      2009737.56     13476370.64      2010974.54     13476563.35
#Sta/Elev= 30
  3735.8  479.29  3750.6  479.73  3887.8  475.32  3912.0  474.44  3929.7  472.51
  4019.7  470.87  4080.5  467.86  4097.7  468.18  4252.9  463.44  4352.5  462.77
  4444.4  462.36  4511.7  462.09  4583.3  461.84  4673.0  461.35  4683.8  462.38
  4719.3  460.88  4911.3  460.55  5092.6  460.29  5093.1  459.49  5099.6  460.29
  5276.3  462.57  5797.1  462.28  5878.3  461.79  5902.5  462.67  5989.6  461.48
  6218.8  464.47  6404.6  468.33  6455.2  468.28  6799.3  476.10  7041.7  484.72
#Mann=11,-1,0
  3735.8     0.1       0  4352.5    0.12       0  4444.4    0.16       0
  4511.7    0.12       0  4583.3     0.1       0  4911.3    0.16       0
  5092.6    0.07       0  5099.6    0.16       0  5797.1     0.1       0
  5902.5    0.16       0  6218.8     0.1       0
Bank Sta=5092.6,5099.6
Exp/Cntr=0.3,0.1

Chan Stop Cuts=-1