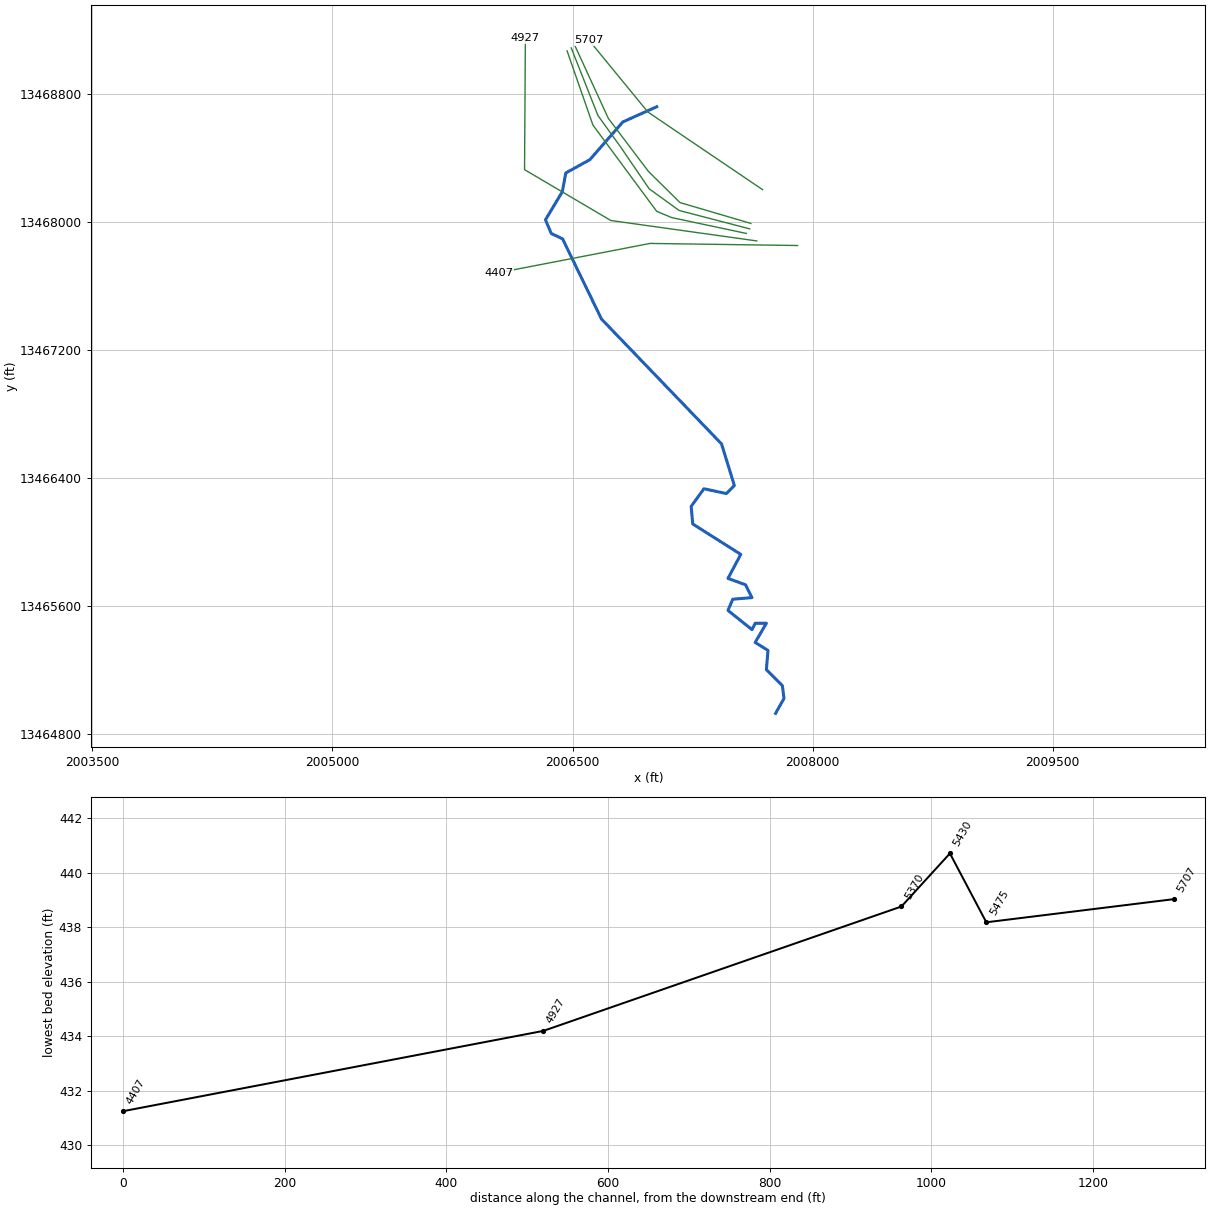
--- UNT 019 in RCW.prj (project) ---

Proj Title=UNT 019 in RCW Base Level Engineering
Current Plan=p01
Default Exp/Contr=0.3,0.1
English Units
Geom File=g01
Flow File=f01
Plan File=p01
BEGIN DESCRIPTION:
UNT 019 in RCW
END DESCRIPTION:

--- UNT 019 in RCW.p01 (plan) ---

Plan Title=Multiple Run
Short Identifier=Multiple
Geom File=g01
Flow File=f01
Subcritical Flow
K Sum by GR= 0
Std Step Tol= 0.01
Critical Tol= 0.01
Num of Std Step Trials= 20
Max Error Tol= 0.3
Flow Tol Ratio= 0.001
Split Flow NTrial= 30
Split Flow Tol= 0.02
Split Flow Ratio= 0.02
Log Output Level= 0
Friction Slope Method= 1
Unsteady Friction Slope Method= 2
Unsteady Bridges Friction Slope Method= 1
Parabolic Critical Depth
Global Vel Dist=  1 , 1 , 1
Global Log Level= 0
CheckData=True
Encroach Param= -1, 0, 0, 0
BEGIN DESCRIPTION:
Multiple Run
END DESCRIPTION:

--- UNT 019 in RCW.f01 (steady flow) ---

Flow Title=Multiple
Number of Profiles=7
Profile Names=10-year,25-year,50-year,1pct_min,100-year,1pct_plu,500-year
River Rch & RM= UNT 019 in RCW,Reach-1,5707
     182     250     306     187     373     744     562
River Rch & RM= UNT 019 in RCW,Reach-1,4407
     228     316     388     238     474     946     720
Boundary for River Rch & Prof#=UNT 019 in RCW,Reach-1,1
Up Type=0
Dn Type=3
Dn Slope=0.005
Boundary for River Rch & Prof#=UNT 019 in RCW,Reach-1,2
Up Type=0
Dn Type=3
Dn Slope=0.005
Boundary for River Rch & Prof#=UNT 019 in RCW,Reach-1,3
Up Type=0
Dn Type=3
Dn Slope=0.005
Boundary for River Rch & Prof#=UNT 019 in RCW,Reach-1,4
Up Type=0
Dn Type=3
Dn Slope=0.005
Boundary for River Rch & Prof#=UNT 019 in RCW,Reach-1,5
Up Type=0
Dn Type=3
Dn Slope=0.005
Boundary for River Rch & Prof#=UNT 019 in RCW,Reach-1,6
Up Type=0
Dn Type=3
Dn Slope=0.005
Boundary for River Rch & Prof#=UNT 019 in RCW,Reach-1,7
Up Type=0
Dn Type=3
Dn Slope=0.005

--- UNT 019 in RCW.g01 (geometry) ---

Geom Title=Existing Conditions

River Reach=UNT 019 in RCW,Reach-1
Reach XY= 30
      2007025.59     13468720.92      2006814.13     13468626.12
      2006607.88     13468390.19      2006457.88     13468307.37
      2006436.01     13468190.19      2006330.80     13468014.68
      2006366.94     13467929.27      2006437.78     13467895.41
      2006680.80     13467394.54      2007430.80     13466614.54
      2007510.80     13466354.54      2007460.80     13466304.54
      2007320.80     13466334.54      2007240.80     13466224.54
      2007250.80     13466114.54      2007550.80     13465924.54
      2007470.80     13465774.54      2007580.80     13465734.54
      2007620.80     13465654.54      2007500.80     13465644.54
      2007470.80     13465574.54      2007620.80     13465454.54
      2007640.80     13465494.54      2007710.80     13465494.54
      2007640.80     13465374.54      2007720.80     13465324.54
      2007710.80     13465204.54      2007810.80     13465104.54
      2007820.80     13465024.54      2007768.29     13464931.32

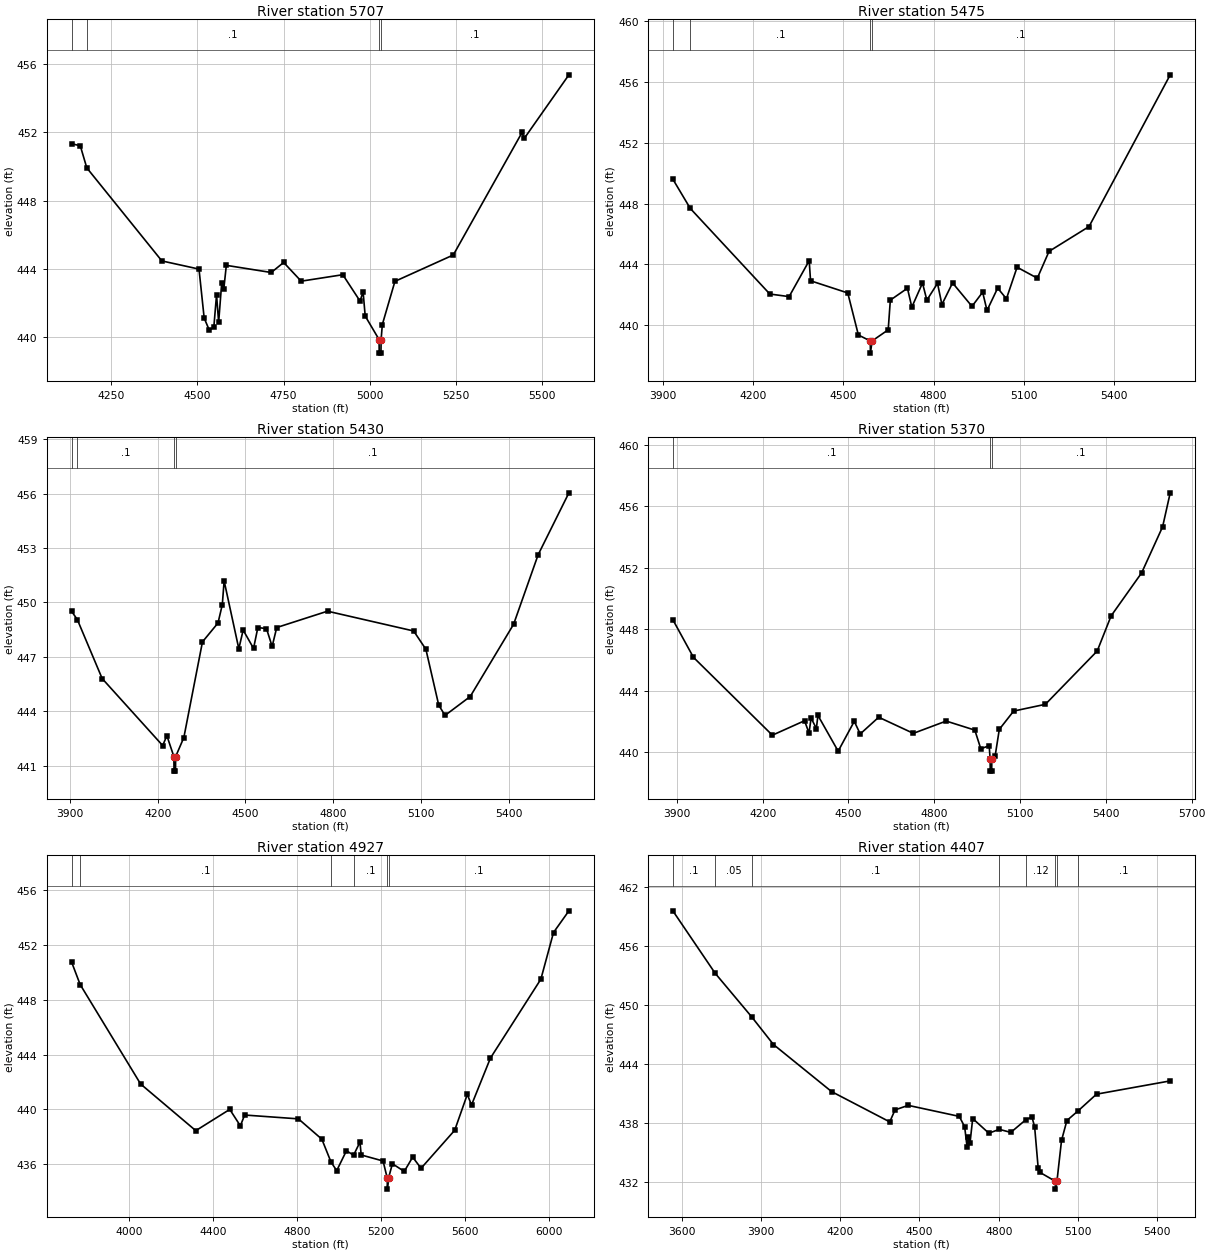
Type RM Length L Ch R = 1,5707,232,232,232
BEGIN DESCRIPTION:
UNT 019 in RCW 7.0
END DESCRIPTION:
XS GIS Cut Line= 3
      2007687.04     13468203.00      2006970.38     13468688.10
      2006603.70     13469135.29
#Sta/Elev= 30
  4134.6  451.34  4160.0  451.22  4178.9  449.92  4396.8  444.45  4504.6  443.97
  4519.6  441.09  4534.5  440.38  4547.6  440.55  4555.5  442.46  4561.6  440.84
  4570.5  443.16  4576.5  442.79  4583.9  444.19  4714.3  443.77  4750.3  444.36
  4801.2  443.26  4922.0  443.64  4972.0  442.09  4980.9  442.63  4987.0  441.21
  5027.2  439.83  5027.7  439.03  5032.7  439.03  5033.2  439.83  5036.7  440.71
  5073.3  443.25  5242.7  444.80  5442.2  452.00  5448.6  451.65  5578.3  455.39
#Mann=4,-1,0
  4134.6    0.05       0  4178.9     0.1       0  5027.2    0.07       0
  5033.2     0.1       0
Bank Sta=5027.2,5033.2
Exp/Cntr=0.3,0.1

Type RM Length L Ch R = 1,5475,45,45,45
BEGIN DESCRIPTION:
Mapping XS ea0dbab1
END DESCRIPTION:
XS GIS Cut Line= 5
      2007614.05     13467992.10      2007171.38     13468122.29
      2006973.46     13468317.61      2006723.46     13468648.34
      2006515.46     13469100.74
#Sta/Elev= 30
  3934.0  449.60  3991.9  447.68  4256.1  442.06  4320.2  441.89  4386.9  444.25
  4391.4  442.93  4515.0  442.13  4550.3  439.37  4589.8  438.98  4590.3  438.18
  4595.8  438.98  4649.3  439.71  4656.4  441.66  4713.2  442.44  4727.8  441.20
  4763.2  442.78  4777.7  441.66  4813.1  442.76  4827.7  441.37  4863.1  442.79
  4927.6  441.25  4963.0  442.18  4977.5  440.98  5012.9  442.45  5042.0  441.75
  5077.4  443.82  5144.6  443.10  5183.5  444.86  5316.4  446.49  5586.0  456.45
#Mann=4,-1,0
  3934.0    0.05       0  3991.9     0.1       0  4589.8    0.07       0
  4595.8     0.1       0
Bank Sta=4589.8,4595.8
Exp/Cntr=0.3,0.1

Type RM Length L Ch R = 1,5430,60,60,60
BEGIN DESCRIPTION:
Mapping XS d6d4420a
END DESCRIPTION:
XS GIS Cut Line= 6
      2007606.26     13467958.24      2007166.17     13468072.82
      2006978.67     13468208.23      2006798.99     13468471.25
      2006658.36     13468666.57      2006491.68     13469088.48
#Sta/Elev= 30
  3905.8  449.52  3925.8  449.05  4010.4  445.81  4217.1  442.12  4231.5  442.66
  4255.4  441.51  4255.9  440.71  4260.9  440.71  4261.4  441.51  4289.4  442.56
  4353.0  447.83  4406.1  448.87  4420.8  449.88  4427.0  451.19  4477.2  447.45
  4492.0  448.48  4527.5  447.47  4542.2  448.62  4571.7  448.56  4591.0  447.58
  4606.7  448.62  4780.1  449.52  5074.4  448.43  5116.2  447.42  5160.1  444.34
  5181.6  443.78  5267.6  444.82  5415.8  448.80  5499.6  452.63  5604.7  456.04
#Mann=4,-1,0
  3905.8    0.05       0  3925.8     0.1       0  4255.4    0.07       0
  4261.4     0.1       0
Bank Sta=4255.4,4261.4
Exp/Cntr=0.3,0.1

Type RM Length L Ch R = 1,5370,443,443,443
BEGIN DESCRIPTION:
Mapping XS 2112cfa5
END DESCRIPTION:
XS GIS Cut Line= 5
      2007585.44     13467929.59      2007119.30     13468028.54
      2007025.55     13468067.61      2006627.11     13468606.67
      2006465.68     13469070.14
#Sta/Elev= 30
  3885.8  448.62  3957.8  446.17  4233.8  441.10  4346.3  442.04  4362.0  441.24
  4369.3  442.22  4387.7  441.53  4393.1  442.39  4463.9  440.06  4520.2  442.00
  4541.0  441.18  4605.7  442.27  4726.8  441.22  4841.6  442.02  4941.8  441.43
  4962.7  440.21  4992.0  440.42  4995.2  439.56  4995.7  438.76  5000.7  438.76
  5001.2  439.56  5012.8  439.75  5027.4  441.48  5077.5  442.67  5188.5  443.11
  5369.7  446.58  5418.4  448.87  5525.1  451.67  5598.4  454.67  5625.0  456.88
#Mann=3,-1,0
  3885.8     0.1       0  4995.2    0.07       0  5001.2     0.1       0
Bank Sta=4995.2,5001.2
Exp/Cntr=0.3,0.1

Type RM Length L Ch R = 1,4927,520,520,520
BEGIN DESCRIPTION:
Mapping XS 3d31d0b7
END DESCRIPTION:
XS GIS Cut Line= 4
      2007650.54     13467882.71      2006739.09     13468010.32
      2006200.03     13468328.02      2006205.24     13469148.35
#Sta/Elev= 30
  3727.1  450.75  3768.0  449.10  4055.8  441.85  4318.3  438.45  4479.9  440.00
  4530.4  438.80  4550.6  439.59  4806.6  439.31  4918.0  437.83  4961.7  436.16
  4988.8  435.54  5035.1  436.99  5068.9  436.66  5099.4  437.62  5105.2  436.68
  5209.3  436.24  5229.2  434.99  5229.7  434.19  5235.2  434.99  5253.7  436.04
  5310.1  435.48  5350.1  436.52  5390.1  435.71  5550.1  438.48  5610.1  441.09
  5630.1  440.32  5720.1  443.74  5960.1  449.49  6020.2  452.89  6093.5  454.47
#Mann=6,-1,0
  3727.1    0.05       0  3768.0     0.1       0  4961.7    0.07       0
  5068.9     0.1       0  5229.2    0.07       0  5235.2     0.1       0
Bank Sta=5229.2,5235.2
Exp/Cntr=0.3,0.1

Type RM Length L Ch R = 1,4407,0,0,0
BEGIN DESCRIPTION:
UNT 019 in RCW 6.0
END DESCRIPTION:
XS GIS Cut Line= 3
      2007905.75     13467854.07      2006983.88     13467867.09
      2006041.20     13467684.80
#Sta/Elev= 30
  3566.8  459.55  3726.9  453.20  3865.3  448.76  3947.6  445.95  4167.6  441.16
  4387.6  438.08  4407.6  439.30  4457.6  439.76  4650.6  438.64  4671.0  437.59
  4680.1  435.56  4685.2  436.53  4691.3  435.93  4701.5  438.42  4762.6  436.93
  4802.1  437.32  4845.7  437.01  4901.6  438.28  4925.6  438.58  4935.8  437.59
  4949.3  433.38  4956.1  432.94  5014.2  432.04  5014.7  431.24  5020.3  432.04
  5037.6  436.19  5058.0  438.22  5100.7  439.21  5170.0  440.90  5448.9  442.25
#Mann=8,-1,0
  3566.8     0.1       0  3726.9    0.05       0  3865.3     0.1       0
  4802.1    0.07       0  4901.6    0.12       0  5014.2    0.07       0
  5020.3    0.12       0  5100.7     0.1       0
Bank Sta=5014.2,5020.3
Exp/Cntr=0.3,0.1

Chan Stop Cuts=-1