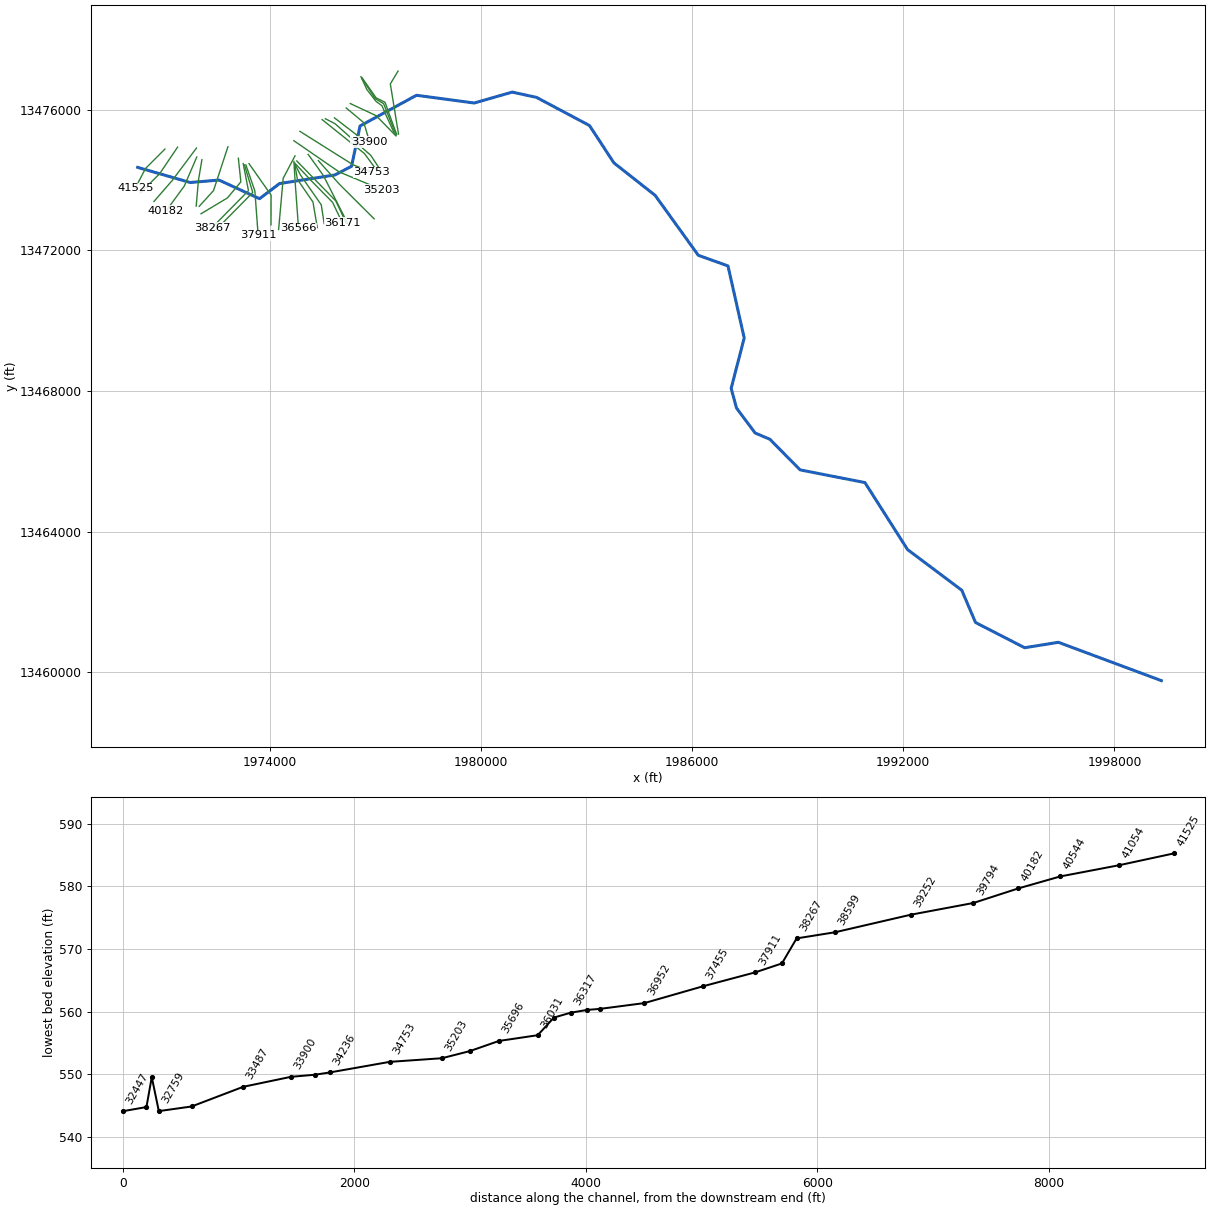
--- UNT 022 in RCW.prj (project) ---

Proj Title=UNT 022 in RCW Base Level Engineering
Current Plan=p01
Default Exp/Contr=0.3,0.1
English Units
Geom File=g01
Flow File=f01
Plan File=p01
Y Axis Title=Elevation
X Axis Title(PF)=Main Channel Distance
X Axis Title(XS)=Station
BEGIN DESCRIPTION:
UNT 022 in RCW
END DESCRIPTION:
DSS Export Rating Curves= 0
DSS Export Rating Curve Sorted= 0
DSS Export Volume Flow Curves= 0
DXF OffsetX= 0
DXF OffsetY= 0
DXF ScaleX= 1
DXF ScaleY= 10

--- UNT 022 in RCW.p01 (plan) ---

Plan Title=Multiple Run
Short Identifier=Multiple
Geom File=g01
Flow File=f01
Subcritical Flow
K Sum by GR= 0
Std Step Tol= 0.01
Critical Tol= 0.01
Num of Std Step Trials= 20
Max Error Tol= 0.3
Flow Tol Ratio= 0.001
Split Flow NTrial= 30
Split Flow Tol= 0.02
Split Flow Ratio= 0.02
Log Output Level= 0
Friction Slope Method= 1
Unsteady Friction Slope Method= 2
Unsteady Bridges Friction Slope Method= 1
Parabolic Critical Depth
Global Vel Dist=  1 , 1 , 1
Global Log Level= 0
CheckData=True
Encroach Param= -1, 0, 0, 0
BEGIN DESCRIPTION:
Multiple Run
END DESCRIPTION:

--- UNT 022 in RCW.f01 (steady flow) ---

Flow Title=Multiple
Program Version=5.05
Number of Profiles= 7
Profile Names=10-year,25-year,50-year,1pct_min,100-year,1pct_plu,500-year
River Rch & RM=UNT 022 in RCW,Reach-1         ,41525
     150     205     249     152     303     604     455
River Rch & RM=UNT 022 in RCW,Reach-1         ,40544
     268     377     468     290     578    1154     899
River Rch & RM=UNT 022 in RCW,Reach-1         ,33487
     372     531     666     416     830    1657    1313
River Rch & RM=UNT 022 in RCW,Reach-1         ,31702
     406     581     730     457     912    1821    1448
River Rch & RM=UNT 022 in RCW,Reach-1         ,28589
     553     801    1015     640    1276    2547    2052
River Rch & RM=UNT 022 in RCW,Reach-1         ,23769
     598     867    1099     693    1382    2758    2224
River Rch & RM=UNT 022 in RCW,Reach-1         ,20168
     615     890    1127     709    1415    2824    2269
River Rch & RM=UNT 022 in RCW,Reach-1         ,16599
     608     876    1105     693    1383    2759    2201
River Rch & RM=UNT 022 in RCW,Reach-1         ,12421
     640     921    1160     726    1449    2891    2298
River Rch & RM=UNT 022 in RCW,Reach-1         ,7278
     665     957    1207     756    1508    3009    2396
River Rch & RM=UNT 022 in RCW,Reach-1         ,5214
    1192    1755    2246    1426    2846    5679    4644
River Rch & RM=UNT 022 in RCW,Reach-1         ,234
    1228    1809    2319    1474    2942    5869    4810
Boundary for River Rch & Prof#=UNT 022 in RCW,Reach-1         , 1
Up Type= 0
Dn Type= 3
Dn Slope=0.01356
Boundary for River Rch & Prof#=UNT 022 in RCW,Reach-1         , 2
Up Type= 0
Dn Type= 3
Dn Slope=0.01356
Boundary for River Rch & Prof#=UNT 022 in RCW,Reach-1         , 3
Up Type= 0
Dn Type= 3
Dn Slope=0.01356
Boundary for River Rch & Prof#=UNT 022 in RCW,Reach-1         , 4
Up Type= 0
Dn Type= 3
Dn Slope=0.01356
Boundary for River Rch & Prof#=UNT 022 in RCW,Reach-1         , 5
Up Type= 0
Dn Type= 3
Dn Slope=0.01356
Boundary for River Rch & Prof#=UNT 022 in RCW,Reach-1         , 6
Up Type= 0
Dn Type= 3
Dn Slope=0.01356
Boundary for River Rch & Prof#=UNT 022 in RCW,Reach-1         , 7
Up Type= 0
Dn Type= 3
Dn Slope=0.01356
DSS Import GetInterval= 0
DSS Import GetPeak= 0
DSS Import FillOption= 0

--- UNT 022 in RCW.g01 (geometry) ---

Geom Title=Existing Conditions
Program Version=5.05

River Reach=UNT 022 in RCW  ,Reach-1
Reach XY= 30
       1970250.8     13474354.54       1971740.8     13473924.54
       1972560.8     13473994.54       1973710.8     13473464.54
       1974280.8     13473894.54       1975851.9     13474138.93
      1976326.74     13474386.17      1976566.89     13475531.52
       1978170.8     13476404.54       1979810.8     13476184.54
       1980890.8     13476494.54       1981580.8     13476344.54
      1983085.74     13475543.95      1983778.45     13474483.53
      1984951.89     13473557.83      1986176.04     13471855.97
      1987020.23     13471553.24       1987480.8     13469504.54
       1987110.8     13468074.54       1987260.8     13467514.54
       1987790.8     13466804.54       1988210.8     13466624.54
       1989070.8     13465754.54       1990910.8     13465394.54
      1992120.16      13463490.8       1993660.8     13462334.54
      1994052.49     13461416.79      1995447.89     13460699.56
      1996405.86     13460853.85       1999330.8     13459764.54

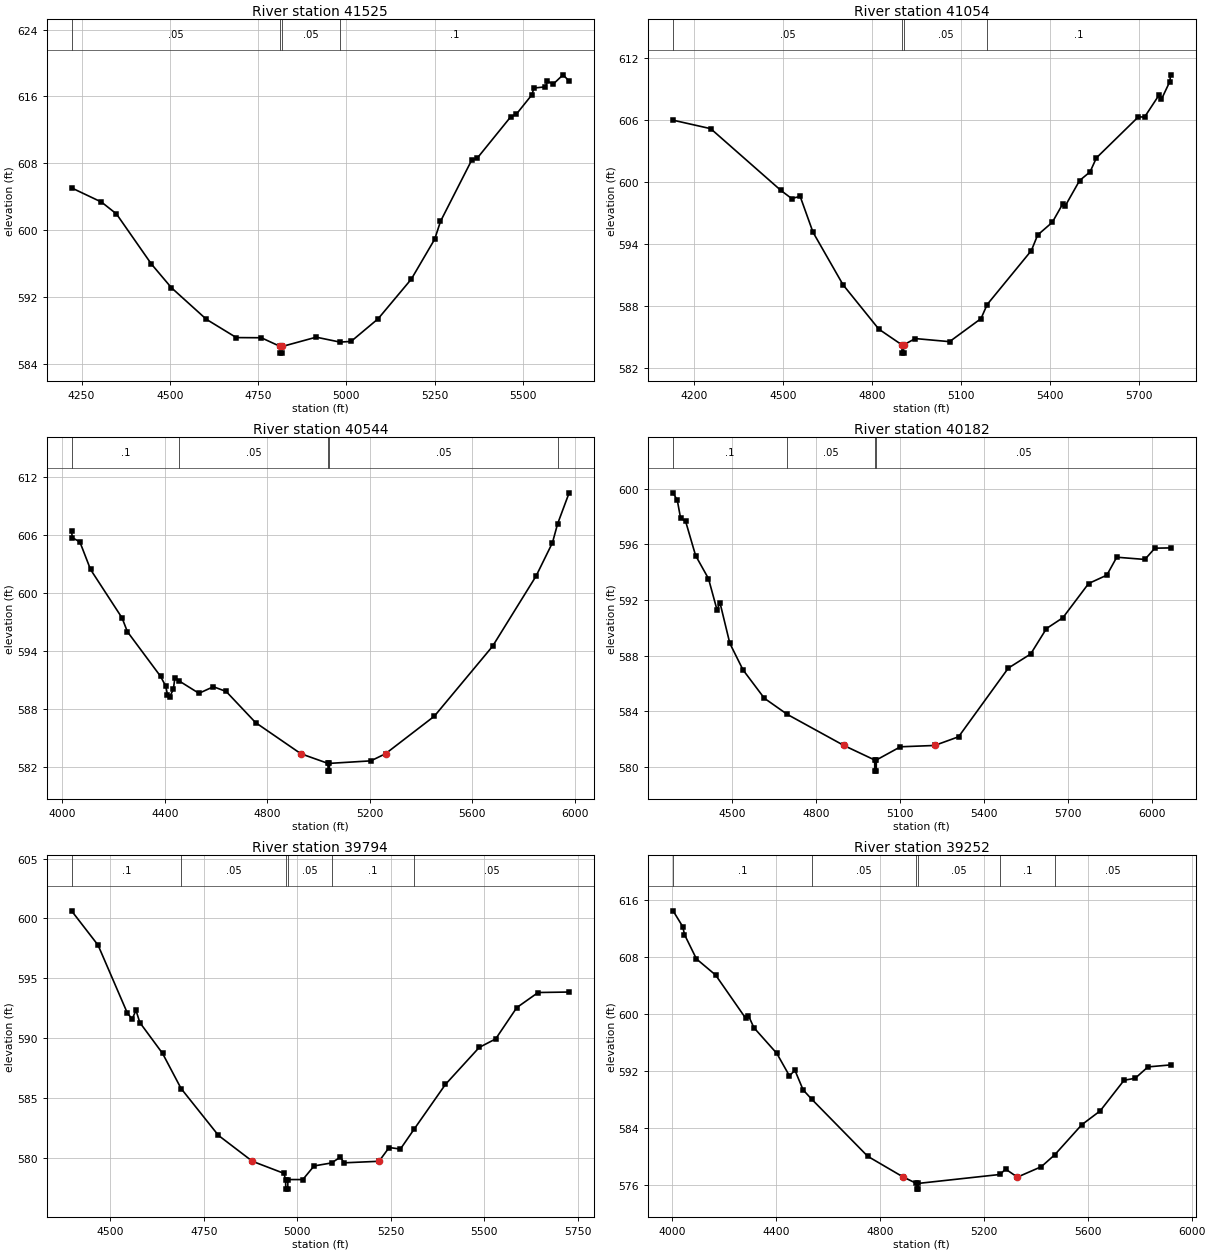
Type RM Length L Ch R = 1 ,41525   ,471,471,471
BEGIN DESCRIPTION:
UNT 022 in RCW 81.0
END DESCRIPTION:
XS GIS Cut Line= 3
      1971024.97     13474874.97        1970475.       13474325.
      1970181.27     13473766.06
#Sta/Elev= 30
  4221.7  605.06  4306.5  603.36  4348.9  601.94  4447.9  595.94  4504.5  593.11
  4603.5  589.33  4688.4  587.14  4759.1  587.12  4812.6  586.08  4813.1  585.28
  4818.1  585.28  4818.6  586.08  4914.6  587.19    4982   586.6  5013.3  586.68
  5089.9  589.39    5184  594.14  5250.2  598.92  5266.6  601.05  5354.7  608.36
  5371.1  608.64    5465  613.54  5481.4  613.88  5525.5   616.2  5531.1  617.01
  5563.9  617.15  5569.6  617.83  5585.9  617.48  5613.6  618.59  5630.9  617.85
#Mann= 4 ,-1 , 0
  4221.7     .05       0  4812.6     .07       0  4818.6     .05       0
    4982      .1       0
Bank Sta=4812.6,4818.6
XS Rating Curve= 0 ,0
Exp/Cntr=0.3,0.1

Type RM Length L Ch R = 1 ,41054   ,510,510,510
BEGIN DESCRIPTION:
UNT 022 in RCW 80.0
END DESCRIPTION:
XS GIS Cut Line= 3
      1971384.39     13474930.11        1970875.       13474175.
      1970329.85     13473635.98
#Sta/Elev= 30
    4129  605.94  4255.8  605.12  4492.7  599.14  4528.7  598.36  4557.4  598.57
  4600.7   595.1  4702.1  590.01  4822.7  585.72  4900.4   584.2  4900.9   583.4
  4905.9   583.4  4906.4   584.2  4945.5  584.81  5061.1  584.51  5167.1  586.74
  5187.8   588.1  5336.8  593.32  5358.1  594.83  5407.5  596.06  5442.9  597.85
    5450  597.59  5499.5   600.1  5534.8  600.94  5556.1  602.29  5697.5  606.26
  5718.7  606.25  5768.2  608.41  5775.2  607.95  5803.5  609.67  5806.5  610.33
#Mann= 4 ,-1 , 0
    4129     .05       0  4900.4    .035       0  4906.4     .05       0
  5187.8      .1       0
Bank Sta=4900.4,4906.4
XS Rating Curve= 0 ,0
Exp/Cntr=0.3,0.1

Type RM Length L Ch R = 1 ,40544   ,362,362,362
BEGIN DESCRIPTION:
UNT 022 in RCW 79.0
END DESCRIPTION:
XS GIS Cut Line= 3
      1971920.86     13474904.09        1971225.       13473975.
      1970712.55     13473385.88
#Sta/Elev= 30
  4035.9  606.34  4039.2  605.68  4068.3  605.26    4110  602.41    4233  597.41
  4253.8  595.99    4383  591.39  4403.8  590.35  4410.1  589.48  4418.4  589.25
    4433  590.03  4439.2  591.22  4455.5  590.91    4533  589.63  4589.3  590.31
  4639.3  589.82  4753.9  586.61 4930.81583.3935  5036.4   582.4  5036.9   581.6
  5041.9   581.6  5042.4   582.4  5203.8  582.66 5260.96583.3934  5451.6  587.27
  5678.6  594.48  5848.5  601.73  5912.4  605.17  5932.4  607.11  5977.5  610.32
#Mann= 5 ,-1 , 0
  4035.9      .1       0  4455.5     .05       0  5036.4    .035       0
  5042.4     .05       0  5932.4      .1       0
Bank Sta=4930.81,5260.96
XS Rating Curve= 0 ,0
Exp/Cntr=0.3,0.1

Type RM Length L Ch R = 1 ,40182   ,388,388,388
BEGIN DESCRIPTION:
UNT 022 in RCW 78.0
END DESCRIPTION:
XS GIS Cut Line= 3
      1971928.68     13474648.89        1971575.       13473825.
      1971056.27     13473115.01
#Sta/Elev= 30
  4290.2   599.7  4305.3  599.16  4316.9  597.89    4335  597.65  4370.6  595.19
  4416.6  593.53  4446.8   591.3  4457.7  591.79  4492.7  588.88  4539.8  586.97
  4615.9  584.93  4697.8  583.77  4899.8581.5351  5009.7  580.49  5010.2  579.69
  5015.2  579.69  5015.7  580.49  5101.6  581.44 5223.74581.5351  5309.2  582.16
  5486.8   587.1  5566.4  588.11  5622.8  589.94  5681.4  590.72  5773.3  593.18
  5838.2  593.78  5873.7  595.07  5974.1  594.91  6009.7  595.72  6066.1  595.74
#Mann= 4 ,-1 , 0
  4290.2      .1       0  4697.8     .05       0  5009.7    .035       0
  5015.7     .05       0
Bank Sta=4899.8,5223.74
XS Rating Curve= 0 ,0
Exp/Cntr=0.3,0.1

Type RM Length L Ch R = 1 ,39794   ,542,542,542
BEGIN DESCRIPTION:
UNT 022 in RCW 77.0
END DESCRIPTION:
XS GIS Cut Line= 3
        1972075.     13474574.97        1971975.       13473975.
      1971913.04     13473255.61
#Sta/Elev= 30
  4396.3  600.63  4467.2  597.76  4545.8  592.06  4558.5  591.59  4568.6  592.31
  4578.8  591.29  4639.6  588.71  4689.2  585.77  4789.1  581.85 4879.72579.6887
    4964  578.68  4968.5  578.16    4969  577.36  4974.2  577.36  4974.7  578.16
  5014.6  578.16  5044.7   579.3  5091.5  579.55    5115  580.04    5125  579.56
 5218.37579.6887  5245.4  580.84  5275.5  580.71  5311.9  582.36    5396  586.12
  5486.3  589.21  5530.2  589.92  5586.7  592.54  5643.7   593.8  5726.6  593.84
#Mann= 6 ,-1 , 0
  4396.3      .1       0  4689.2     .05       0  4968.5    .035       0
  4974.7     .05       0  5091.5      .1       0  5311.9     .05       0
Bank Sta=4879.72,5218.37
XS Rating Curve= 0 ,0
Exp/Cntr=0.3,0.1

Type RM Length L Ch R = 1 ,39252   ,653,653,653
BEGIN DESCRIPTION:
UNT 022 in RCW 76.0
END DESCRIPTION:
XS GIS Cut Line= 3
      1972814.08     13474940.52      1972405.23     13473695.74
      1971998.98     13473247.83
#Sta/Elev= 30
  4004.3  614.53  4041.7   612.3  4048.2   611.2  4094.3  607.78    4168  605.52
  4283.8  599.45  4294.3  599.82  4315.4  598.13  4403.4  594.53  4452.2  591.37
  4473.2  592.16  4504.8   589.4  4538.3  588.08  4753.3  580.09  4890.7577.1617
    4941  576.28  4941.5  575.48  4946.8  575.48  4947.3  576.28  5263.2  577.54
  5283.7   578.3 5329.25 577.162  5421.6  578.63  5473.1   580.3    5577  584.51
    5648  586.46  5739.9  590.76  5782.5  591.03  5831.8  592.63  5919.2  592.91
#Mann= 6 ,-1 , 0
  4004.3      .1       0  4538.3     .05       0    4941    .035       0
  4947.3     .05       0  5263.2      .1       0  5473.1     .05       0
Bank Sta=4890.7,5329.25
XS Rating Curve= 0 ,0
Exp/Cntr=0.3,0.1

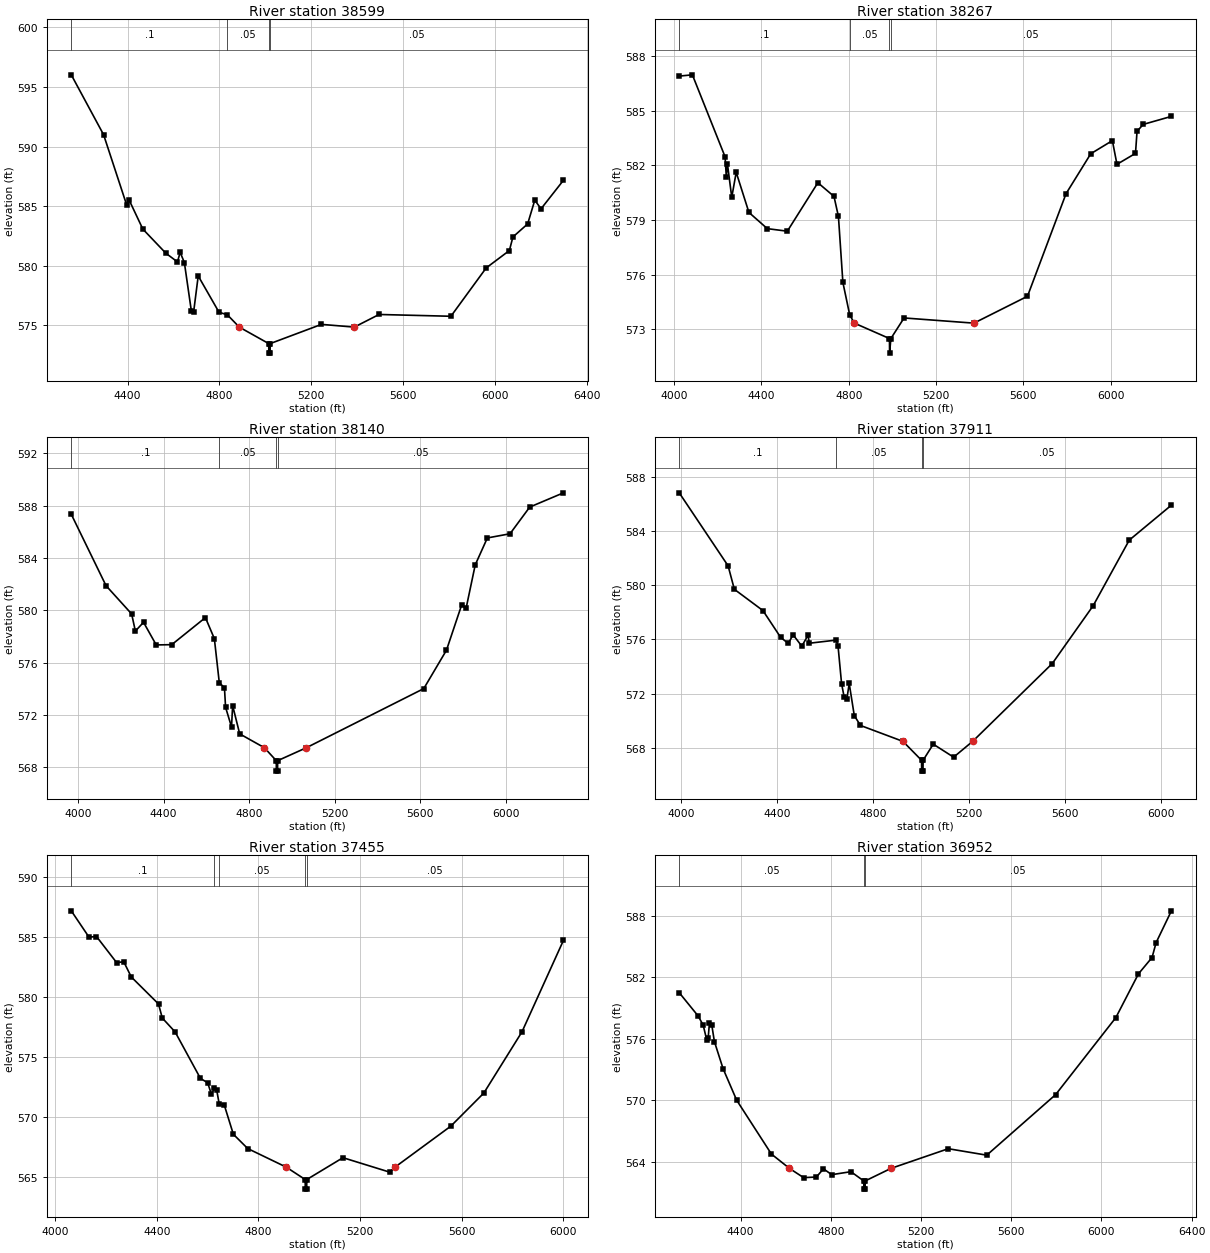
Type RM Length L Ch R = 1 ,38599   ,332,332,332
BEGIN DESCRIPTION:
UNT 022 in RCW 75.0
END DESCRIPTION:
XS GIS Cut Line= 4
      1973110.96     13474615.02      1973181.27     13473943.13
      1972801.06     13473486.88      1972051.06     13473036.89
#Sta/Elev= 30
  4154.7  596.01  4295.5  590.99    4396   585.1  4406.1  585.54  4466.4  583.08
    4567  581.05  4617.2  580.33  4629.1  581.13  4647.4  580.27  4677.6  576.24
  4687.6  576.11  4707.7  579.15  4798.2  576.11  4834.7  575.89 4886.64574.8617
  5014.9  573.48  5015.4  572.68  5020.8  572.68  5021.3  573.48  5244.6  575.09
 5387.73574.8618  5495.6  575.92  5808.5  575.77  5962.1  579.82  6063.2  581.28
  6078.7  582.42  6142.8  583.51  6173.9   585.5  6201.2  584.78  6298.8  587.17
#Mann= 4 ,-1 , 0
  4154.7      .1       0  4834.7     .05       0  5014.9    .035       0
  5021.3     .05       0
Bank Sta=4886.64,5387.73
XS Rating Curve= 0 ,0
Exp/Cntr=0.3,0.1

Type RM Length L Ch R = 1 ,38267   ,127,127,127
BEGIN DESCRIPTION:
UNT 022 in RCW 74.0
END DESCRIPTION:
XS GIS Cut Line= 3
      1973248.98     13474461.36      1973397.42     13473693.13
      1972363.57     13472643.67
#Sta/Elev= 30
  4023.2   586.9  4083.5  586.97  4233.4  582.47  4238.9  581.38    4244  582.09
  4263.9  580.25  4284.3  581.62  4342.6  579.42  4426.9  578.53  4518.6  578.39
  4658.6  581.05  4732.4   580.3  4752.8   579.2  4773.2  575.58  4804.6  573.79
 4826.06573.3451  4986.7   572.5  4987.2   571.7  4993.1   572.5  5053.6  573.63
 5373.79 573.345  5619.2  574.82    5796  580.45  5909.2  582.64  6008.2  583.36
  6029.3  582.06  6114.2  582.66  6121.3  583.87  6149.6  584.25  6278.8  584.69
#Mann= 4 ,-1 , 0
  4023.2      .1       0  4804.6     .05       0  4986.7     .04       0
  4993.1     .05       0
Bank Sta=4826.06,5373.79
XS Rating Curve= 0 ,0
Exp/Cntr=0.3,0.1

Type RM Length L Ch R = 1 ,38140   ,229,229,229
BEGIN DESCRIPTION:
Mapping XS 4a427f9a
END DESCRIPTION:
XS GIS Cut Line= 3
      1973282.83     13474424.93      1973519.81     13473641.05
      1972480.72     13472586.34
#Sta/Elev= 30
  3968.9  587.34  4131.3  581.88  4250.9  579.72  4268.3  578.41  4306.5  579.08
  4365.8  577.35  4438.3  577.37  4595.6  579.44  4637.4  577.83  4660.4  574.47
  4684.6  574.07  4689.8  572.58  4717.6  571.08  4722.8  572.71  4755.7  570.55
 4871.16569.4903  4926.7   568.5  4927.2   567.7  4932.6   567.7  4933.1   568.5
 5067.44569.4904  5615.8  574.01  5721.9  576.95  5792.6   580.4  5813.8  580.17
  5856.2  583.47  5912.8  585.53  6018.8  585.85  6110.8  587.89  6268.4  588.98
#Mann= 4 ,-1 , 0
  3968.9      .1       0  4660.4     .05       0  4926.7     .04       0
  4933.1     .05       0
Bank Sta=4871.16,5067.44
XS Rating Curve= 0 ,0
Exp/Cntr=0.3,0.1

Type RM Length L Ch R = 1 ,37911   ,456,456,456
BEGIN DESCRIPTION:
UNT 022 in RCW 73.0
END DESCRIPTION:
XS GIS Cut Line= 3
      1973324.51     13474424.86      1973579.71     13473682.72
      1973673.44     13472419.88
#Sta/Elev= 30
  3993.7  586.82  4197.4  581.43  4223.4   579.7  4342.5  578.13  4416.5  576.15
  4448.3   575.7    4468  576.35  4504.5   575.5  4530.5  576.31  4535.8  575.72
  4647.5  575.95  4655.4  575.53  4670.3  572.73  4680.9  571.76    4692  571.57
  4702.1  572.75  4723.2  570.38  4749.1  569.65 4926.11568.4756  5003.6  567.08
  5004.1  566.28  5009.5  566.28    5010  567.08  5052.3  568.27  5137.2  567.31
 5216.49568.4755  5548.3  574.22  5718.8  578.49  5869.2  583.33  6044.8  585.91
#Mann= 4 ,-1 , 0
  3993.7      .1       0  4647.5     .05       0  5003.6    .035       0
    5010     .05       0
Bank Sta=4926.11,5216.49
XS Rating Curve= 0 ,0
Exp/Cntr=0.3,0.1

Type RM Length L Ch R = 1 ,37455   ,503,503,503
BEGIN DESCRIPTION:
UNT 022 in RCW 72.0
END DESCRIPTION:
XS GIS Cut Line= 3
      1973413.03     13474461.38      1974040.64     13473565.53
      1974038.04     13472721.75
#Sta/Elev= 30
  4063.7  587.22  4133.4  585.03    4163  585.08  4242.4   582.9  4270.2  582.98
  4299.9  581.71  4407.1  579.46  4421.9  578.29  4472.5  577.13  4572.1  573.26
  4600.7  572.89  4615.5  571.92  4627.3  572.44  4636.4  572.26    4646  571.14
    4666  571.04  4701.8   568.6  4758.4  567.41 4909.95565.8632  4984.5  564.83
    4985  564.03  4990.4  564.03  4990.9  564.83  5133.3  566.65    5318  565.44
 5338.24565.8633    5558  569.28    5688  572.04  5838.1  577.14  6001.3  584.76
#Mann= 5 ,-1 , 0
  4063.7      .1       0  4627.3     .08       0    4646     .05       0
  4984.5    .035       0  4990.9     .05       0
Bank Sta=4909.95,5338.24
XS Rating Curve= 0 ,0
Exp/Cntr=0.3,0.1

Type RM Length L Ch R = 1 ,36952   ,386,386,386
BEGIN DESCRIPTION:
UNT 022 in RCW 71.0
END DESCRIPTION:
XS GIS Cut Line= 3
      1974720.32     13474682.69      1974384.39      13474047.3
      1974254.24     13472589.53
#Sta/Elev= 30
  4127.9  580.51  4212.1  578.23  4234.2  577.34  4249.7  575.91  4256.2  576.09
  4261.8  577.54  4272.3  577.35  4283.8  575.75  4322.2  573.11  4382.6  570.03
  4536.6  564.78 4616.58563.3831  4679.4  562.48  4736.1  562.54  4767.4  563.34
    4804  562.77  4889.1  563.06  4946.1  562.16  4946.6  561.36    4952  561.36
  4952.5  562.16 5066.97563.3832  5320.8   565.3  5491.5  564.67  5796.7  570.57
  6063.8  578.08  6164.2  582.35  6224.4  583.94  6242.4  585.39  6310.2  588.49
#Mann= 3 ,-1 , 0
  4127.9     .05       0  4946.1    .035       0  4952.5     .05       0
Bank Sta=4616.58,5066.97
XS Rating Curve= 0 ,0
Exp/Cntr=0.3,0.1

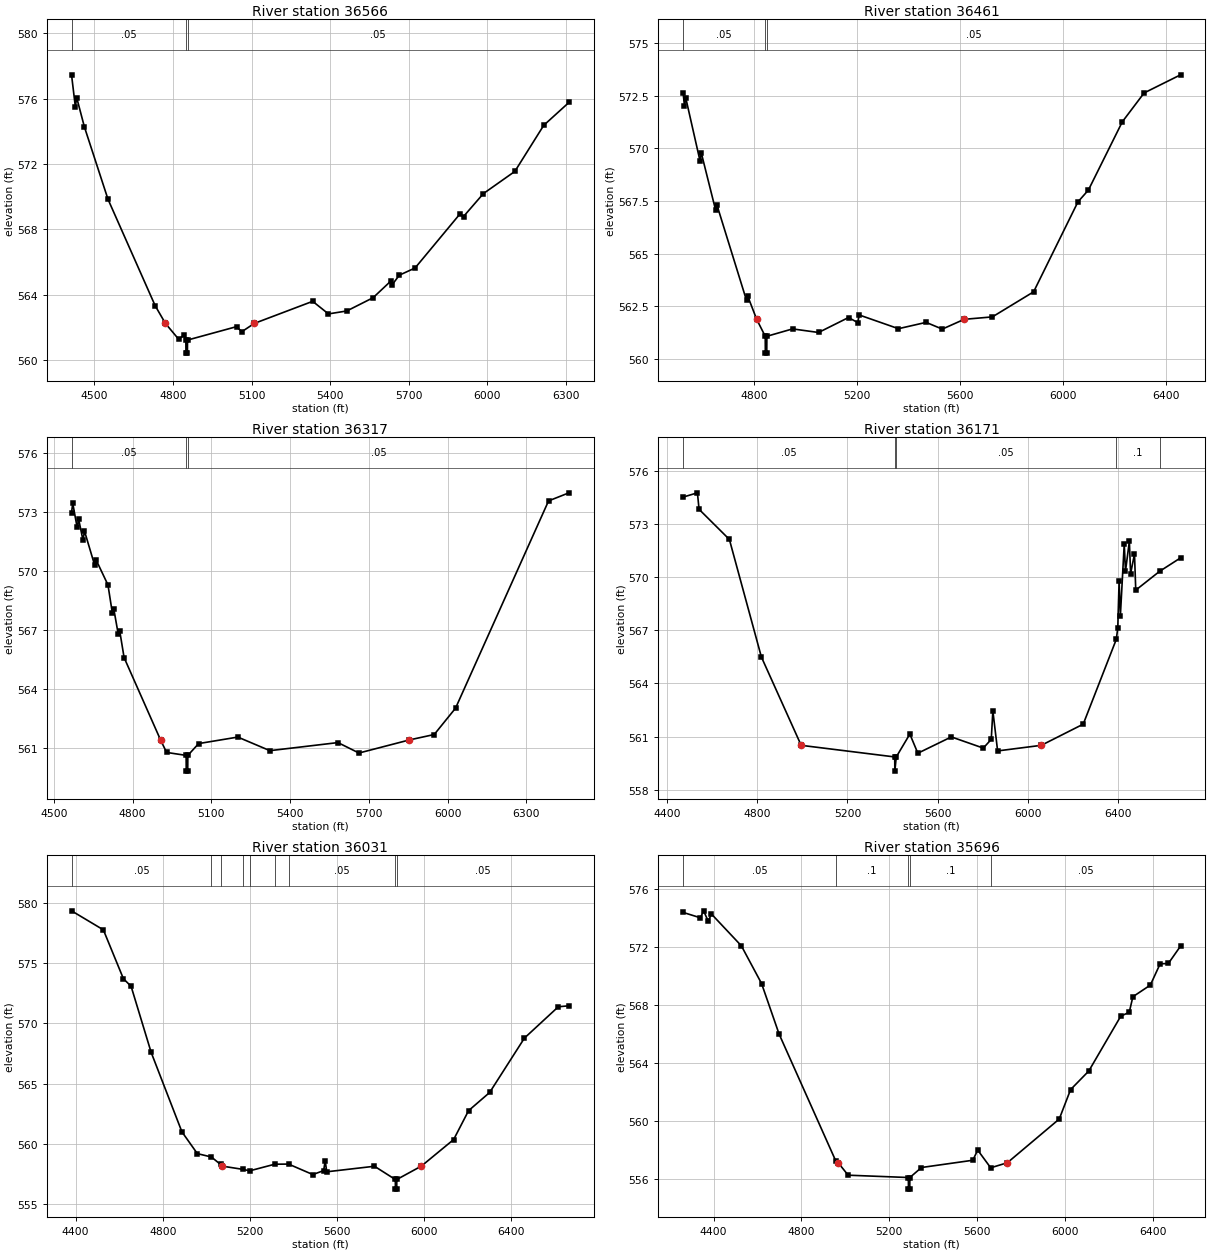
Type RM Length L Ch R = 1 ,36566   ,105,105,105
BEGIN DESCRIPTION:
UNT 022 in RCW 70.0
END DESCRIPTION:
XS GIS Cut Line= 3
      1974689.08     13474523.88        1974725.       13473925.
      1974819.22     13472628.97
#Sta/Elev= 30
  4412.7  577.46  4427.3   575.5  4432.3  576.07  4461.7  574.28  4551.8  569.85
  4732.1  563.33 4771.22562.2479  4822.3  561.27  4842.3  561.55  4849.2  561.23
  4849.7  560.43  4855.1  560.43  4855.6  561.23  5042.7  562.05  5062.8  561.74
 5110.59562.2477  5333.5   563.6  5393.7  562.83  5463.8  563.01  5564.1  563.82
  5631.3  564.83  5636.3   564.6  5664.4   565.2  5724.5  565.64    5895  568.93
  5909.5  568.79  5985.2  570.19  6105.5  571.55  6215.8  574.37  6312.1  575.77
#Mann= 3 ,-1 , 0
  4412.7     .05       0  4849.2    .035       0  4855.6     .05       0
Bank Sta=4771.22,5110.59
XS Rating Curve= 0 ,0
Exp/Cntr=0.3,0.1

Type RM Length L Ch R = 1 ,36461   ,144,144,144
BEGIN DESCRIPTION:
Mapping XS ece8405d
END DESCRIPTION:
XS GIS Cut Line= 4
      1974718.76       13474423.       1974788.2     13474013.28
      1975229.18     13473370.92      1975354.17     13472641.77
#Sta/Elev= 30
  4522.9  572.63  4528.1  572.02  4533.2  572.39  4588.5  569.41  4593.6  569.78
  4648.8  567.09  4653.9  567.33  4769.5  562.78  4774.6  562.97 4808.93561.8844
  4842.2  561.08  4842.7  560.28  4848.1  560.28  4848.6  561.08  4948.5  561.43
  5049.6  561.26  5166.1  561.97  5201.9  561.73    5208  562.09  5360.3  561.44
  5467.9  561.74  5530.8  561.42 5615.98561.8844  5725.6     562    5886  563.19
  6058.4  567.46    6099  568.02  6230.9  571.26  6315.7  572.63  6457.4  573.49
#Mann= 3 ,-1 , 0
  4522.9     .05       0  4842.2    .035       0  4848.6     .05       0
Bank Sta=4808.93,5615.98
XS Rating Curve= 0 ,0
Exp/Cntr=0.3,0.1

Type RM Length L Ch R = 1 ,36317   ,146,146,146
BEGIN DESCRIPTION:
Mapping XS e078664e
END DESCRIPTION:
XS GIS Cut Line= 4
      1974729.15     13474426.52      1974868.06      13474148.7
      1975465.29     13473291.06      1975548.33      13472758.2
#Sta/Elev= 30
  4567.7  572.96  4572.3  573.44  4589.1  572.21  4594.7  572.63  4611.4  571.56
    4617  572.03  4656.1  570.28  4661.7  570.55  4706.5  569.29  4723.2  567.86
  4728.8  568.06  4745.6  566.79  4751.2  566.96  4767.9   565.6 4906.75561.4159
  4929.8  560.78  5004.2  560.63  5004.7  559.83  5010.3  559.83  5010.8  560.63
    5052  561.23  5201.2  561.56  5323.4  560.87  5582.6  561.28  5662.7  560.75
 5855.09561.4159  5949.4  561.69  6030.7  563.03    6385  573.56  6462.7  573.97
#Mann= 3 ,-1 , 0
  4567.7     .05       0  5004.2    .035       0  5010.8     .05       0
Bank Sta=4906.75,5855.09
XS Rating Curve= 0 ,0
Exp/Cntr=0.3,0.1

Type RM Length L Ch R = 1 ,36171   ,140,140,140
BEGIN DESCRIPTION:
Mapping XS 9a9c190b
END DESCRIPTION:
XS GIS Cut Line= 4
      1974709.91      13474479.6      1975220.33     13473935.32
      1975788.04      13473359.8      1976066.69     13472773.86
#Sta/Elev= 30
  4472.1  574.51  4535.4  574.75  4542.7  573.82    4677  572.12  4818.7  565.49
    4995560.5057  5409.4  559.85  5409.9  559.05  5416.2  559.85  5476.4  561.14
  5511.8  560.06  5660.2  560.98  5801.6  560.35    5837  560.84  5844.1  562.45
  5865.2  560.19 6058.71560.5059  6244.4   561.7  6390.8  566.48  6397.4  567.11
  6403.4  569.79  6408.9   567.8  6426.1  571.87  6431.6  570.33  6448.8  572.02
  6454.3  570.19  6471.5   571.3  6477.1  569.26  6582.6  570.32  6675.5  571.08
#Mann= 5 ,-1 , 0
  4472.1     .05       0  5409.4    .035       0  5416.2     .05       0
  6390.8      .1       0  6582.6     .05       0
Bank Sta=4995,6058.71
XS Rating Curve= 0 ,0
Exp/Cntr=0.3,0.1

Type RM Length L Ch R = 1 ,36031   ,335,335,335
BEGIN DESCRIPTION:
UNT 022 in RCW 69.0
END DESCRIPTION:
XS GIS Cut Line= 3
      1974770.66     13474537.34      1975879.62     13473400.17
      1976174.76     13472770.82
#Sta/Elev= 30
  4381.5  579.35  4527.6  577.77  4619.6  573.71  4654.9  573.08    4747  567.59
  4888.2  560.99    4959  559.18  5023.4   558.9  5065.6  558.28 5071.89558.1445
  5168.9  557.87  5199.2  557.75  5314.4   558.3  5377.8  558.31  5489.3  557.44
  5538.9  557.77  5545.9  558.59  5553.1  557.67  5772.2  558.13  5867.9  557.03
  5868.4  556.23  5874.2  556.23  5874.7  557.03 5987.61558.1445  6135.7  560.35
  6204.2  562.75    6301  564.26  6460.7  568.78  6616.2  571.38    6665  571.46
#Mann= 9 ,-1 , 0
  4381.5     .05       0  5023.4      .1       0  5065.6     .05       0
  5168.9      .1       0  5199.2     .05       0  5314.4      .1       0
  5377.8     .05       0  5867.9     .04       0  5874.7     .05       0
Bank Sta=5071.89,5987.61
XS Rating Curve= 0 ,0
Exp/Cntr=0.3,0.1

Type RM Length L Ch R = 1 ,35696   ,251,251,251
BEGIN DESCRIPTION:
UNT 022 in RCW 68.0
END DESCRIPTION:
XS GIS Cut Line= 3
      1975094.29     13474724.13        1975525.       13474125.
      1976215.99     13472762.15
#Sta/Elev= 30
  4261.6  574.38  4340.2  574.01    4355  574.49  4375.9  573.77  4390.6  574.27
  4526.8  572.08  4618.9  569.48  4698.7     566  4957.3  557.24  4967.8  557.13
  5013.4  556.27  5287.6  556.11  5288.1  555.31  5293.9  555.31  5294.4  556.11
  5347.4   556.8  5581.2   557.3  5603.5     558  5662.7  556.78 5738.73557.1298
  5974.9  560.14  6026.6  562.17  6109.5  563.45  6255.2  567.23  6293.8   567.5
  6310.4  568.57  6389.8  569.37  6434.6  570.84  6471.9  570.86  6527.5  572.06
#Mann= 5 ,-1 , 0
  4261.6     .05       0  4957.3      .1       0  5287.6     .07       0
  5294.4      .1       0  5662.7     .05       0
Bank Sta=4967.8,5738.73
XS Rating Curve= 0 ,0
Exp/Cntr=0.3,0.1

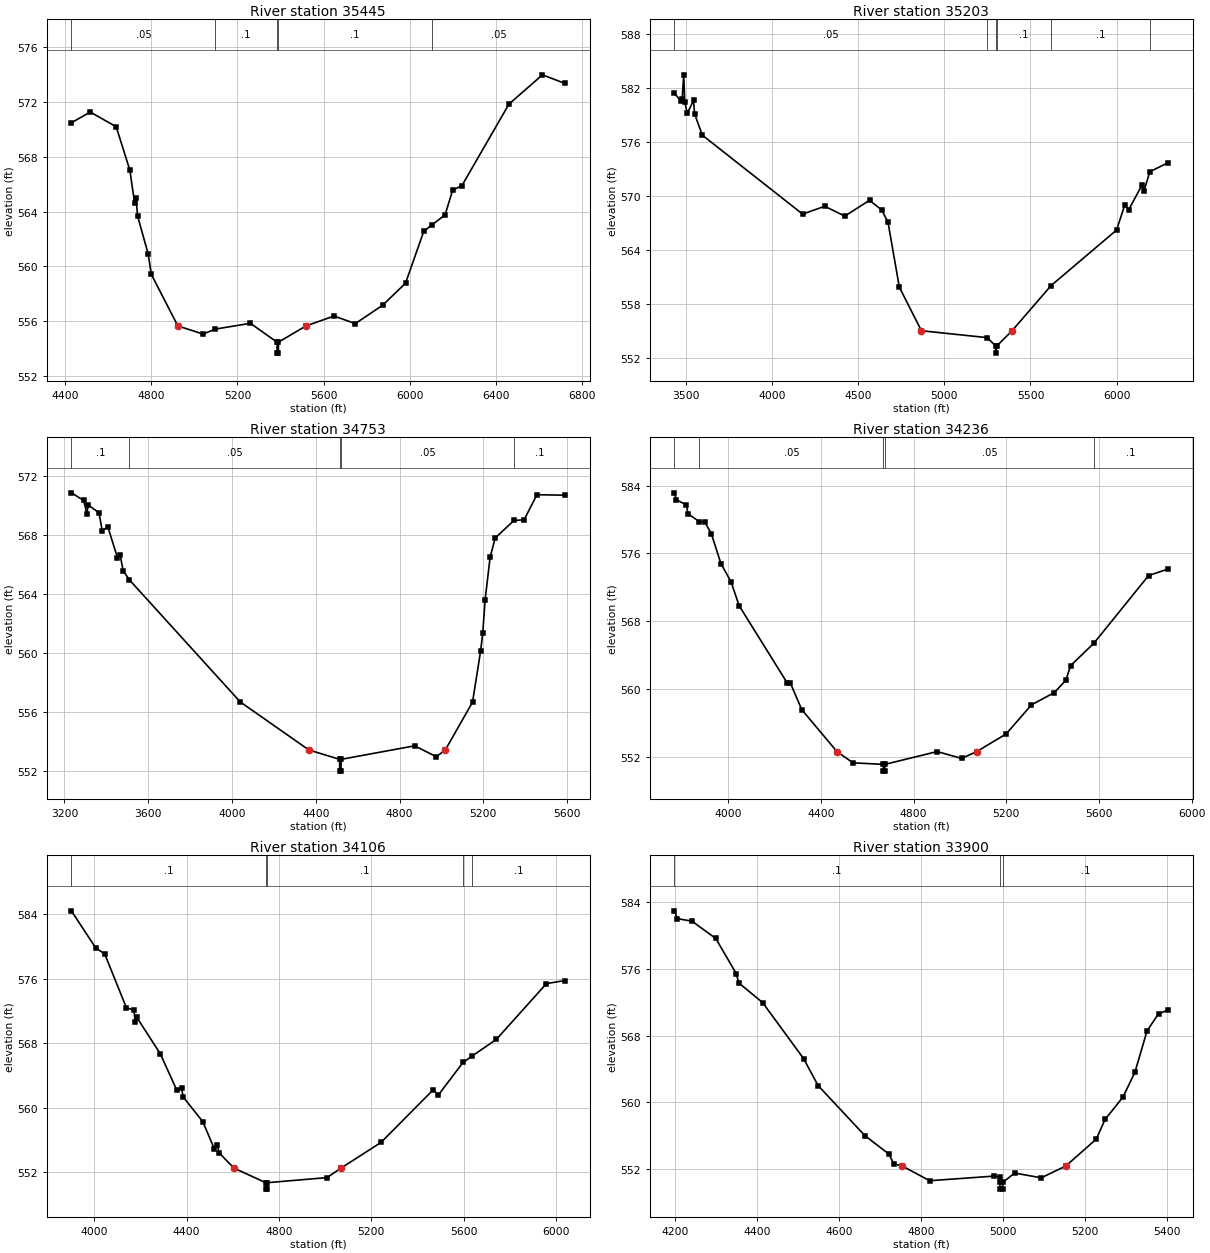
Type RM Length L Ch R = 1 ,35445   ,242,242,242
BEGIN DESCRIPTION:
Mapping XS 84c80bcc
END DESCRIPTION:
XS GIS Cut Line= 3
      1975382.49     13474547.04      1975983.21      13473873.4
      1976969.32     13472890.77
#Sta/Elev= 30
  4427.9  570.46    4516  571.24  4636.4  570.17    4700     567  4721.7  564.63
  4728.4  564.95  4735.9  563.66  4785.2   560.9  4799.4  559.43 4922.97555.6691
  5040.2  555.08  5096.9  555.44  5260.1  555.86  5383.8  554.49  5384.3  553.69
  5390.1  553.69  5390.6  554.49 5518.32555.6691  5648.8  556.39  5747.8  555.84
  5875.1  557.18  5981.2  558.78    6066  562.56  6102.4  563.01    6165  563.75
  6200.4  565.57  6242.8  565.87    6462  571.82  6617.6  573.95  6722.6  573.32
#Mann= 5 ,-1 , 0
  4427.9     .05       0  5096.9      .1       0  5383.8    .035       0
  5390.6      .1       0  6102.4     .05       0
Bank Sta=4922.97,5518.32
XS Rating Curve= 0 ,0
Exp/Cntr=0.3,0.1

Type RM Length L Ch R = 1 ,35203   ,450,450,450
BEGIN DESCRIPTION:
UNT 022 in RCW 67.0
END DESCRIPTION:
XS GIS Cut Line= 3
       1974688.1     13475112.96        1975975.       13474225.
      1977174.99     13473725.01
#Sta/Elev= 30
  3434.2  581.42  3473.8  580.49  3479.9   580.8  3488.7  583.44  3494.7  580.42
  3509.6  579.16  3545.5   580.6  3551.9  579.11  3596.2  576.75  4178.3  567.98
  4306.7  568.85    4423  567.76  4566.4  569.51    4638  568.43  4673.9  567.05
  4739.4  559.87 4867.39555.0342  5248.7  554.27  5298.2  553.35  5298.7  552.55
    5305  553.35 5393.38555.0344  5619.7  560.05  5999.3  566.21  6046.9  568.99
  6070.2  568.48    6146  571.18  6158.5  570.59  6192.6  572.69  6297.7  573.68
#Mann= 6 ,-1 , 0
  3434.2     .05       0  5248.7      .1       0  5298.2    .035       0
    5305      .1       0  5619.7      .1       0  6192.6     .05       0
Bank Sta=4867.39,5393.38
XS Rating Curve= 0 ,0
Exp/Cntr=0.3,0.1

Type RM Length L Ch R = 1 ,34753   ,517,517,517
BEGIN DESCRIPTION:
UNT 022 in RCW 66.0
END DESCRIPTION:
XS GIS Cut Line= 3
      1974858.23     13475380.33        1976375.       13474425.
      1976899.89     13474217.14
#Sta/Elev= 30
  3232.8  570.88  3291.8  570.36  3307.1  569.46    3313  570.06  3364.8  569.52
  3380.1  568.31  3407.2  568.56  3453.1  566.47  3465.3  566.68  3480.2  565.59
  3509.1  564.98  4039.4  556.67 4366.95553.4074  4513.7  552.77  4514.2  551.97
  4520.1  551.97  4520.6  552.77  4871.7  553.69  4975.3  552.95 5018.33553.4075
  5148.3  556.66  5186.7  560.12    5197  561.35  5208.2   563.6  5232.1  566.49
  5256.4  567.81  5346.5  569.01  5394.2  569.04  5455.6  570.75  5589.9  570.72
#Mann= 5 ,-1 , 0
  3232.8      .1       0  3509.1     .05       0  4513.7    .035       0
  4520.6     .05       0  5346.5      .1       0
Bank Sta=4366.95,5018.33
XS Rating Curve= 0 ,0
Exp/Cntr=0.3,0.1

Type RM Length L Ch R = 1 ,34236   ,130,130,130
BEGIN DESCRIPTION:
UNT 022 in RCW 65.0
END DESCRIPTION:
XS GIS Cut Line= 3
      1975490.16     13475713.67      1976691.54      13474748.4
       1977041.1     13474274.25
#Sta/Elev= 30
  3767.7  583.16  3776.9  582.33  3820.1  581.73  3826.5  580.69  3876.1  579.75
  3898.5  579.74  3927.3  578.34  3968.9  574.79  4012.1  572.67  4047.3  569.83
  4253.7  560.75  4268.1  560.71  4317.7  557.54 4469.72552.5836  4538.5  551.26
  4669.5  551.08    4670  550.28    4676  550.28  4676.5  551.08  4901.7  552.59
  5007.4  551.78 5072.12552.5837  5199.4  554.67  5308.8  558.11  5406.8  559.55
  5456.9  561.01  5477.8  562.75  5577.7  565.38    5814  573.38  5897.9  574.16
#Mann= 5 ,-1 , 0
  3767.7      .1       0  3876.1     .05       0  4669.5    .035       0
  4676.5     .05       0  5577.7      .1       0
Bank Sta=4469.72,5072.12
XS Rating Curve= 0 ,0
Exp/Cntr=0.3,0.1

Type RM Length L Ch R = 1 ,34106   ,206,206,206
BEGIN DESCRIPTION:
Mapping XS 874da016
END DESCRIPTION:
XS GIS Cut Line= 4
      1975583.91     13475737.98      1975861.68     13475592.15
      1976875.57     13474692.85      1977132.52     13474300.47
#Sta/Elev= 30
  3900.9  584.45  4006.8  579.83  4045.2  579.11  4139.3  572.42  4171.9  572.13
  4177.5  570.62  4184.5  571.22  4285.9  566.72  4356.5  562.26  4378.2  562.48
  4384.9  561.36  4470.2  558.28  4519.5  554.95  4533.8  555.36  4540.4  554.42
 4605.19 552.519  4742.7  550.71  4743.2  549.91  4749.2  549.91  4749.7  550.71
    5008  551.34 5068.76552.5188  5242.1  555.71  5468.8  562.26  5489.7  561.57
  5597.1  565.63  5637.4  566.45  5741.4  568.49  5958.5  575.42  6038.9   575.8
#Mann= 5 ,-1 , 0
  3900.9      .1       0  4742.7     .07       0  4749.7      .1       0
  5597.1     .05       0  5637.4      .1       0
Bank Sta=4605.19,5068.76
XS Rating Curve= 0 ,0
Exp/Cntr=0.3,0.1

Type RM Length L Ch R = 1 ,33900   ,413,413,413
BEGIN DESCRIPTION:
UNT 022 in RCW 64.0
END DESCRIPTION:
XS GIS Cut Line= 3
      1975840.87     13475762.27        1976475.       13475275.
      1976824.97     13475075.01
#Sta/Elev= 30
  4199.2     583  4206.8  582.06  4242.2  581.76  4300.2  579.68    4350  575.47
  4356.3  574.34  4414.4  571.98  4514.1  565.26  4549.4  562.02  4663.6     556
  4721.5  553.81  4734.3  552.61 4754.65552.3544  4821.3  550.59  4977.1  551.14
  4991.7  551.06  4992.3  550.38  4992.8  549.58  4998.8  549.58  4999.3  550.38
  5028.4  551.51  5093.2  550.94 5152.93552.3547  5227.1  555.58  5248.7  557.95
  5291.9  560.61  5321.4  563.61  5350.9  568.58    5379  570.65    5402  571.07
#Mann= 3 ,-1 , 0
  4199.2      .1       0  4992.3     .07       0  4999.3      .1       0
Bank Sta=4754.65,5152.93
XS Rating Curve= 0 ,0
Exp/Cntr=0.3,0.1

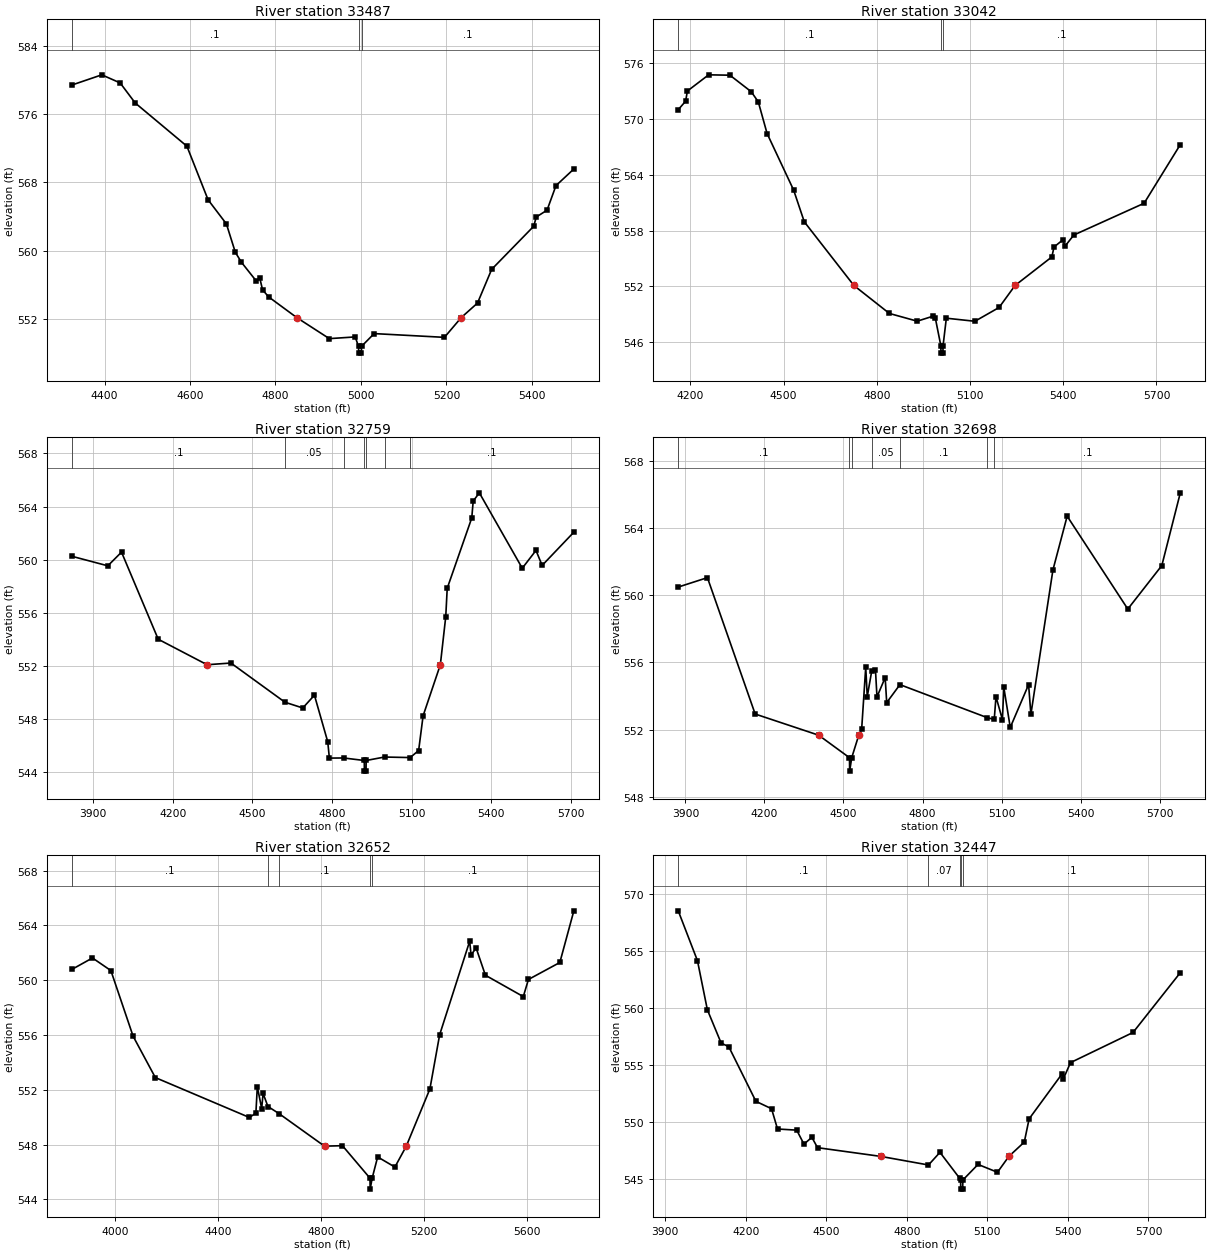
Type RM Length L Ch R = 1 ,33487   ,445,445,445
BEGIN DESCRIPTION:
UNT 022 in RCW 63.0
END DESCRIPTION:
XS GIS Cut Line= 3
      1976174.19     13476043.53        1976675.       13475625.
        1976825.     13475124.98
#Sta/Elev= 30
  4323.4  579.41  4393.7  580.61  4436.6  579.66  4471.8  577.31  4592.8  572.24
  4642.3  565.96  4685.2  563.13    4706  559.81  4720.4  558.63  4755.5  556.41
  4763.3  556.77  4769.8   555.4  4784.1  554.57 4849.56552.1555    4926  549.68
  4986.5  549.88  4994.3  548.78  4994.8  547.98  5000.9  547.98  5001.4  548.78
  5030.9  550.27  5195.3  549.83 5234.77552.1551  5272.7  553.85  5305.8   557.8
  5404.1  562.85  5410.2  563.94  5435.4  564.74  5456.3  567.62  5498.1  569.57
#Mann= 3 ,-1 , 0
  4323.4      .1       0  4994.3     .07       0  5001.4      .1       0
Bank Sta=4849.56,5234.77
XS Rating Curve= 0 ,0
Exp/Cntr=0.3,0.1

Type RM Length L Ch R = 1 ,33042   ,283,283,283
BEGIN DESCRIPTION:
UNT 022 in RCW 62.0
END DESCRIPTION:
XS GIS Cut Line= 3
      1976288.74     13476170.28        1977025.       13475825.
      1977585.67     13475250.98
#Sta/Elev= 30
  4161.1  570.98  4184.9  571.89  4190.5  572.98  4258.9  574.72  4327.4  574.68
  4395.9  572.91  4418.7  571.82    4447  568.42  4532.5  562.34  4566.7  558.94
 4726.36552.1024  4840.5   549.1  4930.1  548.27  4981.4  548.81  4988.4   548.6
  5006.1  545.64  5006.6  544.84  5012.7  544.84  5013.3  545.64  5023.8  548.59
  5115.7  548.26  5193.5  549.74 5244.93552.1025  5363.3  555.17  5370.3  556.23
  5398.6     557  5405.7  556.32    5434  557.52  5660.2  560.93  5776.7  567.23
#Mann= 3 ,-1 , 0
  4161.1      .1       0  5006.1     .07       0  5013.3      .1       0
Bank Sta=4726.36,5244.93
XS Rating Curve= 0 ,0
Exp/Cntr=0.3,0.1

Type RM Length L Ch R = 1 ,32759   ,61,61,61
BEGIN DESCRIPTION:
Mapping XS 1bd3e7a7
END DESCRIPTION:
XS GIS Cut Line= 6
      1976593.47     13476933.26      1976760.12     13476568.71
      1977020.53     13476232.78      1977189.81     13476107.78
      1977296.58     13475860.38      1977537.99     13475328.24
#Sta/Elev= 30
  3820.3  560.26    3956  559.54  4007.6  560.57  4145.7  554.02 4329.78 552.101
  4419.4  552.23    4623  549.28  4689.9  548.85  4733.8  549.81  4783.9  546.31
  4790.1  545.08  4843.5  545.09  4921.4   544.9  4921.9   544.1    4928   544.1
  4928.6   544.9  4997.6  545.16  5094.2  545.12  5126.1  545.65  5142.9  548.26
 5207.81552.1013  5228.2  555.72  5233.7  557.85  5326.1  563.14  5331.5  564.41
  5354.6  565.03  5516.2  559.36  5567.9   560.7    5591  559.57  5710.4  562.07
#Mann= 7 ,-1 , 0
  3820.3      .1       0    4623     .05       0  4843.5      .1       0
  4921.4    .033       0  4928.6      .1       0  4997.6     .05       0
  5094.2      .1       0
Bank Sta=4329.78,5207.81
XS Rating Curve= 0 ,0
Exp/Cntr=0.3,0.1

Type RM Length L Ch R = 1 ,32698   ,46,46,46
BEGIN DESCRIPTION:
Mapping XS 2fb8af5e
END DESCRIPTION:
XS GIS Cut Line= 5
      1976629.89     13476873.44      1976994.49     13476313.51
      1977236.68     13476167.67      1977356.47     13475862.98
      1977588.18     13475279.81
#Sta/Elev= 30
  3872.8  560.49  3983.6  561.05  4164.8  552.93  4405.8551.6703  4522.8  550.33
  4523.5  549.53  4531.3  550.33 4558.06551.6698    4569  552.02  4584.5  555.71
  4590.3  553.97  4607.2  555.49  4621.4  555.57  4627.2  553.95  4658.3   555.1
  4664.1  553.61  4714.3  554.68  5046.4  552.71  5072.3  552.61  5078.9  553.96
  5103.3   552.6  5108.7  554.51  5133.1  552.13  5202.7  554.68  5211.4  552.91
  5295.1  561.51  5349.1  564.71  5579.3  559.18  5708.4  561.77  5778.6   566.1
#Mann= 7 ,-1 , 0
  3872.8      .1       0  4522.8     .07       0  4531.3      .1       0
  4607.2     .05       0  4714.3      .1       0  5046.4     .05       0
  5072.3      .1       0
Bank Sta=4405.8,4558.06
XS Rating Curve= 0 ,0
Exp/Cntr=0.3,0.1

Type RM Length L Ch R = 1 ,32652   ,205,205,205
BEGIN DESCRIPTION:
UNT 022 in RCW 61.0
END DESCRIPTION:
XS GIS Cut Line= 5
      1976626.44     13476899.43      1977023.14     13476331.73
      1977278.35     13476204.13      1977405.95     13475844.76
      1977609.09     13475290.04
#Sta/Elev= 30
  3831.2  560.78  3911.6  561.62  3983.1   560.7  4069.4  555.91  4155.8  552.89
    4521  549.98  4546.3   550.3  4551.9  552.23  4568.7  550.63  4574.3  551.73
  4593.1  550.78  4636.3  550.26 4812.79547.8854  4882.5  547.92  4989.4  545.55
  4990.1  544.75  4997.9  545.55  5019.2   547.1  5086.2  546.36 5130.37547.8856
  5222.1  552.06  5259.9  556.01  5376.6  562.84    5382  561.85  5401.8  562.34
  5437.7  560.36  5584.9   558.8  5604.8  560.05  5726.8  561.29  5781.2  565.06
#Mann= 5 ,-1 , 0
  3831.2      .1       0  4593.1     .05       0  4636.3      .1       0
  4989.4     .07       0  4997.9      .1       0
Bank Sta=4812.79,5130.37
XS Rating Curve= 0 ,0
Exp/Cntr=0.3,0.1

Type RM Length L Ch R = 1 ,32447   ,310,310,310
BEGIN DESCRIPTION:
Mapping XS 048b14ec
END DESCRIPTION:
XS GIS Cut Line= 3
      1977646.38     13477092.12      1977427.65     13476727.57
      1977660.15     13475301.33
#Sta/Elev= 30
  3948.5  568.52  4020.1  564.14    4057  559.83  4108.4   556.9  4136.7  556.59
  4237.8  551.79  4296.1  551.14  4318.3  549.36  4389.8  549.26  4416.8  548.03
  4446.2  548.63  4467.4  547.72 4702.23546.9575  4880.7   546.2  4923.4  547.31
  4997.2  545.02  5000.2  544.88  5000.9  544.08  5007.9  544.08  5008.7  544.88
  5065.2  546.25  5137.6  545.56 5180.24546.9583  5237.5  548.21  5255.5  550.25
  5378.5  554.21  5383.5  553.79  5409.7  555.19  5642.7  557.84  5818.7  563.09
#Mann= 5 ,-1 , 0
  3948.5      .1       0  4880.7     .07       0  4997.2      .1       0
  5000.2     .07       0  5008.7      .1       0
Bank Sta=4702.23,5180.24
XS Rating Curve= 0 ,0
Exp/Cntr=0.3,0.1