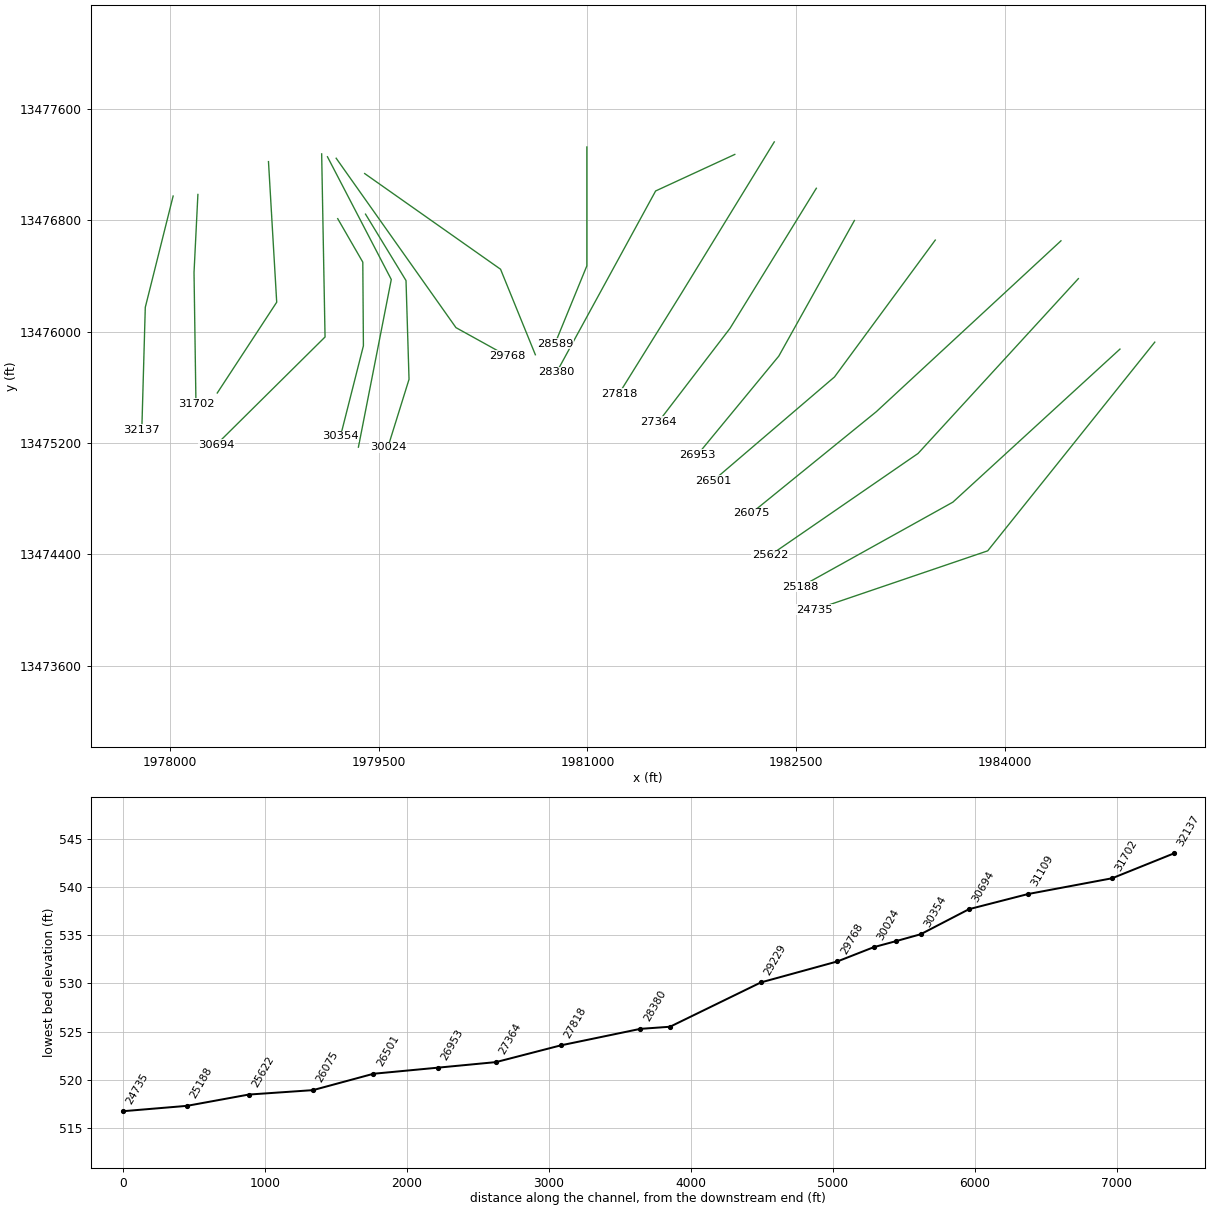
HEC-RAS study UNT 022 in RCW.prj: UNT 022 in RCW Base Level Engineering

--- UNT 022 in RCW.g01 (geometry) --- (continued)

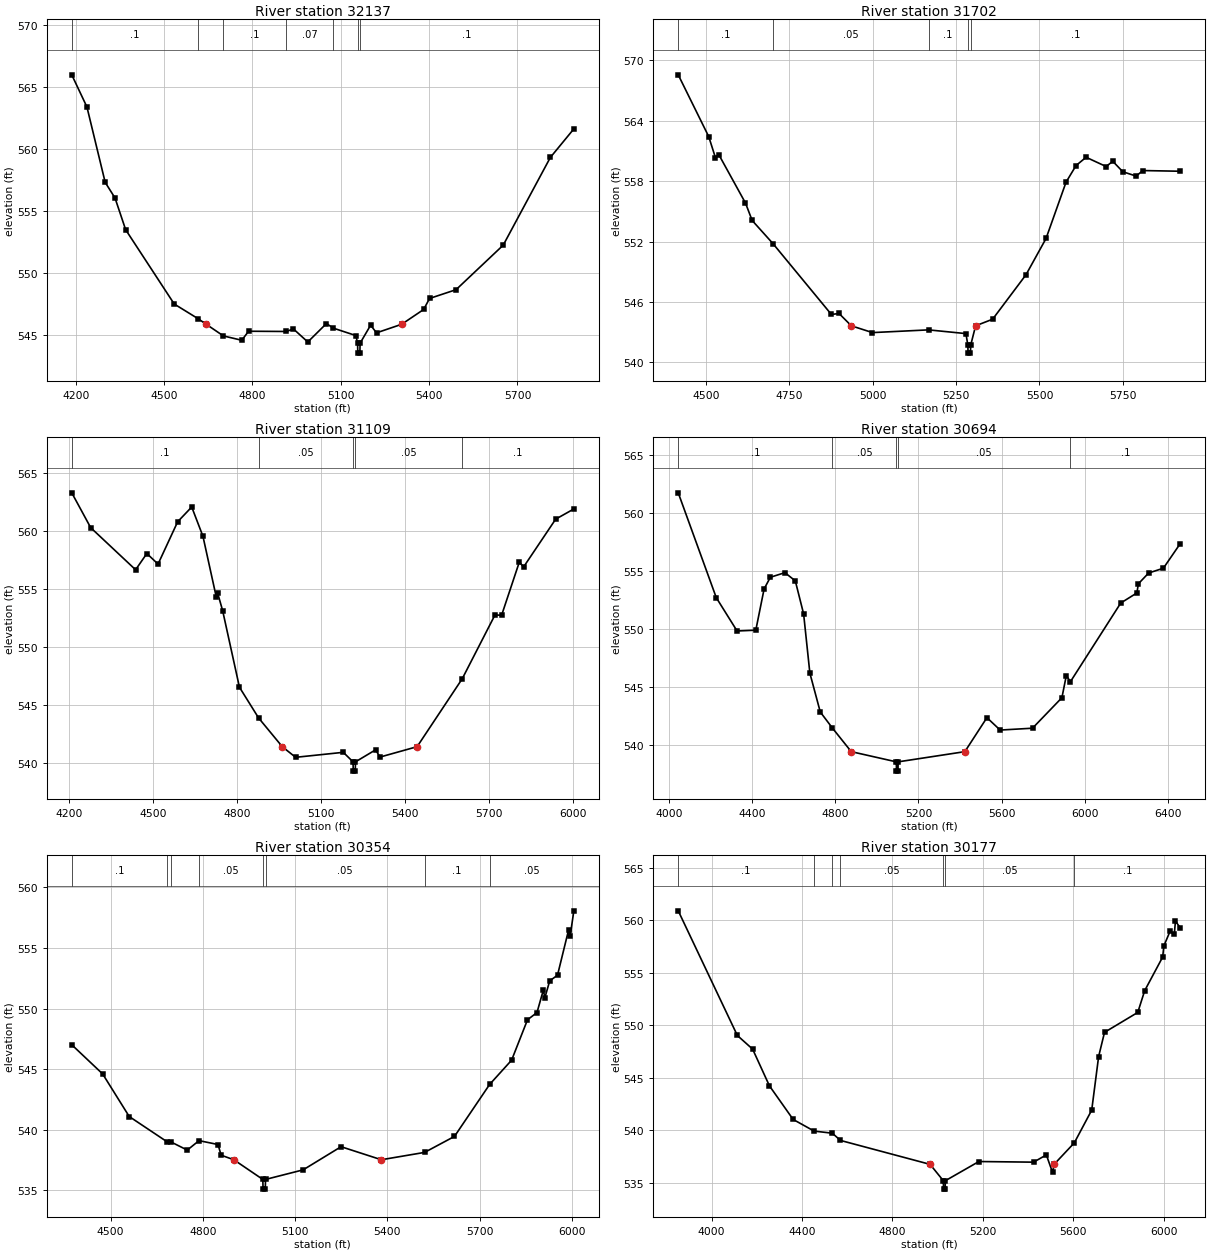
Type RM Length L Ch R = 1 ,32137   ,435,435,435
BEGIN DESCRIPTION:
UNT 022 in RCW 60.0
END DESCRIPTION:
XS GIS Cut Line= 3
        1978025.     13476974.98        1977825.       13476175.
      1977800.05     13475295.26
#Sta/Elev= 30
  4186.7     566  4238.2   563.4  4300.1  557.31  4333.6  556.04  4369.6  553.48
  4534.6  547.47  4615.8  546.28 4643.21545.8328  4701.6  544.89  4763.9  544.54
  4787.1  545.27  4915.5  545.25  4939.1  545.46  4988.1   544.4  5051.3  545.89
  5074.8  545.52  5151.4  544.92  5157.1   544.3  5157.9   543.5  5164.9   543.5
  5165.6   544.3  5201.4  545.76  5221.4  545.14 5306.89545.8328  5381.5  547.03
  5401.5  547.92  5491.5  548.63  5651.6  552.23  5811.6  559.32  5891.4  561.63
#Mann= 7 ,-1 , 0
  4186.7      .1       0  4615.8     .05       0  4701.6      .1       0
  4915.5     .07       0  5074.8      .1       0  5157.1     .07       0
  5165.6      .1       0
Bank Sta=4643.21,5306.89
XS Rating Curve= 0 ,0
Exp/Cntr=0.3,0.1

Type RM Length L Ch R = 1 ,31702   ,593,593,593
BEGIN DESCRIPTION:
UNT 022 in RCW 59.0
END DESCRIPTION:
XS GIS Cut Line= 3
      1978202.83     13476986.25        1978175.       13476425.
      1978188.94     13475482.74
#Sta/Elev= 30
  4417.6  568.57    4509  562.43    4529  560.34    4539  560.65  4619.1  555.83
  4639.1   554.1  4701.7  551.79  4876.5  544.76  4899.4  544.86 4936.25 543.634
  4999.5  542.96  5167.6  543.23  5279.6  542.86  5285.3  541.72    5286  540.92
  5293.1  540.92  5293.9  541.72 5308.59543.6341  5359.6  544.29  5459.6  548.71
  5519.6  552.31  5579.6  557.91  5609.6  559.56  5639.6  560.38  5699.6  559.46
  5719.6  559.98  5749.6  558.94  5789.6  558.51  5809.6  559.06  5921.9  558.99
#Mann= 5 ,-1 , 0
  4417.6      .1       0  4701.7     .05       0  5167.6      .1       0
  5285.3    .035       0  5293.9      .1       0
Bank Sta=4936.25,5308.59
XS Rating Curve= 0 ,0
Exp/Cntr=0.3,0.1

Type RM Length L Ch R = 1 ,31109   ,415,415,415
BEGIN DESCRIPTION:
UNT 022 in RCW 58.0
END DESCRIPTION:
XS GIS Cut Line= 3
      1978709.77     13477222.39       1978768.8     13476211.94
      1978341.96     13475559.54
#Sta/Elev= 30
  4210.8  563.26  4278.3  560.26  4438.6  556.63  4478.7  558.03  4518.7  557.12
  4588.8  560.77  4638.9  562.04    4679  559.51  4726.6  554.27  4731.6   554.6
  4749.1  553.12  4809.2  546.51  4877.6  543.86 4962.09 541.386  5009.6  540.47
  5179.8   540.9  5214.6  540.08  5215.4  539.28  5222.5  539.28  5223.3  540.08
  5295.4  541.12  5310.5  540.49 5443.22541.3859  5604.3  547.24  5721.2  552.74
  5744.8  552.71  5808.1   557.3  5823.2  556.87  5937.7  560.99  6002.6  561.87
#Mann= 5 ,-1 , 0
  4210.8      .1       0  4877.6     .05       0  5214.6    .035       0
  5223.3     .05       0  5604.3      .1       0
Bank Sta=4962.09,5443.22
XS Rating Curve= 0 ,0
Exp/Cntr=0.3,0.1

Type RM Length L Ch R = 1 ,30694   ,340,340,340
BEGIN DESCRIPTION:
UNT 022 in RCW 57.0
END DESCRIPTION:
XS GIS Cut Line= 3
      1979091.72     13477277.93      1979116.02     13475961.94
      1978335.95     13475188.81
#Sta/Elev= 30
    4045   561.7    4228  552.66    4328  549.79    4418  549.86    4458  553.42
    4488  554.42    4558  554.82    4608  554.11    4648  551.26    4678  546.16
    4728  542.81  4786.6  541.42 4877.12539.3888  5093.8  538.51  5094.6  537.71
  5101.7  537.71  5102.5  538.51 5423.34539.3887  5529.5  542.32  5593.1  541.25
  5748.7  541.41  5890.1  544.04  5911.3  545.95  5931.1  545.42    6173   552.2
  6250.7  553.07  6257.8  553.86  6307.3  554.79    6378   555.2  6459.5  557.33
#Mann= 5 ,-1 , 0
    4045      .1       0  4786.6     .05       0  5093.8     .03       0
  5102.5     .05       0  5931.1      .1       0
Bank Sta=4877.12,5423.34
XS Rating Curve= 0 ,0
Exp/Cntr=0.3,0.1

Type RM Length L Ch R = 1 ,30354   ,177,177,177
BEGIN DESCRIPTION:
Mapping XS 88f426ce
END DESCRIPTION:
XS GIS Cut Line= 4
      1979207.03     13476812.34      1979387.16     13476499.82
       1979391.5      13475898.7      1979226.88     13475248.87
#Sta/Elev= 30
    4374  547.02  4474.5  544.61  4560.8   541.1    4683  539.03  4698.2  538.98
  4749.5  538.33  4787.7  539.11  4849.5  538.79  4859.5  537.91 4900.86537.5342
  4995.1  535.91  4995.9  535.11  5003.1  535.11  5003.9  535.91  5126.2   536.7
  5249.5  538.61 5380.42537.5339    5521  538.14  5618.2  539.46  5732.5  543.75
  5803.9  545.75  5855.5  549.08  5886.4  549.68    5907  551.53  5912.1  550.91
  5927.7  552.29  5953.1  552.76    5989  556.48  5994.1  555.97  6006.2  558.07
#Mann= 8 ,-1 , 0
    4374      .1       0    4683     .05       0  4698.2      .1       0
  4787.7     .05       0  4995.1    .035       0  5003.9     .05       0
    5521      .1       0  5732.5     .05       0
Bank Sta=4900.86,5380.42
XS Rating Curve= 0 ,0
Exp/Cntr=0.3,0.1

Type RM Length L Ch R = 1 ,30177   ,153,153,153
BEGIN DESCRIPTION:
UNT 022 in RCW 56.0
END DESCRIPTION:
XS GIS Cut Line= 3
      1979133.38     13477257.09      1979591.72     13476375.14
      1979355.61     13475170.29
#Sta/Elev= 30
  3852.6   560.9  4114.2  549.02  4181.8  547.72  4256.2  544.22  4361.1  541.02
  4453.9  539.91  4534.4  539.71  4570.6  539.02 4967.05536.7401  5025.7  535.18
  5026.5  534.38  5033.7  534.38  5034.5  535.18    5183  537.01  5424.9  536.95
  5481.5  537.64    5509  535.97 5515.77536.7399  5605.2  538.79  5682.3  541.91
  5712.8  547.01  5738.9  549.32  5886.1  551.22  5916.6  553.29  5996.3   556.5
  6001.4  557.55  6028.7  558.94  6047.7  558.68  6052.8  559.93  6074.3  559.26
#Mann= 7 ,-1 , 0
  3852.6      .1       0  4453.9     .05       0  4534.4      .1       0
  4570.6     .05       0  5025.7     .03       0  5034.5     .05       0
  5605.2      .1       0
Bank Sta=4967.05,5515.77
XS Rating Curve= 0 ,0
Exp/Cntr=0.3,0.1

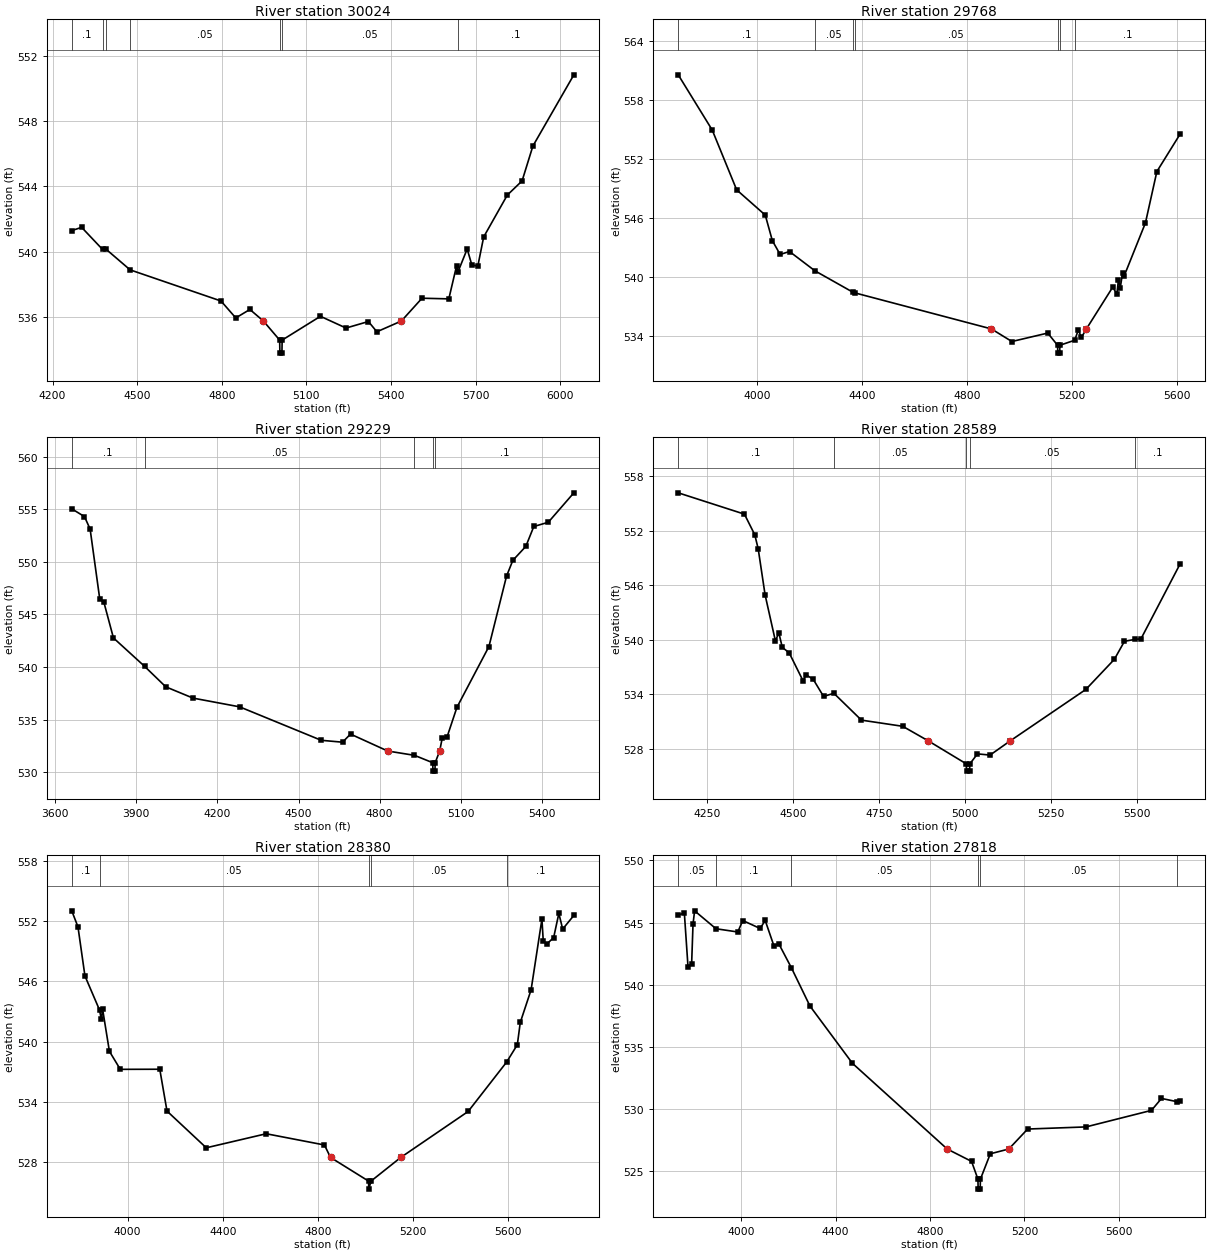
Type RM Length L Ch R = 1 ,30024   ,256,256,256
BEGIN DESCRIPTION:
Mapping XS 4d47a99d
END DESCRIPTION:
XS GIS Cut Line= 4
       1979406.7     13476844.87      1979697.49     13476367.45
      1979719.19     13475657.81      1979567.36     13475169.76
#Sta/Elev= 30
    4268  541.29    4303  541.49  4377.3  540.13  4388.7  540.16  4474.9  538.88
    4797  536.97  4849.5  535.93  4899.5  536.45 4947.48535.7406  5005.1  534.57
  5005.9  533.77  5013.1  533.77  5013.9  534.57  5149.6  536.03  5240.4  535.31
  5319.7  535.71  5349.7  535.08 5436.68535.7405  5509.8  537.14  5604.8   537.1
  5632.1  539.11  5637.6  538.77  5669.9  540.16  5686.5  539.18  5707.6  539.11
  5728.4   540.9  5812.2  543.47  5864.6  544.34  5902.9  546.48  6048.1  550.85
#Mann= 7 ,-1 , 0
    4268      .1       0  4377.3     .05       0  4388.7      .1       0
  4474.9     .05       0  5005.1     .03       0  5013.9     .05       0
  5637.6      .1       0
Bank Sta=4947.48,5436.68
XS Rating Curve= 0 ,0
Exp/Cntr=0.3,0.1

Type RM Length L Ch R = 1 ,29768   ,539,539,539
BEGIN DESCRIPTION:
UNT 022 in RCW 55.0
END DESCRIPTION:
XS GIS Cut Line= 3
      1979195.86     13477246.69      1980056.25     13476029.17
      1980424.96     13475825.02
#Sta/Elev= 30
  3699.4  560.58    3829  554.96  3921.9  548.89  4030.9  546.32  4057.9  543.72
  4087.5  542.32  4123.2  542.62  4219.9  540.66  4366.1  538.46  4371.4  538.42
 4892.33534.7498  4970.2  533.47  5106.8  534.33  5144.2  533.09    5145  532.29
  5152.2  532.29    5153  533.09  5209.6   533.6  5223.1  534.65    5235  533.88
 5253.94534.7498  5354.1  538.99  5370.2  538.31  5375.9  539.72  5383.1  538.96
  5391.9  540.45  5397.6  540.12  5478.9  545.53  5522.4  550.75  5611.7  554.59
#Mann= 7 ,-1 , 0
  3699.4      .1       0  4219.9     .05       0  4366.1      .1       0
  4371.4     .05       0  5144.2     .03       0    5153     .05       0
  5209.6      .1       0
Bank Sta=4892.33,5253.94
XS Rating Curve= 0 ,0
Exp/Cntr=0.3,0.1

Type RM Length L Ch R = 1 ,29229   ,640,640,640
BEGIN DESCRIPTION:
UNT 022 in RCW 54.0
END DESCRIPTION:
XS GIS Cut Line= 3
      1979400.71     13477136.45      1980376.44     13476448.92
      1980626.43     13475834.35
#Sta/Elev= 30
  3661.3  555.04  3708.3   554.3  3729.2  553.11  3764.9  546.45  3779.7   546.2
  3815.4  542.77  3930.6  540.07  4009.1  538.12  4109.8  537.05  4282.2  536.22
    4584  533.04  4662.8  532.86  4692.4  533.63 4829.96532.0204    4929  531.61
  4996.4  530.91  4997.3  530.11  5004.7  530.11  5005.5  530.91 5022.09532.0201
  5031.9  533.29  5049.1  533.33  5085.9  536.17  5204.3  541.95  5269.4  548.64
  5292.7  550.14  5340.8  551.47  5370.3  553.36  5423.8  553.76  5518.4  556.56
#Mann= 5 ,-1 , 0
  3661.3      .1       0  3930.6     .05       0    4929      .1       0
  4996.4     .07       0  5005.5      .1       0
Bank Sta=4829.96,5022.09
XS Rating Curve= 0 ,0
Exp/Cntr=0.3,0.1

Type RM Length L Ch R = 1 ,28589   ,209,209,209
BEGIN DESCRIPTION:
UNT 022 in RCW 53.0
END DESCRIPTION:
XS GIS Cut Line= 3
      1980996.23     13477327.44      1980996.23     13476473.23
      1980767.06     13475913.32
#Sta/Elev= 30
  4167.1  556.18  4359.5  553.83  4389.5  551.56  4399.5  550.01  4419.5  544.94
  4449.5  539.86  4459.5  540.75  4469.5  539.15  4489.5  538.55  4529.5  535.49
  4539.5  536.11  4559.5  535.62  4589.5  533.74  4619.4  534.09  4699.5  531.13
  4819.5  530.45 4894.03528.8403  5004.4  526.31  5005.3  525.51  5013.7  525.51
  5014.7  526.31  5036.7  527.41  5073.4  527.28 5131.78528.8405  5351.7  534.51
  5434.6  537.83    5464  539.82  5493.5  540.02    5512  540.09  5626.3  548.39
#Mann= 5 ,-1 , 0
  4167.1      .1       0  4619.4     .05       0  5004.4    .035       0
  5014.7     .05       0  5493.5      .1       0
Bank Sta=4894.03,5131.78
XS Rating Curve= 0 ,0
Exp/Cntr=0.3,0.1

Type RM Length L Ch R = 1 ,28380   ,562,562,562
BEGIN DESCRIPTION:
UNT 022 in RCW 52.0
END DESCRIPTION:
XS GIS Cut Line= 3
      1982058.71       13477274.      1981490.15     13477011.42
      1980778.35     13475707.17
#Sta/Elev= 30
  3764.8  553.03  3790.9  551.43  3820.2  546.54  3881.5  543.15  3889.1  542.23
  3894.6  543.21  3923.1  539.03  3968.9  537.23    4135  537.24  4165.4  533.07
  4330.6  529.41  4582.8  530.81  4827.7  529.69 4853.22528.4499  5013.3  526.09
  5014.2  525.29  5023.6  526.09 5148.85528.4497  5432.2  533.03  5594.3  537.96
  5639.1  539.68  5651.5   541.9  5697.1  545.16  5742.6   552.2  5748.3  549.99
  5764.4  549.75  5791.9  550.36  5813.8  552.77  5829.9  551.21  5876.9  552.57
#Mann= 5 ,-1 , 0
  3764.8      .1       0  3881.5     .05       0  5013.3    .035       0
  5023.6     .05       0  5594.3      .1       0
Bank Sta=4853.22,5148.85
XS Rating Curve= 0 ,0
Exp/Cntr=0.3,0.1

Type RM Length L Ch R = 1 ,27818   ,454,454,454
BEGIN DESCRIPTION:
UNT 022 in RCW 51.0
END DESCRIPTION:
XS GIS Cut Line= 3
      1982342.27     13477364.09        1981675.       13476275.
      1981226.78     13475554.14
#Sta/Elev= 30
  3733.9   545.6  3759.8  545.76  3775.2  541.46  3790.6  541.66  3796.5  544.87
  3803.2  545.94  3893.7   544.5    3986  544.24  4007.3  545.16  4080.8  544.52
  4102.1  545.17  4138.8  543.14  4160.1  543.28  4213.4  541.35  4291.6  538.29
  4471.7  533.68 4872.77526.7949    4976   525.8    5003  524.37  5003.9  523.57
  5012.6  523.57  5013.5  524.37  5055.4  526.41 5133.76526.7949  5213.6   528.4
  5460.4  528.57  5737.8   529.9  5780.3  530.86  5845.7   530.6    5860  530.67
#Mann= 6 ,-1 , 0
  3733.9     .05       0  3893.7      .1       0  4213.4     .05       0
    5003    .035       0  5013.5     .05       0  5845.7      .1       0
Bank Sta=4872.77,5133.76
XS Rating Curve= 0 ,0
Exp/Cntr=0.3,0.1

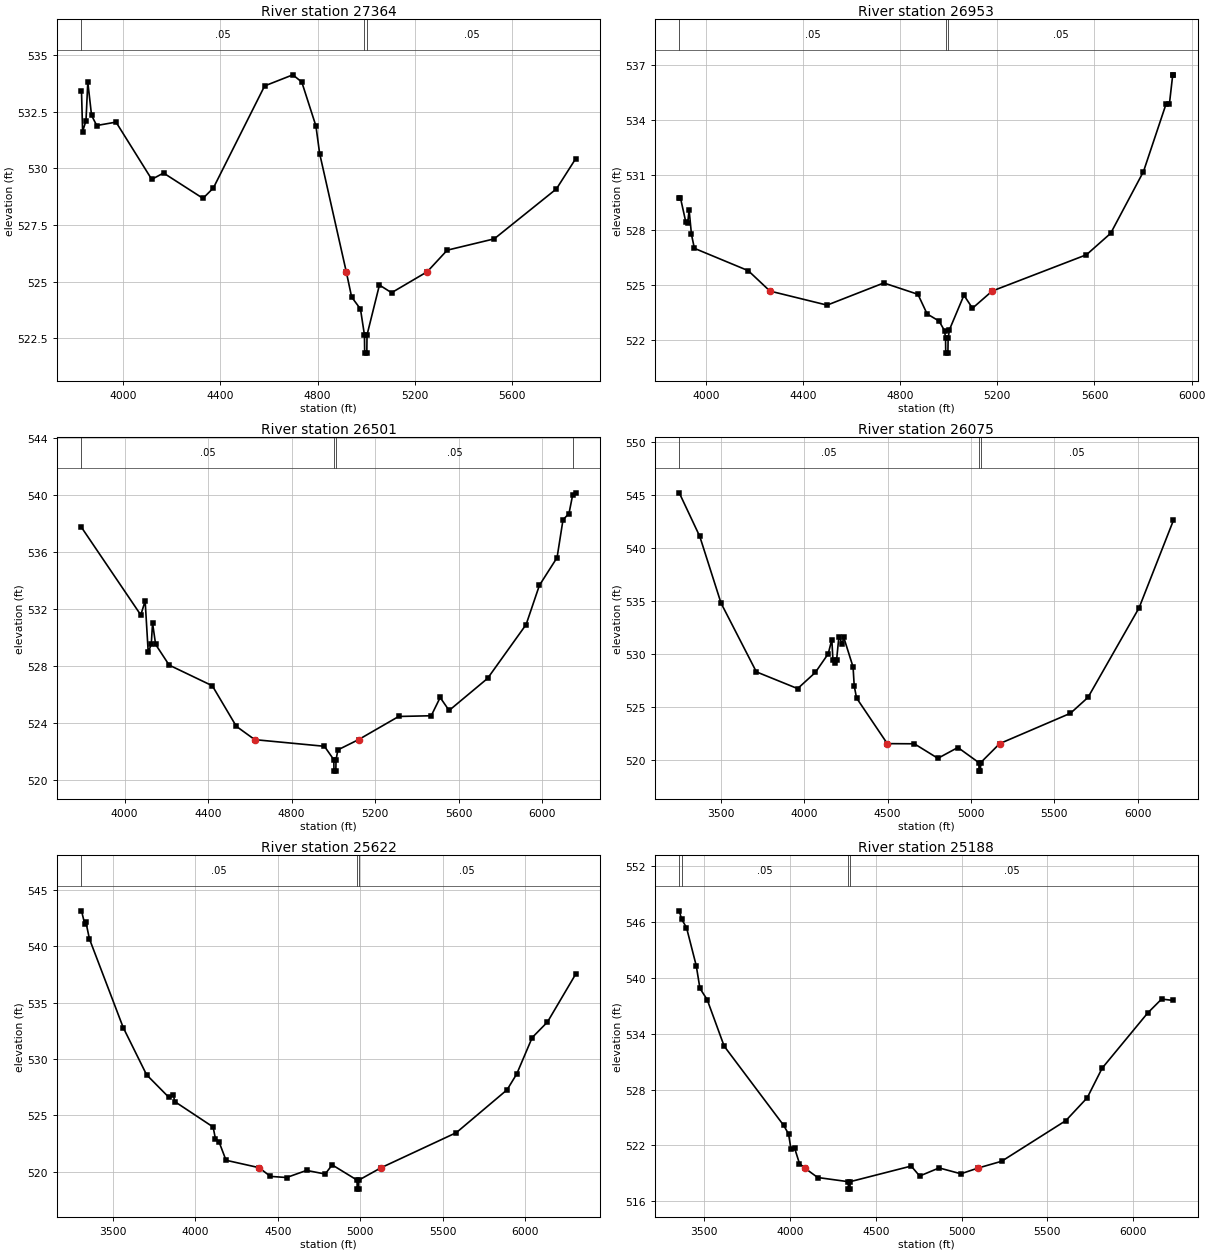
Type RM Length L Ch R = 1 ,27364   ,411,411,411
BEGIN DESCRIPTION:
UNT 022 in RCW 50.0
END DESCRIPTION:
XS GIS Cut Line= 3
      1982644.35     13477030.74        1982025.       13476025.
      1981509.46     13475350.88
#Sta/Elev= 30
    3830  533.42  3834.6  531.63  3848.5  532.12  3855.9  533.82  3871.3  532.35
  3892.5   531.9  3971.8  532.05  4118.5  529.52    4167   529.8  4329.1  528.68
  4371.7  529.14  4582.3  533.65  4698.2  534.14  4734.9  533.82  4792.9  531.88
  4808.3  530.66 4917.59525.4364  4939.6  524.32  4975.9  523.79  4992.3  522.64
  4993.2  521.84    5002  521.84  5002.8  522.64  5053.8  524.85  5103.6  524.51
  5250.1525.4362  5332.2  526.39  5525.3  526.89    5781   529.1  5859.8  530.43
#Mann= 3 ,-1 , 0
    3830     .05       0  4992.3    .035       0  5002.8     .05       0
Bank Sta=4917.59,5250.1
XS Rating Curve= 0 ,0
Exp/Cntr=0.3,0.1

Type RM Length L Ch R = 1 ,26953   ,452,452,452
BEGIN DESCRIPTION:
UNT 022 in RCW 49.0
END DESCRIPTION:
XS GIS Cut Line= 3
      1982917.78     13476798.97        1982375.       13475825.
      1981791.02     13475115.78
#Sta/Elev= 30
  3891.1  529.73  3896.2  529.73  3918.5  528.39  3925.9  528.36  3931.7  529.08
  3941.4  527.74  3953.4  526.98  4175.1  525.76 4264.32524.6475  4499.7  523.88
  4732.9  525.09  4873.5  524.47  4911.2   523.4  4960.4  523.01  4983.2  522.48
  4987.1  522.06  4987.9  521.26  4996.8  521.26  4997.7  522.06  5003.2  522.54
  5062.8  524.42  5097.9  523.71 5178.81524.6475  5567.1  526.63  5666.7   527.8
  5801.7  531.17  5894.2  534.84  5908.5  534.87  5922.1  536.45  5924.8  536.45
#Mann= 3 ,-1 , 0
  3891.1     .05       0  4987.1    .035       0  4997.7     .05       0
Bank Sta=4264.32,5178.81
XS Rating Curve= 0 ,0
Exp/Cntr=0.3,0.1

Type RM Length L Ch R = 1 ,26501   ,426,426,426
BEGIN DESCRIPTION:
UNT 022 in RCW 48.0
END DESCRIPTION:
XS GIS Cut Line= 3
      1983498.53     13476658.38        1982775.       13475675.
      1981904.78     13474930.06
#Sta/Elev= 30
  3793.5  537.71  4077.5  531.57  4098.3  532.56    4113  528.96  4127.6  529.51
  4133.8  531.01  4148.4  529.51  4213.2  528.06    4420  526.61  4534.9  523.77
 4623.24522.8354  4956.9  522.37  5001.8  521.43  5002.6  520.63  5011.5  520.63
  5012.4  521.43  5021.5  522.12 5120.06522.8353  5312.4  524.46  5468.3  524.51
  5511.1  525.79  5553.9  524.88  5738.3  527.13  5922.7   530.9  5986.4  533.65
  6070.9  535.59  6099.4  538.24    6128  538.68  6145.5  539.97  6159.9  540.13
#Mann= 4 ,-1 , 0
  3793.5     .05       0  5001.8    .035       0  5012.4     .05       0
  6145.5      .1       0
Bank Sta=4623.24,5120.06
XS Rating Curve= 0 ,0
Exp/Cntr=0.3,0.1

Type RM Length L Ch R = 1 ,26075   ,453,453,453
BEGIN DESCRIPTION:
UNT 022 in RCW 47.0
END DESCRIPTION:
XS GIS Cut Line= 3
      1984401.28     13476653.13        1983075.       13475425.
      1982175.61     13474693.95
#Sta/Elev= 30
  3248.7   545.2  3372.1  541.08  3499.6  534.79  3711.7   528.3  3959.5  526.72
  4065.5  528.24  4143.2  530.01  4164.7  531.35  4171.5  529.41  4185.7   529.1
  4193.1  529.38  4207.2  531.62  4228.2  530.93  4235.6  531.59  4292.3  528.76
  4299.1  526.98  4313.3  525.83 4497.74521.5255  4660.2  521.51  4801.4  520.14
  4921.6  521.16  5047.6  519.73  5048.4  518.93  5057.3  518.93  5058.2  519.73
 5172.42521.5253  5597.2  524.39  5702.7  525.89  6009.5  534.35  6215.3  542.59
#Mann= 3 ,-1 , 0
  3248.7     .05       0  5047.6    .035       0  5058.2     .05       0
Bank Sta=4497.74,5172.42
XS Rating Curve= 0 ,0
Exp/Cntr=0.3,0.1

Type RM Length L Ch R = 1 ,25622   ,434,434,434
BEGIN DESCRIPTION:
UNT 022 in RCW 46.0
END DESCRIPTION:
XS GIS Cut Line= 3
      1984526.27     13476381.41        1983375.       13475125.
      1982311.04     13474391.87
#Sta/Elev= 30
  3310.3  543.15  3330.1  541.97  3336.9  542.15  3358.4  540.66  3563.2   532.8
    3705  528.61  3839.4  526.62  3867.8  526.82  3875.1  526.24  4108.3  523.98
  4122.5  522.93    4144  522.67  4186.6  521.03  4387.3520.3723  4455.4   519.6
  4554.1   519.5    4675  520.13  4787.8  519.81  4830.3  520.62  4981.1  519.27
  4981.9  518.47  4990.8  518.47  4991.7  519.27 5127.49520.3724  5583.2  523.48
  5890.8  527.28  5949.5  528.69    6043  531.91  6135.6  533.29  6306.5  537.53
#Mann= 3 ,-1 , 0
  3310.3     .05       0  4981.1    .035       0  4991.7     .05       0
Bank Sta=4387.3,5127.49
XS Rating Curve= 0 ,0
Exp/Cntr=0.3,0.1

Type RM Length L Ch R = 1 ,25188   ,453,453,453
BEGIN DESCRIPTION:
UNT 022 in RCW 45.0
END DESCRIPTION:
XS GIS Cut Line= 3
      1984825.02     13475875.01        1983625.       13474775.
      1982530.66     13474166.17
#Sta/Elev= 30
  3354.5  547.23  3368.2  546.33  3396.8  545.43  3453.5  541.34  3475.1  538.89
  3517.3  537.68  3616.3  532.68  3963.4  524.15  3991.8  523.23  4005.7   521.6
  4026.9  521.71  4055.3  520.05 4087.23519.5506  4161.4  518.55  4339.8   518.1
  4340.6   517.3  4349.6   517.3  4350.4   518.1  4706.5  519.78  4755.8  518.71
  4869.3  519.58  4996.1  518.95 5093.32519.5505    5234   520.3  5607.9  524.67
  5732.6  527.13  5819.5  530.31  6084.8  536.24    6166  537.74  6234.7  537.59
#Mann= 4 ,-1 , 0
  3354.5      .1       0  3368.2     .05       0  4339.8    .035       0
  4350.4     .05       0
Bank Sta=4087.23,5093.32
XS Rating Curve= 0 ,0
Exp/Cntr=0.3,0.1

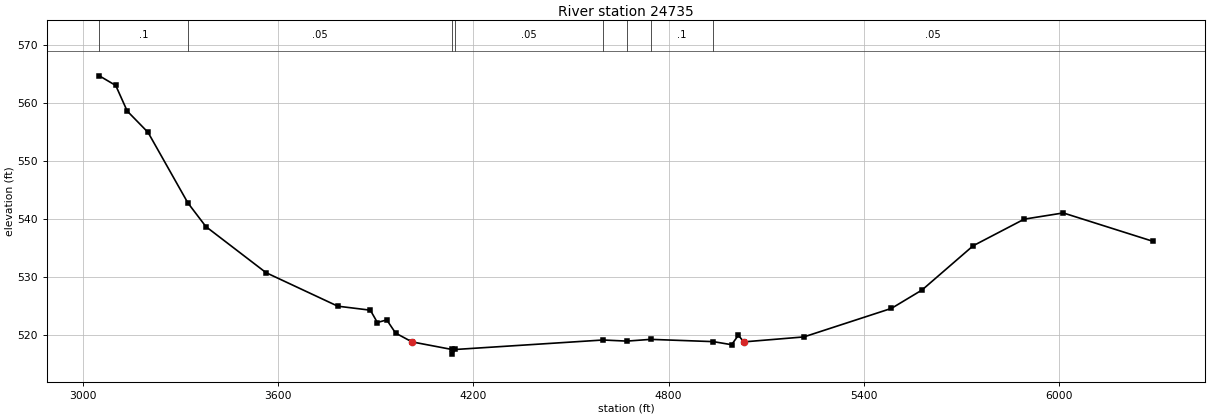
Type RM Length L Ch R = 1 ,24735   ,241,241,241
BEGIN DESCRIPTION:
UNT 022 in RCW 44.0
END DESCRIPTION:
XS GIS Cut Line= 3
      1985074.97     13475924.97        1983875.       13474425.
      1982630.47     13474001.23
#Sta/Elev= 30
  3051.3  564.62  3101.7  562.96  3136.9  558.56  3200.9  554.89  3323.3  542.75
  3378.6  538.68  3563.5  530.75  3783.6  524.99  3883.7   524.3  3905.3  522.18
  3934.1  522.63  3961.3  520.36 4011.57518.8467  4134.4  517.54  4135.3  516.74
  4145.1  517.54  4598.6  519.17  4671.5  518.98  4744.9  519.28  4937.2  518.89
  4993.3  518.36    5014  519.97 5031.19518.8469  5215.2   519.7  5484.3  524.61
  5578.4  527.78  5735.2  535.38    5892  539.96  6012.1  541.03  6286.9  536.16
#Mann= 8 ,-1 , 0
  3051.3      .1       0  3323.3     .05       0  4134.4    .035       0
  4145.1     .05       0  4598.6      .1       0  4671.5     .05       0
  4744.9      .1       0  4937.2     .05       0
Bank Sta=4011.57,5031.19
XS Rating Curve= 0 ,0
Exp/Cntr=0.3,0.1