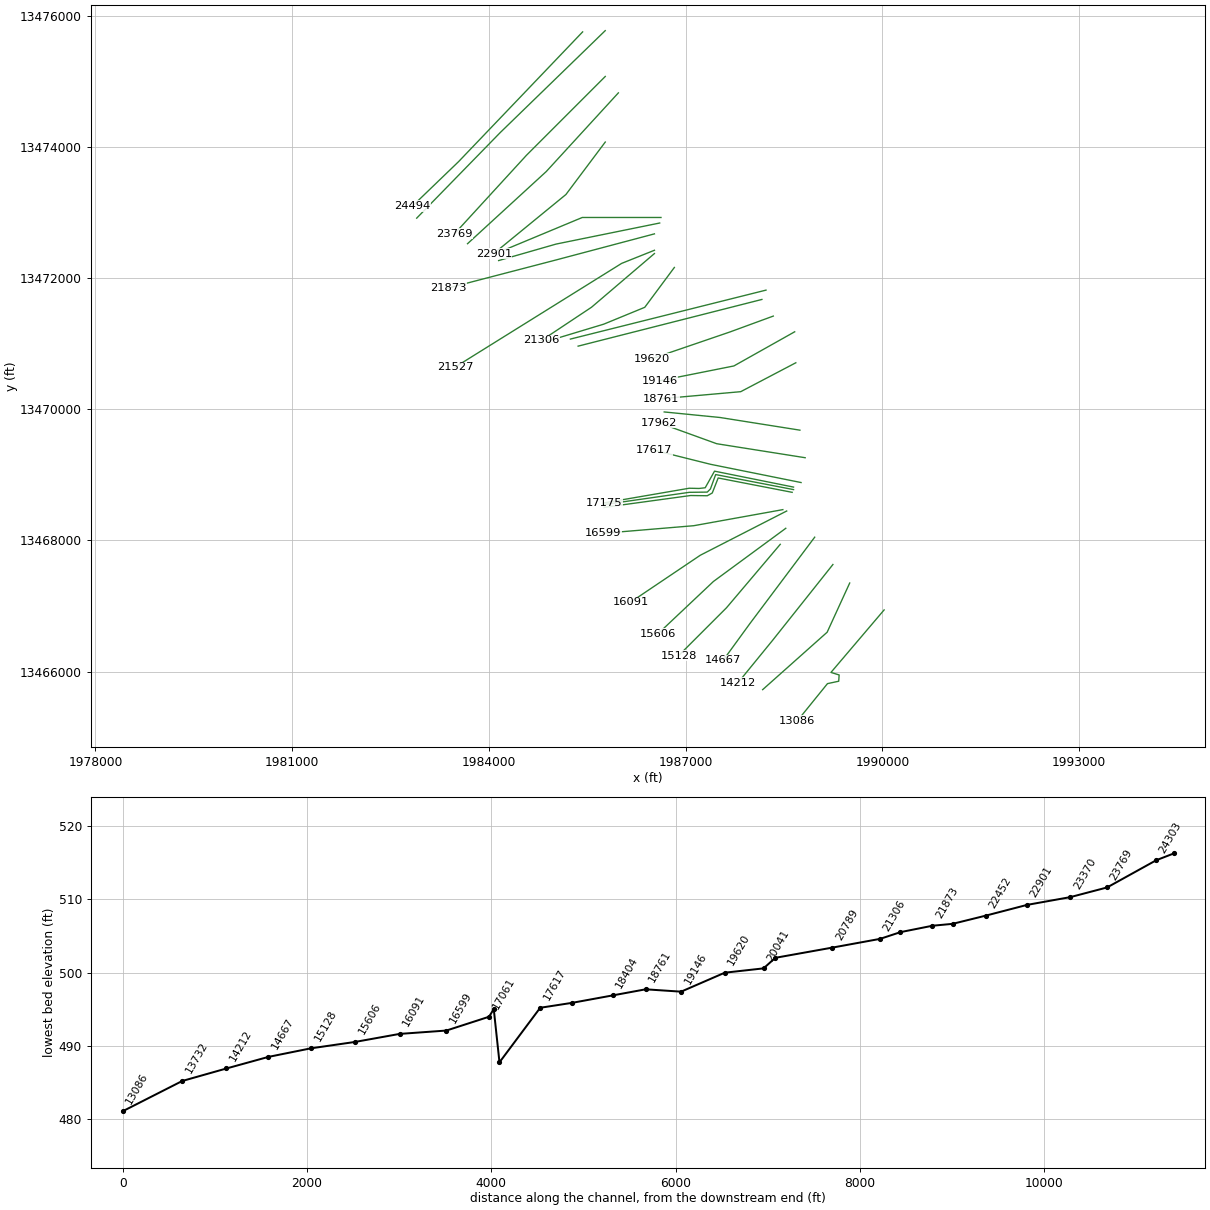
HEC-RAS study UNT 022 in RCW.prj: UNT 022 in RCW Base Level Engineering

--- UNT 022 in RCW.g01 (geometry) --- (continued)

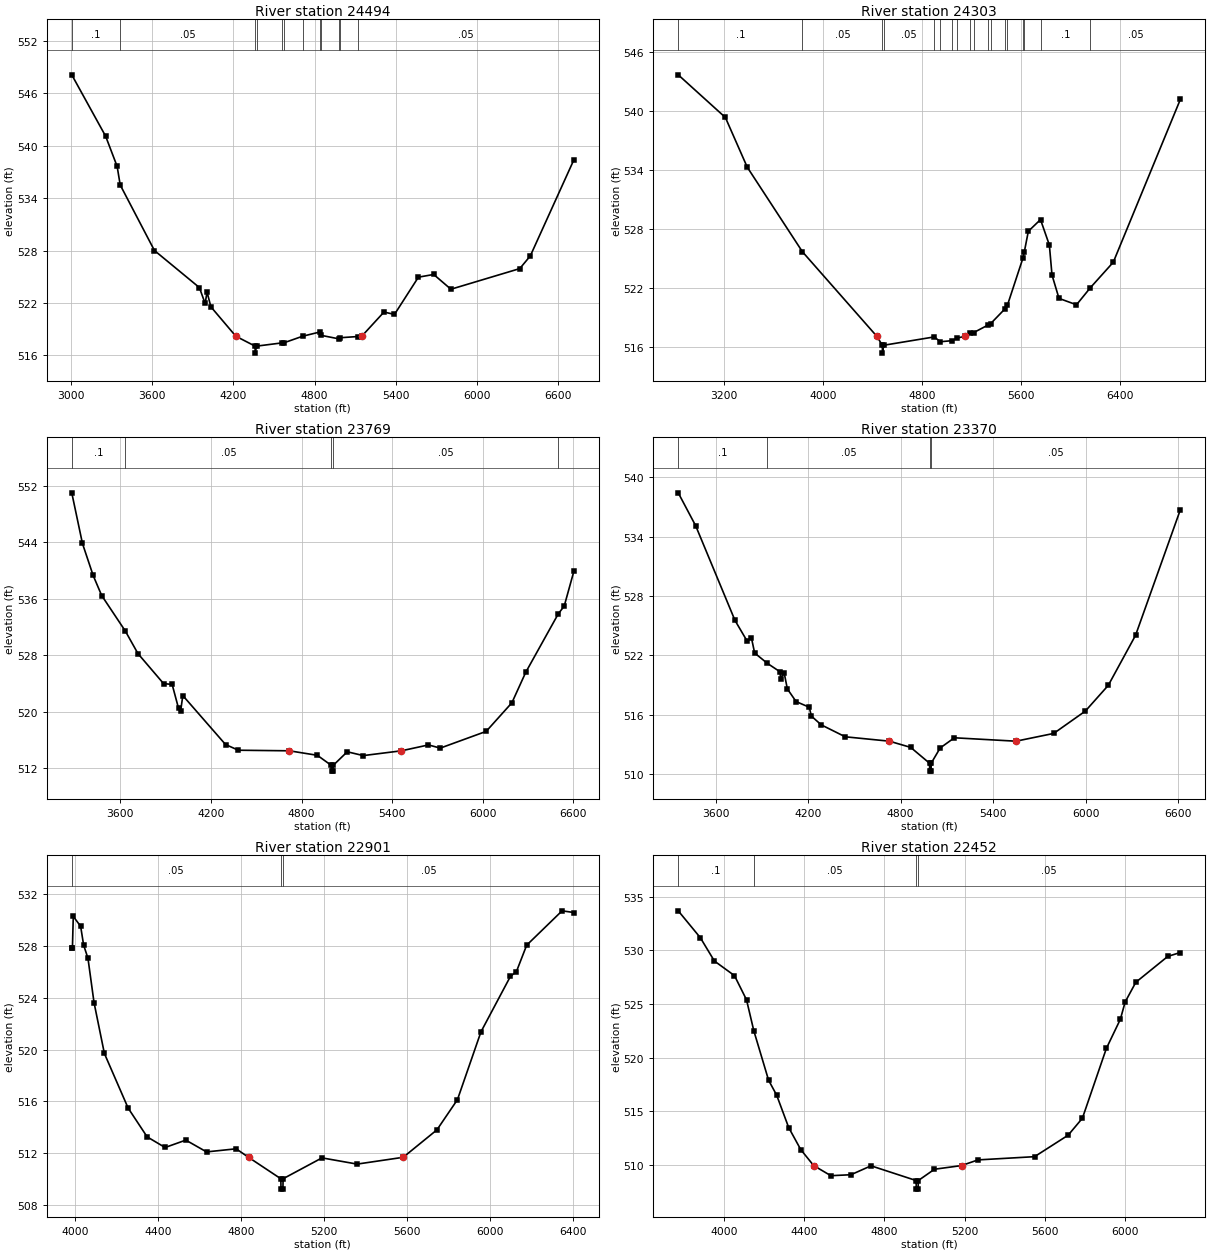
Type RM Length L Ch R = 1 ,24494   ,191,191,191
BEGIN DESCRIPTION:
Mapping XS 4091af96
END DESCRIPTION:
XS GIS Cut Line= 3
      1985429.92     13475754.69      1983537.57     13473775.53
      1982835.23      13473099.2
#Sta/Elev= 30
  3004.5  548.11  3255.2  541.08  3340.1  537.63  3362.7  535.51  3615.9  528.01
  3948.4  523.77  3990.8  521.95    4005  523.25  4033.3  521.57 4217.79518.2051
  4360.4  517.07  4361.2  516.27  4371.1  517.07  4558.7  517.44  4575.3  517.46
  4713.1  518.21  4840.1  518.69  4850.8   518.3  4980.8   517.9  4988.5  518.03
  5121.5  518.17 5149.22518.2051  5313.6  520.97  5391.3   520.7  5568.1  524.96
  5681.3  525.27  5808.6  523.58  6317.7  525.94  6395.7  527.39  6717.8  538.38
#Mann= 12 ,-1 , 0
  3004.5      .1       0  3362.7     .05       0  4360.4     .07       0
  4371.1     .05       0  4558.7     .08       0  4575.3     .05       0
  4713.1     .08       0  4840.1     .05       0  4850.8      .1       0
  4980.8     .05       0  4988.5     .08       0  5121.5     .05       0
Bank Sta=4217.79,5149.22
XS Rating Curve= 0 ,0
Exp/Cntr=0.3,0.1

Type RM Length L Ch R = 1 ,24303   ,534,534,534
BEGIN DESCRIPTION:
UNT 022 in RCW 43.0
END DESCRIPTION:
XS GIS Cut Line= 3
      1985774.57     13475773.81      1984175.59     13474221.71
      1982899.77     13472914.65
#Sta/Elev= 30
  2829.6  543.66  3210.3  539.32    3387  534.26  3832.3  525.66 4433.76517.0477
    4478  516.14  4478.8  515.34  4488.7  516.14  4897.6  516.99  4945.8   516.5
    5044  516.61  5079.3  516.87 5145.82 517.048  5186.6  517.39  5215.7  517.43
  5328.8  518.18    5352  518.33    5471  519.88  5488.4  520.22  5613.2     525
  5624.7  525.65  5657.1  527.74  5755.4  528.93  5826.9  526.34  5848.2  523.29
  5904.7  520.91    6046  520.26    6159  522.01  6343.1  524.59  6884.5  541.15
#Mann= 18 ,-1 , 0
  2829.6      .1       0  3832.3     .05       0    4478    .035       0
  4488.7     .05       0  4897.6      .1       0  4945.8     .05       0
    5044      .1       0  5079.3     .05       0  5186.6      .1       0
  5215.7     .05       0  5328.8      .1       0    5352     .05       0
    5471      .1       0  5488.4     .05       0  5613.2      .1       0
  5624.7     .05       0  5755.4      .1       0    6159     .05       0
Bank Sta=4433.76,5145.82
XS Rating Curve= 0 ,0
Exp/Cntr=0.3,0.1

Type RM Length L Ch R = 1 ,23769   ,399,399,399
BEGIN DESCRIPTION:
UNT 022 in RCW 42.0
END DESCRIPTION:
XS GIS Cut Line= 3
      1985775.01     13475075.01        1984575.       13473875.
      1983475.03     13472675.04
#Sta/Elev= 30
  3278.4  551.03  3349.1  543.86  3419.8  539.34  3476.4  536.49    3633  531.46
  3716.8  528.26  3886.5  524.01  3943.1   523.9  3985.5  520.51  3999.7  520.19
  4013.8  522.32  4296.6  515.39  4381.5  514.58 4719.27514.4981  4904.8  513.86
  4998.1  512.42  4998.9  511.62  5008.2  511.62  5008.9  512.42  5102.8  514.36
  5208.9  513.82 5461.36514.4982  5640.5  515.33  5718.8  514.88  6022.8  517.25
    6193   521.3  6284.9  525.62  6500.1  533.89  6539.5  534.99  6603.3  539.91
#Mann= 5 ,-1 , 0
  3278.4      .1       0    3633     .05       0  4998.1    .035       0
  5008.9     .05       0  6500.1      .1       0
Bank Sta=4719.27,5461.36
XS Rating Curve= 0 ,0
Exp/Cntr=0.3,0.1

Type RM Length L Ch R = 1 ,23370   ,469,469,469
BEGIN DESCRIPTION:
UNT 022 in RCW 41.0
END DESCRIPTION:
XS GIS Cut Line= 3
        1985975.       13474825.        1984875.       13473625.
      1983674.97     13472524.98
#Sta/Elev= 30
  3357.5  538.43  3470.6   535.1  3725.3  525.54  3803.6  523.46    3832  523.78
    3853  522.24  3934.1  521.21  4015.7  520.36  4022.5  519.66  4044.1  520.25
  4065.1  518.61  4121.8  517.33  4206.9  516.76  4221.1  515.86  4284.6  514.98
  4440.6  513.77 4726.85513.3257  4864.8   512.7  4987.1   511.1  4987.8   510.3
  4997.1   510.3  4997.9   511.1    5056  512.64  5148.2  513.67 5547.72513.3256
  5792.2  514.11  5997.6  516.37  6146.2  518.97  6323.1  524.03  6613.3  536.71
#Mann= 4 ,-1 , 0
  3357.5      .1       0  3934.1     .05       0  4987.1    .035       0
  4997.9     .05       0
Bank Sta=4726.85,5547.72
XS Rating Curve= 0 ,0
Exp/Cntr=0.3,0.1

Type RM Length L Ch R = 1 ,22901   ,449,449,449
BEGIN DESCRIPTION:
UNT 022 in RCW 40.0
END DESCRIPTION:
XS GIS Cut Line= 3
      1985774.98     13474074.98        1985175.       13473275.
      1984075.03     13472375.03
#Sta/Elev= 30
  3982.5  527.81  3985.6  527.81  3989.8  530.27  4025.2  529.51  4039.8  528.05
  4060.6  527.04  4089.8  523.63  4139.8   519.7  4254.3  515.49    4346  513.27
  4432.5  512.45  4532.5  513.02  4632.5  512.11  4775.2  512.35 4834.92511.6935
  4990.7  510.04  4991.5  509.24  5000.8  509.24  5001.5  510.04  5189.2  511.65
  5358.6  511.17 5580.64511.6936  5743.4  513.81  5842.4  516.14  5955.8  521.37
    6098  525.65  6126.7  526.01  6176.2  528.05    6347   530.7  6403.7  530.57
#Mann= 3 ,-1 , 0
  3982.5     .05       0  4990.7    .035       0  5001.5     .05       0
Bank Sta=4834.92,5580.64
XS Rating Curve= 0 ,0
Exp/Cntr=0.3,0.1

Type RM Length L Ch R = 1 ,22452   ,360,360,360
BEGIN DESCRIPTION:
UNT 022 in RCW 39.0
END DESCRIPTION:
XS GIS Cut Line= 3
      1986624.99       13472925.        1985425.       13472925.
      1984224.99       13472425.
#Sta/Elev= 30
  3773.5  533.67  3883.5  531.17  3953.5     529  4053.5  527.64  4113.5  525.39
  4149.8  522.51  4223.5   517.9  4263.5  516.52  4323.5   513.5  4383.5  511.45
 4447.86509.9633  4533.5  509.02  4633.5  509.11  4733.5  509.94  4958.1  508.57
  4958.8  507.77  4968.1  507.77  4968.9  508.57  5049.3  509.62  5184.2509.9632
    5266  510.49  5547.7  510.79    5715  512.79    5786  514.37  5905.2  520.86
    5975  523.58  5998.9  525.19    6052  527.02  6211.2  529.43  6273.5  529.79
#Mann= 4 ,-1 , 0
  3773.5      .1       0  4149.8     .05       0  4958.1    .035       0
  4968.9     .05       0
Bank Sta=4447.86,5184.2
XS Rating Curve= 0 ,0
Exp/Cntr=0.3,0.1

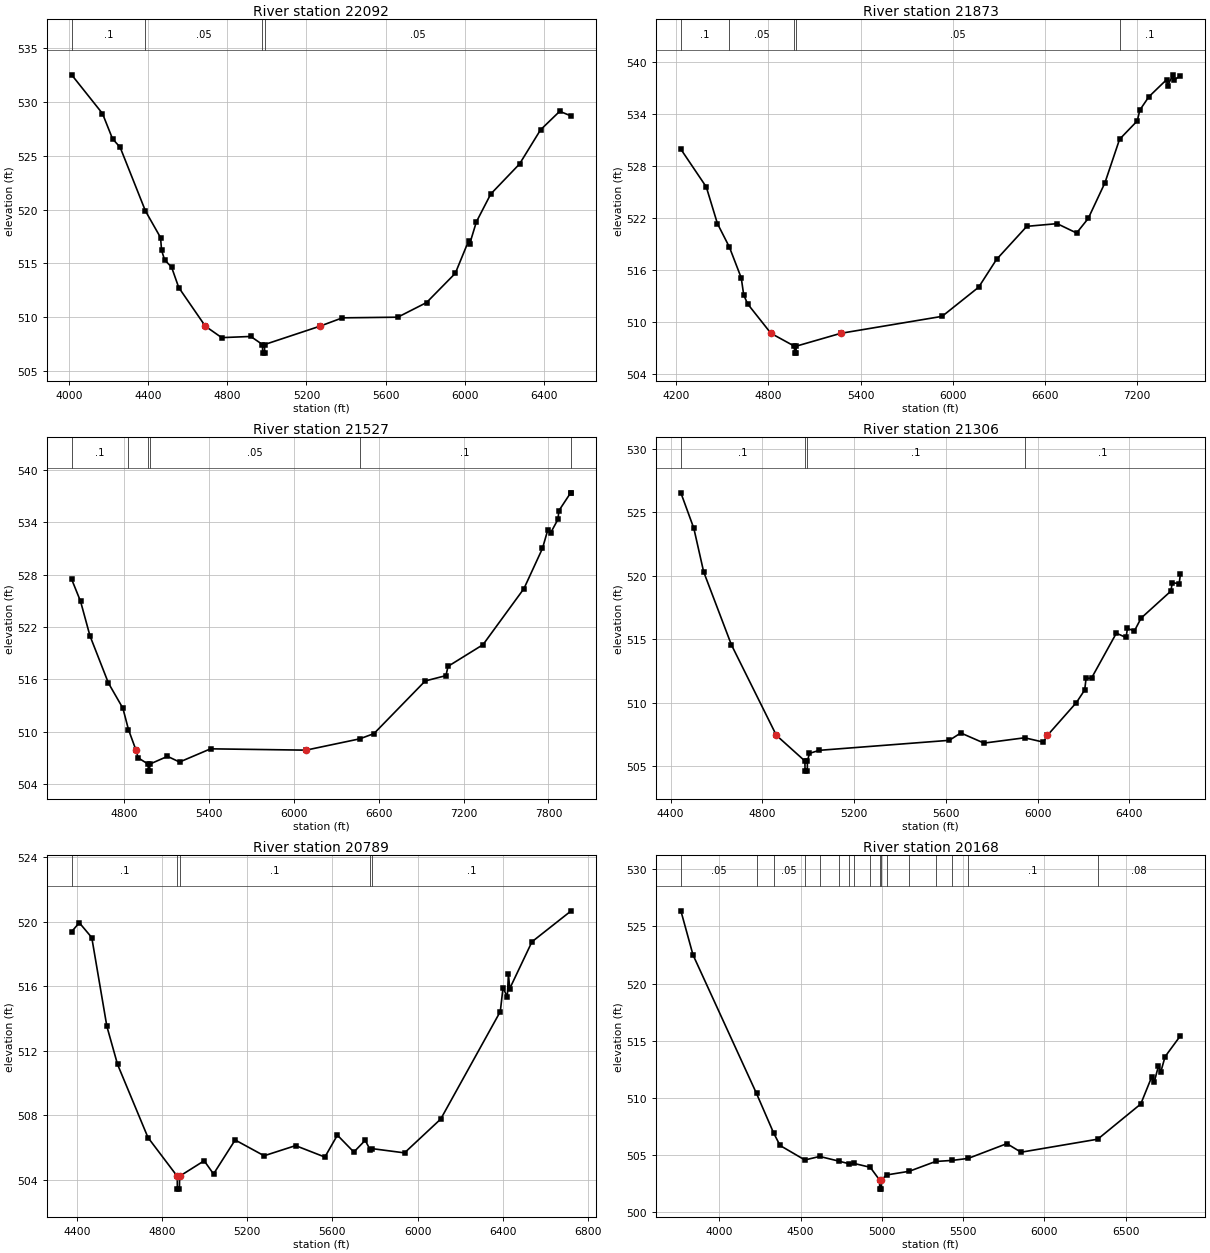
Type RM Length L Ch R = 1 ,22092   ,219,219,219
BEGIN DESCRIPTION:
Mapping XS 1fda4f3b
END DESCRIPTION:
XS GIS Cut Line= 3
      1986605.05     13472840.54      1985025.18     13472519.36
      1984149.26     13472267.85
#Sta/Elev= 30
  4014.2  532.52    4170  528.92  4220.6  526.58  4259.2  525.78  4387.1  519.86
  4463.3  517.39  4468.5  516.21  4483.7  515.32  4519.1  514.64  4555.1  512.75
 4689.53509.1561  4772.2  508.09  4918.9   508.2  4978.2  507.45    4979  506.65
  4988.4  506.65  4989.2  507.45 5268.73509.1561  5381.7  509.93  5661.6  509.99
  5806.9  511.35  5952.2  514.07  6019.7   517.1  6024.9   516.8  6058.6  518.85
  6131.3  521.44  6276.6  524.23  6382.9  527.41  6479.7  529.13  6537.7  528.69
#Mann= 4 ,-1 , 0
  4014.2      .1       0  4387.1     .05       0  4978.2    .035       0
  4989.2     .05       0
Bank Sta=4689.53,5268.73
XS Rating Curve= 0 ,0
Exp/Cntr=0.3,0.1

Type RM Length L Ch R = 1 ,21873   ,346,346,346
BEGIN DESCRIPTION:
UNT 022 in RCW 38.0
END DESCRIPTION:
XS GIS Cut Line= 3
      1986524.97     13472674.99      1985031.49       13472279.
      1983379.32      13471848.6
#Sta/Elev= 30
  4230.4   529.9  4395.9  525.55  4468.3  521.33  4546.4  518.61  4623.5  515.06
  4639.5   513.1  4664.9  512.07 4816.78508.6738  4969.7  507.19  4970.4  506.39
    4980  506.39  4980.8  507.19 5271.11508.6738  5931.1  510.63    6169  513.99
  6285.3  517.19  6482.6  521.01    6680  521.32  6806.6  520.24  6882.5  521.92
  6991.2  526.03  7086.5  531.05  7201.3  533.16  7218.6  534.42  7277.2  535.95
  7393.5  537.94  7398.7  537.21    7434  538.48  7439.2  537.85  7482.8  538.37
#Mann= 5 ,-1 , 0
  4230.4      .1       0  4546.4     .05       0  4969.7    .035       0
  4980.8     .05       0  7086.5      .1       0
Bank Sta=4816.78,5271.11
XS Rating Curve= 0 ,0
Exp/Cntr=0.3,0.1

Type RM Length L Ch R = 1 ,21527   ,221,221,221
BEGIN DESCRIPTION:
UNT 022 in RCW 37.0
END DESCRIPTION:
XS GIS Cut Line= 3
      1986524.97     13472424.99        1986025.       13472225.
      1983486.36     13470643.58
#Sta/Elev= 30
  4431.2  527.46  4494.4  524.92  4560.4     521    4691  515.59  4793.3  512.71
  4832.7  510.27 4885.79507.9185    4901  507.04  4971.8  506.32  4972.6  505.52
  4982.2  505.52  4982.9  506.32  5108.4  507.21  5193.5  506.56  5412.8  508.07
 6086.75507.9184  6466.2  509.21    6567  509.81  6929.2  515.83  7075.6  516.44
  7090.4   517.5  7337.6  519.98  7626.7  526.39  7757.7  530.99  7794.3  533.05
  7815.5  532.77  7867.4  534.32  7873.3  535.29  7956.6  537.34  7960.6  537.32
#Mann= 6 ,-1 , 0
  4431.2      .1       0  4832.7     .05       0  4971.8    .035       0
  4982.9     .05       0  6466.2      .1       0  7956.6     .08       0
Bank Sta=4885.79,6086.75
XS Rating Curve= 0 ,0
Exp/Cntr=0.3,0.1

Type RM Length L Ch R = 1 ,21306   ,517,517,517
BEGIN DESCRIPTION:
UNT 022 in RCW 36.0
END DESCRIPTION:
XS GIS Cut Line= 3
      1986524.98     13472374.98      1985566.22     13471556.78
      1984802.28     13471049.06
#Sta/Elev= 30
    4445  526.55  4501.5  523.75  4544.3  520.32  4665.1  514.57 4861.34507.4226
  4985.6   505.4  4986.4   504.6    4996   504.6  4996.7   505.4  5005.5     506
  5048.3  506.24    5615  507.03  5665.3  507.61  5766.4  506.81  5943.5  507.23
  6024.9  506.89 6042.92507.4225  6169.3  510.01  6205.3     511  6211.3  511.91
  6235.2  511.94  6343.3  515.48  6385.7  515.14  6391.7  515.86  6421.8  515.65
  6451.3  516.67  6581.1   518.8  6587.1  519.46  6617.2  519.39  6622.7  520.16
#Mann= 4 ,-1 , 0
    4445      .1       0  4985.6    .035       0  4996.7      .1       0
  5943.5      .1       0
Bank Sta=4861.34,6042.92
XS Rating Curve= 0 ,0
Exp/Cntr=0.3,0.1

Type RM Length L Ch R = 1 ,20789   ,621,621,621
BEGIN DESCRIPTION:
Mapping XS 0294fc9b
END DESCRIPTION:
XS GIS Cut Line= 4
      1986828.66     13472162.71      1986377.29     13471555.09
      1985752.29     13471298.15      1984878.63     13471034.66
#Sta/Elev= 30
  4376.2  519.39  4412.2  519.94  4470.7  519.02  4541.6  513.51  4591.7  511.15
  4734.6  506.61  4871.9  504.21  4872.6  503.41  4882.2  503.41    4883  504.21
  4998.4  505.17  5042.3  504.35  5143.8  506.46  5279.8  505.48  5427.5  506.11
    5565   505.4  5623.7  506.76    5701  505.71  5754.3  506.44  5777.9  505.84
  5788.4  505.92  5938.8  505.66  6108.9  507.76  6388.5  514.43  6401.4  515.91
  6421.5  515.33  6426.7  516.78  6432.7  515.85  6537.2  518.76  6721.4  520.68
#Mann= 5 ,-1 , 0
  4376.2      .1       0  4871.9     .07       0    4883      .1       0
  5777.9     .05       0  5788.4      .1       0
Bank Sta=4871.9,4883
XS Rating Curve= 0 ,0
Exp/Cntr=0.3,0.1

Type RM Length L Ch R = 1 ,20168   ,127,127,127
BEGIN DESCRIPTION:
Mapping XS 94d93f4c
END DESCRIPTION:
XS GIS Cut Line= 2
      1988225.93     13471817.19      1985243.34     13471070.68
#Sta/Elev= 30
  3763.2  526.36  3837.7  522.51  4228.7  510.38  4333.5  506.94  4373.5  505.83
  4526.4  504.56  4617.3  504.87  4738.3  504.45  4798.3  504.23    4828  504.26
  4928.6  503.92    4986  502.81  4986.7  502.01  4996.5  502.01  4997.2  502.81
    5029  503.25  5168.5  503.57  5330.8  504.43  5431.3  504.52  5531.9   504.7
  5769.5  505.99    5857  505.24  6328.7  506.38  6593.7  509.46  6660.8  511.82
  6676.1  511.36  6702.1  512.76  6717.3  512.29  6743.3   513.6  6837.8  515.43
#Mann= 17 ,-1 , 0
  3763.2     .05       0  4228.7      .1       0  4333.5     .05       0
  4526.4      .1       0  4617.3     .05       0  4738.3      .1       0
  4798.3     .08       0    4828     .05       0  4928.6     .08       0
    4986     .07       0  4997.2     .08       0    5029      .1       0
  5168.5     .08       0  5330.8     .05       0  5431.3     .08       0
  5531.9      .1       0  6328.7     .08       0
Bank Sta=4986,4997.2
XS Rating Curve= 0 ,0
Exp/Cntr=0.3,0.1

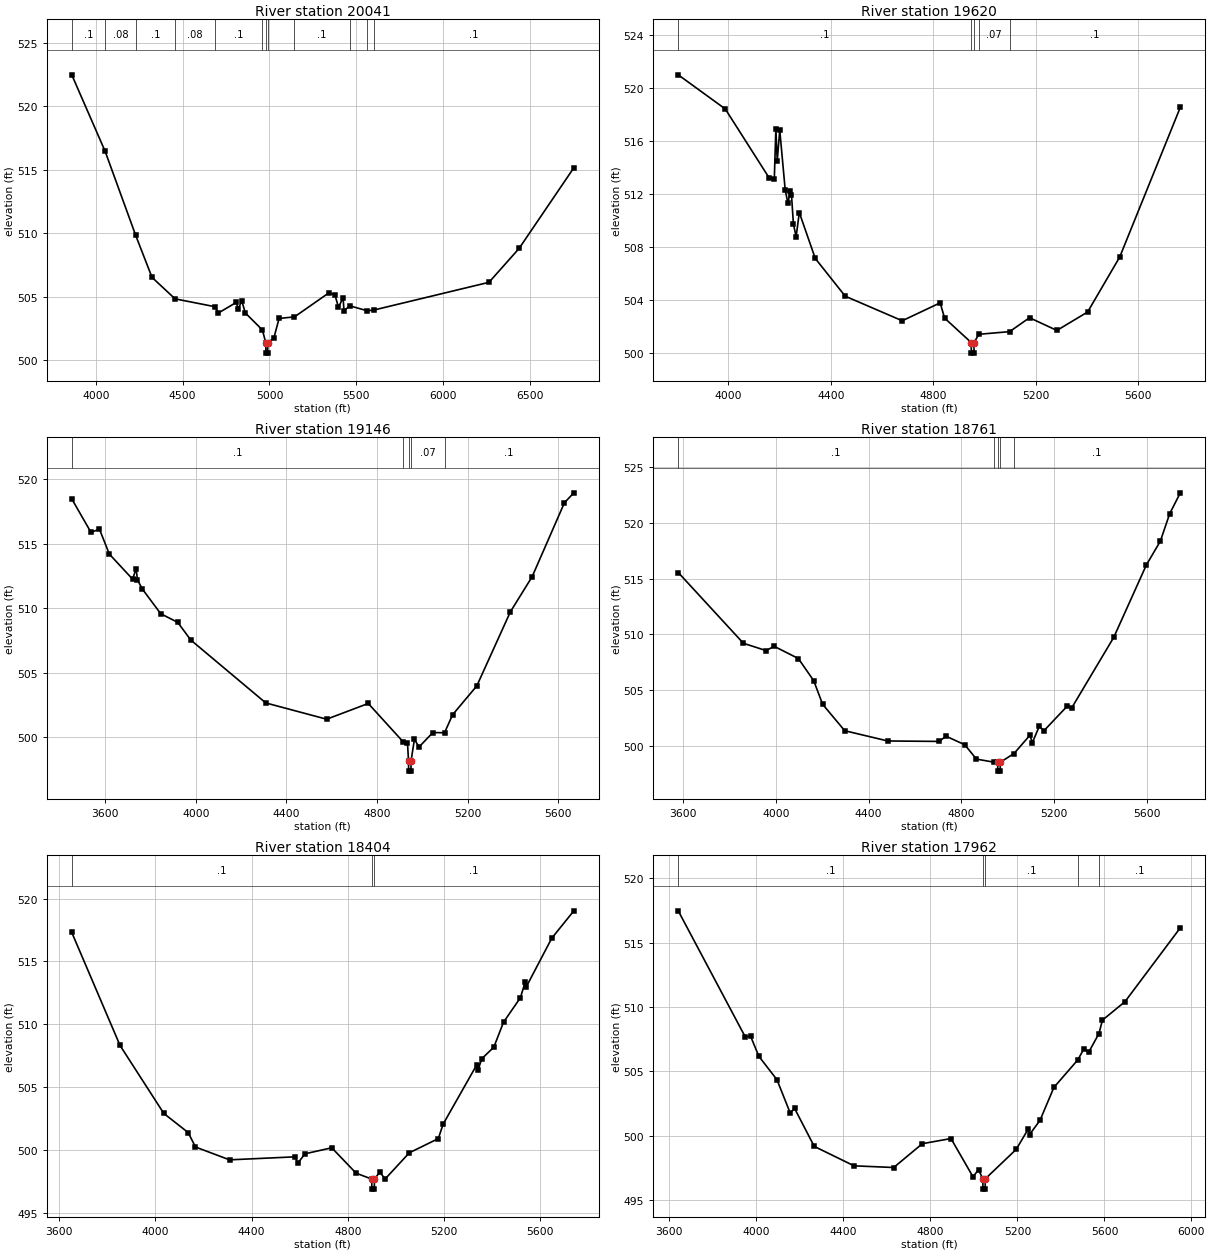
Type RM Length L Ch R = 1 ,20041   ,421,421,421
BEGIN DESCRIPTION:
Mapping XS 054b660a
END DESCRIPTION:
XS GIS Cut Line= 2
      1988163.48     13471674.84      1985361.38     13470963.03
#Sta/Elev= 30
  3861.7  522.46  4053.9  516.44  4229.3  509.85  4323.7  506.53  4456.4  504.84
  4686.7  504.22  4706.2  503.73  4809.4  504.56  4820.2  504.01  4840.3   504.7
  4861.1  503.73  4959.5  502.39  4979.1  501.37  4979.8  500.57  4989.8  500.57
  4990.5  501.37    5026  501.79  5055.5   503.3  5144.1  503.42  5342.1  505.31
  5376.8  505.16  5397.5  504.18    5424  504.93  5429.2  503.91  5462.6  504.29
  5563.3   503.9  5601.5  503.96  6264.1  506.14  6437.3   508.8  6752.8  515.15
#Mann= 12 ,-1 , 0
  3861.7      .1       0  4053.9     .08       0  4229.3      .1       0
  4456.4     .08       0  4686.7      .1       0  4959.5     .08       0
  4979.1     .07       0  4990.5     .08       0  5144.1      .1       0
  5462.6     .08       0  5563.3     .05       0  5601.5      .1       0
Bank Sta=4979.1,4990.5
XS Rating Curve= 0 ,0
Exp/Cntr=0.3,0.1

Type RM Length L Ch R = 1 ,19620   ,474,474,474
BEGIN DESCRIPTION:
UNT 022 in RCW 33.0
END DESCRIPTION:
XS GIS Cut Line= 3
      1988337.02     13471421.35      1987673.86     13471178.31
      1986488.21     13470772.69
#Sta/Elev= 30
  3804.3  520.96  3987.7  518.39  4160.1  513.16  4179.2  513.08  4185.3  516.89
  4190.6  514.48  4200.5  516.78  4221.8  512.27  4232.5  511.27    4241  512.19
  4246.3   511.9  4253.8  509.71  4264.4  508.76  4276.8  510.58    4339  507.12
  4456.1  504.27  4678.5  502.42  4826.5  503.77  4843.8  502.62  4947.6  500.78
  4948.3  499.98  4958.3  499.98    4959  500.78  4977.3   501.4  5097.6   501.6
  5175.2  502.65    5282  501.69  5401.9  503.08  5527.1  507.22  5763.7  518.51
#Mann= 5 ,-1 , 0
  3804.3      .1       0  4947.6     .07       0    4959      .1       0
  4977.3     .07       0  5097.6      .1       0
Bank Sta=4947.6,4959
XS Rating Curve= 0 ,0
Exp/Cntr=0.3,0.1

Type RM Length L Ch R = 1 ,19146   ,385,385,385
BEGIN DESCRIPTION:
UNT 022 in RCW 32.0
END DESCRIPTION:
XS GIS Cut Line= 3
      1988663.45     13471181.79      1987736.36     13470660.94
      1986604.42     13470435.25
#Sta/Elev= 30
  3451.7  518.47  3536.5  515.88  3574.1  516.12  3617.5   514.2  3720.1  512.26
  3736.1  513.06  3741.8   512.2  3763.5  511.49  3844.5  509.58  3919.7  508.91
  3977.5  507.54  4308.6  502.67  4577.6  501.41  4761.2  502.63  4914.3  499.68
  4934.5   499.6    4939  498.19  4939.7  497.39  4949.8  497.39  4950.4  498.19
  4965.1  499.85  4985.5  499.26  5046.7  500.38  5098.2  500.36  5133.5  501.75
  5240.7  503.99  5388.8  509.72  5485.2  512.45  5627.9  518.18  5669.3  518.94
#Mann= 5 ,-1 , 0
  3451.7      .1       0  4914.3     .07       0    4939     .07       0
  4950.4     .07       0  5098.2      .1       0
Bank Sta=4939,4950.4
XS Rating Curve= 0 ,0
Exp/Cntr=0.3,0.1

Type RM Length L Ch R = 1 ,18761   ,357,357,357
BEGIN DESCRIPTION:
UNT 022 in RCW 31.0
END DESCRIPTION:
XS GIS Cut Line= 3
      1988680.77     13470709.54      1987840.52     13470268.58
      1986629.32       13470161.
#Sta/Elev= 30
  3579.5  515.56  3860.5   509.2  3958.7  508.54  3992.8  508.93  4097.4  507.83
  4163.6  505.84    4202  503.72  4297.5  501.34  4483.1  500.42  4704.6  500.38
  4734.1  500.85  4815.1  500.08  4865.3  498.79  4939.4  498.52  4956.9  498.51
  4957.5  497.71  4967.6  497.71  4968.3  498.51  5027.3  499.29  5096.2  500.94
  5106.2  500.26  5136.3  501.74  5156.4  501.34  5256.8  503.55  5276.9  503.42
  5457.6  509.74  5598.1  516.24  5658.4  518.38  5698.5  520.84  5744.4  522.72
#Mann= 5 ,-1 , 0
  3579.5      .1       0  4939.4     .07       0  4956.9     .07       0
  4968.3     .07       0  5027.3      .1       0
Bank Sta=4956.9,4968.3
XS Rating Curve= 0 ,0
Exp/Cntr=0.3,0.1

Type RM Length L Ch R = 1 ,18404   ,442,442,442
BEGIN DESCRIPTION:
UNT 022 in RCW 30.0
END DESCRIPTION:
XS GIS Cut Line= 3
      1988743.31     13469681.78        1987525.       13469875.
      1986673.83     13469959.56
#Sta/Elev= 30
  3651.7   517.3  3852.5  508.31  4034.7   502.9    4136  501.38  4166.4  500.23
  4308.1  499.21  4581.5  499.45  4591.6  498.93    4622  499.69  4733.4  500.17
  4834.6  498.15  4899.6  497.68  4900.3  496.88  4910.4  496.88    4911  497.68
  4933.1  498.23  4955.6  497.69  5056.1  499.77  5176.7   500.9  5196.8  502.05
  5336.4  506.76  5341.5  506.33  5357.5  507.25  5407.8  508.18    5448  510.16
  5518.3  512.11  5538.1  513.35  5543.1  512.99    5649  516.85  5740.6  519.02
#Mann= 3 ,-1 , 0
  3651.7      .1       0  4899.6     .07       0    4911      .1       0
Bank Sta=4899.6,4911
XS Rating Curve= 0 ,0
Exp/Cntr=0.3,0.1

Type RM Length L Ch R = 1 ,17962   ,345,345,345
BEGIN DESCRIPTION:
UNT 022 in RCW 29.0
END DESCRIPTION:
XS GIS Cut Line= 3
      1988823.19     13469261.63        1987475.       13469475.
      1986588.54     13469795.82
#Sta/Elev= 30
  3640.9  517.48  3949.1  507.68  3973.2  507.75  4011.4  506.18  4094.7  504.36
  4155.4  501.78  4175.7  502.13    4266  499.18    4449  497.67  4631.3  497.54
  4762.9  499.39  4894.5  499.79  4995.7  496.82  5021.2  497.37  5040.8  496.66
  5041.5  495.86  5051.6  495.86  5052.2  496.66  5194.4  498.95  5250.4  500.55
  5255.7   500.1  5303.6   501.2  5367.5  503.76  5477.8  505.91  5505.7  506.77
    5527  506.48  5574.4  507.94  5590.8  508.99  5694.1  510.42  5948.6  516.16
#Mann= 5 ,-1 , 0
  3640.9      .1       0  5040.8     .07       0  5052.2      .1       0
  5477.8     .05       0  5574.4      .1       0
Bank Sta=5040.8,5052.2
XS Rating Curve= 0 ,0
Exp/Cntr=0.3,0.1

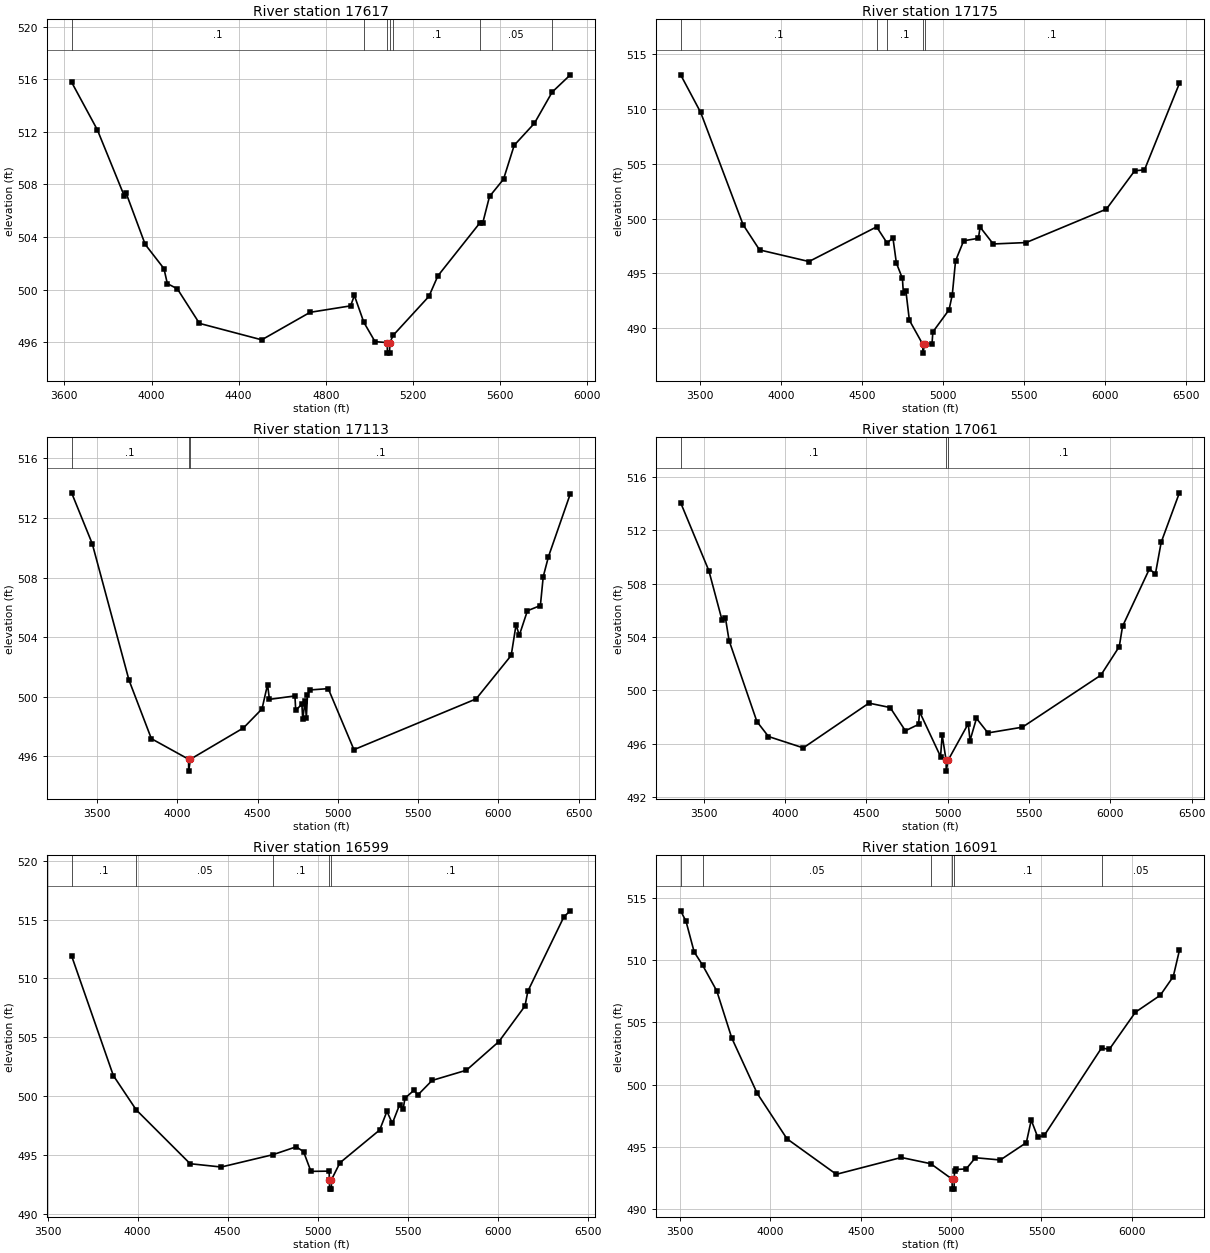
Type RM Length L Ch R = 1 ,17617   ,442,442,442
BEGIN DESCRIPTION:
UNT 022 in RCW 28.0
END DESCRIPTION:
XS GIS Cut Line= 3
      1988760.67     13468883.17      1987382.19     13469160.94
        1986525.       13469375.
#Sta/Elev= 30
  3633.2  515.77  3751.2  512.16  3874.5  507.15  3883.8  507.33    3971  503.45
  4057.2  501.61  4072.7  500.47  4118.4  500.08    4220  497.45  4506.1   496.2
  4728.1  498.29  4914.1  498.78  4931.4  499.57  4974.8  497.53  5026.3  496.06
  5082.3  495.99    5083  495.19  5093.1  495.19  5093.7  495.99  5110.5  496.56
  5273.6   499.5  5314.8  501.06  5508.4   505.1  5520.9  505.09  5551.8  507.09
  5616.1   508.4  5665.2  510.98    5758  512.65  5839.5  515.02  5922.9  516.33
#Mann= 7 ,-1 , 0
  3633.2      .1       0  4974.8     .16       0  5082.3     .07       0
  5093.7     .16       0  5110.5      .1       0  5508.4     .05       0
  5839.5      .1       0
Bank Sta=5082.3,5093.7
XS Rating Curve= 0 ,0
Exp/Cntr=0.3,0.1

Type RM Length L Ch R = 1 ,17175   ,62,62,62
BEGIN DESCRIPTION:
Mapping XS 3b6f0277
END DESCRIPTION:
XS GIS Cut Line= 6
      1988646.07     13468813.72      1987441.22     13469056.78
      1987298.86     13468803.31      1987205.11     13468792.89
       1987055.8     13468796.36      1985764.14     13468574.14
#Sta/Elev= 30
  3382.3  513.11  3505.8  509.68    3767  499.45  3868.6  497.15  4173.3  496.09
  4590.2  499.25  4654.9  497.77  4690.7  498.26  4712.1  495.95  4749.2  494.55
    4755  493.22  4770.6  493.42  4792.1  490.74  4874.8  488.54  4875.5  487.74
  4886.2  488.54  4931.8   488.6  4936.8  489.67  5036.7  491.69  5056.7  493.07
  5076.7  496.15  5126.8  497.98  5217.8  498.21    5228  499.23  5309.1  497.69
  5512.1  497.82  6006.7  500.87  6181.4  504.37  6241.3  504.44  6456.6  512.33
#Mann= 5 ,-1 , 0
  3382.3      .1       0  4590.2     .16       0  4654.9      .1       0
  4874.8     .07       0  4886.2      .1       0
Bank Sta=4874.8,4886.2
XS Rating Curve= 0 ,0
Exp/Cntr=0.3,0.1

Type RM Length L Ch R = 1 ,17113   ,52,52,52
BEGIN DESCRIPTION:
Mapping XS fc93a113
END DESCRIPTION:
XS GIS Cut Line= 6
      1988646.05     13468775.53      1987458.58     13469004.69
      1987378.72     13468785.94      1987330.11     13468737.33
       1987055.8     13468733.86      1985750.27     13468546.37
#Sta/Elev= 30
  3341.6  513.69  3470.3  510.27  3699.1  501.11  3838.4  497.18  4070.3   495.8
  4070.9     495  4081.7   495.8    4412   497.9  4527.7  499.18  4562.1  500.81
  4573.9  499.82  4732.6  500.05  4737.7  499.09  4776.1  499.49  4781.2  498.48
  4796.6  499.74  4803.7  498.56  4810.8  500.08  4824.9  500.45  4940.2  500.54
  5100.2  496.44  5861.3  499.85  6079.8  502.77  6110.1  504.83  6130.3  504.12
  6180.9  505.77  6261.7  506.12  6279.4  508.06  6312.2  509.41  6448.3  513.63
#Mann= 3 ,-1 , 0
  3341.6      .1       0  4070.3     .07       0  4081.7      .1       0
Bank Sta=4070.3,4081.7
XS Rating Curve= 0 ,0
Exp/Cntr=0.3,0.1

Type RM Length L Ch R = 1 ,17061   ,462,462,462
BEGIN DESCRIPTION:
Mapping XS 9e6abce9
END DESCRIPTION:
XS GIS Cut Line= 6
      1988625.21     13468733.87      1987496.77     13468952.61
      1987406.49     13468723.44      1987330.11     13468681.78
      1987076.63     13468685.25       1985758.6     13468504.89
#Sta/Elev= 30
  3358.1  514.05  3531.5  508.96    3613  505.24  3633.3  505.44  3655.9  503.73
  3826.9  497.67  3898.2  496.55  4112.1   495.7  4515.9  499.05  4646.2  498.72
  4739.9  496.98  4821.2  497.46  4826.9  498.41  4956.2  495.05  4966.2  496.66
  4990.5  494.76  4991.2  493.96  5001.9  494.76  5126.5  497.51  5137.5  496.25
    5177  497.91  5247.6  496.82  5459.6  497.25  5941.8  501.14  6055.1  503.28
  6075.3   504.8  6240.7   509.1  6277.1   508.7  6312.9  511.09  6424.9  514.79
#Mann= 3 ,-1 , 0
  3358.1      .1       0  4990.5     .07       0  5001.9      .1       0
Bank Sta=4990.5,5001.9
XS Rating Curve= 0 ,0
Exp/Cntr=0.3,0.1

Type RM Length L Ch R = 1 ,16599   ,508,508,508
BEGIN DESCRIPTION:
UNT 022 in RCW 27.0
END DESCRIPTION:
XS GIS Cut Line= 3
      1988482.88     13468469.97        1987125.       13468225.
      1985739.96     13468108.87
#Sta/Elev= 30
  3633.6  511.91  3865.2  501.74  3992.4  498.82  4291.9  494.24  4464.7  493.96
    4752  495.01  4881.3  495.68  4921.9  495.26  4962.6  493.59  5063.6  493.61
  5065.2  492.88  5065.8  492.08  5076.1  492.08  5076.7  492.88  5123.8  494.32
  5344.6  497.11  5384.7  498.69  5414.8  497.67  5454.9  499.25    5475  498.92
    5485  499.81  5535.2  500.49  5556.2  500.08  5635.6  501.32  5826.2  502.19
  6006.9  504.63  6151.4  507.65  6167.4  508.91  6368.1  515.25  6403.3  515.74
#Mann= 5 ,-1 , 0
  3633.6      .1       0  3992.4     .05       0    4752      .1       0
  5065.2     .07       0  5076.7      .1       0
Bank Sta=5065.2,5076.7
XS Rating Curve= 0 ,0
Exp/Cntr=0.3,0.1

Type RM Length L Ch R = 1 ,16091   ,485,485,485
BEGIN DESCRIPTION:
UNT 022 in RCW 26.0
END DESCRIPTION:
XS GIS Cut Line= 3
      1988541.51     13468449.16        1987225.       13467775.
        1986163.     13467060.25
#Sta/Elev= 30
  3503.8  513.96  3533.6  513.11  3578.5  510.66  3625.1   509.6  3703.6  507.53
  3786.8  503.74  3926.8  499.32    4092  495.66    4365  492.81  4724.5  494.16
  4887.5  493.66  5005.6  492.42  5006.2  491.62  5016.6  491.62  5017.2  492.42
    5019  493.06  5026.4   493.2  5083.4  493.24  5134.3  494.14  5272.2  493.96
  5416.2  495.35  5443.3  497.16  5479.3  495.79  5515.3  495.93  5832.2  502.95
  5875.2  502.84  6019.5  505.82  6157.1  507.18    6229  508.68    6263  510.78
#Mann= 6 ,-1 , 0
  3503.8      .1       0  3625.1     .05       0  4887.5      .1       0
  5005.6     .07       0  5017.2      .1       0  5832.2     .05       0
Bank Sta=5005.6,5017.2
XS Rating Curve= 0 ,0
Exp/Cntr=0.3,0.1

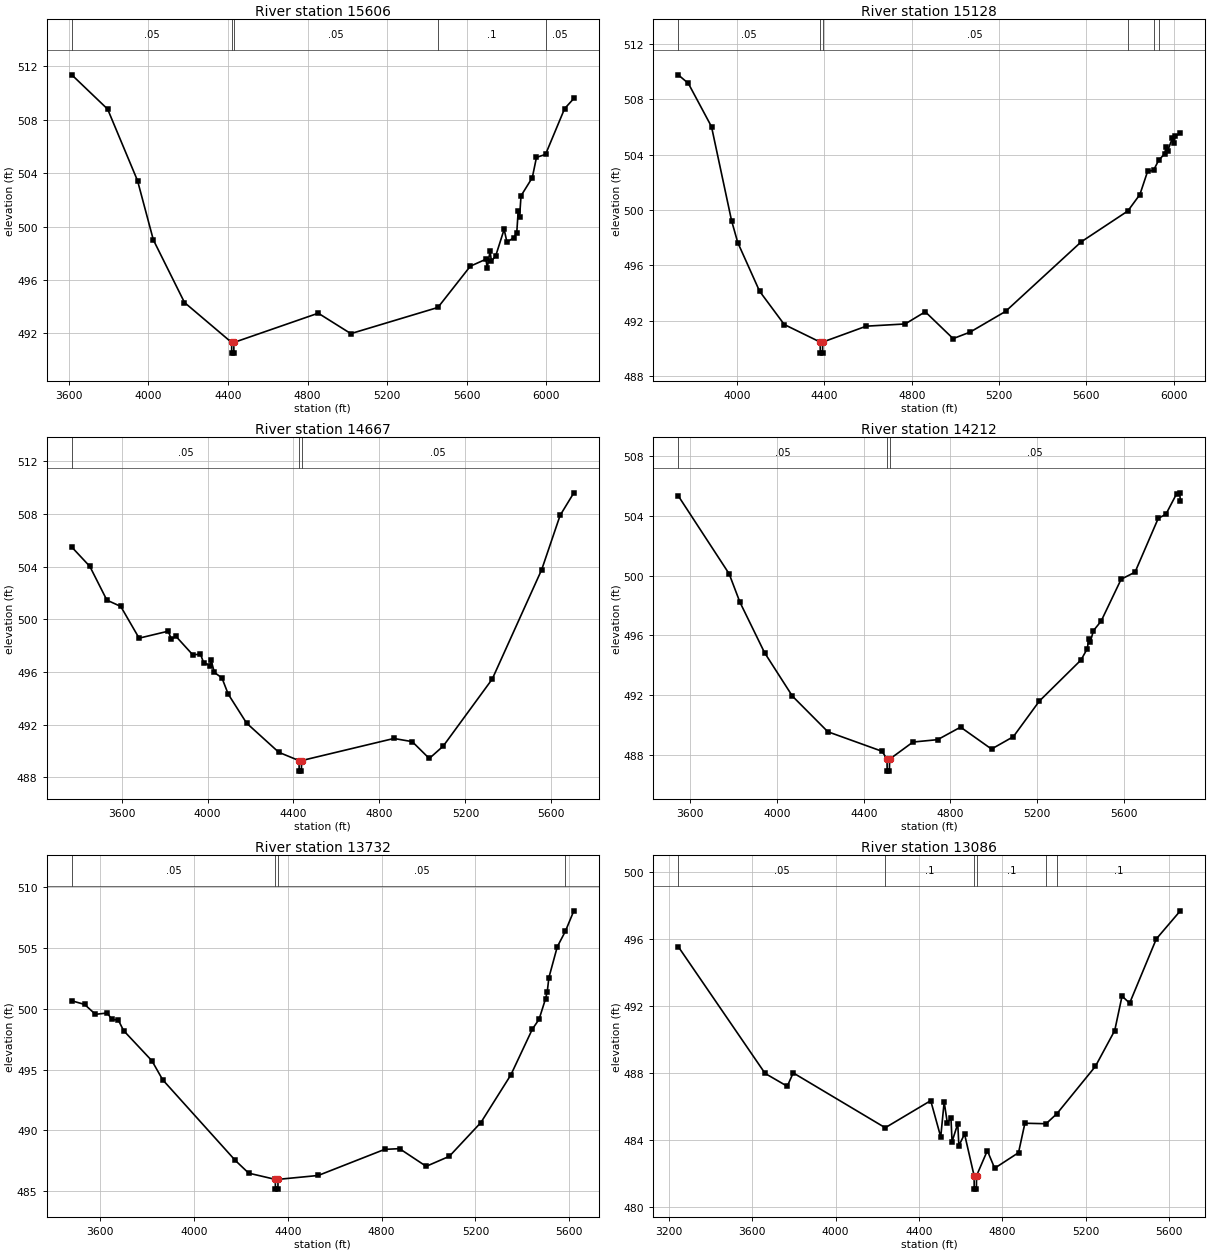
Type RM Length L Ch R = 1 ,15606   ,478,478,478
BEGIN DESCRIPTION:
UNT 022 in RCW 25.0
END DESCRIPTION:
XS GIS Cut Line= 3
      1988527.56     13468185.23        1987425.       13467375.
      1986583.15     13466581.09
#Sta/Elev= 30
  3614.3  511.36  3794.7  508.79  3945.2  503.43  4024.6     499  4181.3  494.31
  4418.3  491.32  4418.9  490.52  4429.3  490.52  4429.9  491.32  4854.1  493.51
    5018  491.98    5456  493.94  5619.1  497.03  5697.2  497.55  5704.1  496.92
  5718.3  498.16  5725.1  497.41  5746.6   497.8  5789.1  499.79  5803.2  498.83
  5838.4  499.17  5852.6  499.54  5859.9  501.19  5866.7   500.7    5874   502.3
  5930.7  503.66  5951.7  505.18  5997.3   505.4  6093.3  508.83  6139.7  509.59
#Mann= 5 ,-1 , 0
  3614.3     .05       0  4418.3    .035       0  4429.9     .05       0
    5456      .1       0  5997.3     .05       0
Bank Sta=4418.3,4429.9
XS Rating Curve= 0 ,0
Exp/Cntr=0.3,0.1

Type RM Length L Ch R = 1 ,15128   ,461,461,461
BEGIN DESCRIPTION:
UNT 022 in RCW 24.0
END DESCRIPTION:
XS GIS Cut Line= 3
      1988443.38     13467941.32        1987625.       13466975.
      1986893.88     13466244.25
#Sta/Elev= 30
  3730.4  509.78  3776.7  509.16  3882.8  506.03  3974.6  499.24    4003  497.65
    4103  494.13  4216.1  491.72  4380.6  490.45  4381.2  489.65  4391.7  489.65
  4392.2  490.45  4591.8   491.6  4769.9  491.76  4862.1  492.64  4989.6   490.7
  5067.4  491.17    5230  492.67  5576.5   497.7  5789.9  499.93  5845.2  501.12
  5880.6   502.8  5907.6  502.87    5931  503.59  5958.4  504.07  5965.4  504.59
  5972.5  504.28  5993.7  505.19  6000.8  504.83  6007.9  505.35  6030.4  505.55
#Mann= 6 ,-1 , 0
  3730.4     .05       0  4380.6    .035       0  4392.2     .05       0
  5789.9      .1       0  5907.6     .05       0    5931      .1       0
Bank Sta=4380.6,4392.2
XS Rating Curve= 0 ,0
Exp/Cntr=0.3,0.1

Type RM Length L Ch R = 1 ,14667   ,455,455,455
BEGIN DESCRIPTION:
UNT 022 in RCW 23.0
END DESCRIPTION:
XS GIS Cut Line= 3
      1988968.57     13468049.85        1987975.       13466725.
        1987575.       13466175.
#Sta/Elev= 30
  3368.4   505.5  3452.5  504.03  3531.7  501.47  3596.3  500.99  3681.7  498.58
  3817.1  499.11  3831.7   498.5  3852.5  498.73  3931.7  497.31  3967.1  497.37
  3981.7  496.73  4010.9   496.5  4017.1  496.89  4031.7  495.98  4067.1  495.56
  4096.3  494.33  4181.7  492.13  4331.7  489.91  4425.9  489.28  4426.5  488.48
    4437  488.48  4437.5  489.28  4867.1  490.96  4952.5  490.72  5031.8  489.44
  5096.7  490.38  5324.7  495.47    5555  503.79  5640.7  507.91  5704.5  509.62
#Mann= 3 ,-1 , 0
  3368.4     .05       0  4425.9    .035       0  4437.5     .05       0
Bank Sta=4425.9,4437.5
XS Rating Curve= 0 ,0
Exp/Cntr=0.3,0.1

Type RM Length L Ch R = 1 ,14212   ,480,480,480
BEGIN DESCRIPTION:
UNT 022 in RCW 22.0
END DESCRIPTION:
XS GIS Cut Line= 3
      1989246.34     13467633.18        1988325.       13466475.
      1987797.66     13465828.81
#Sta/Elev= 30
  3545.2  505.36  3779.8  500.13  3829.4  498.23  3943.1  494.84  4071.3  491.93
  4234.7  489.54  4484.6  488.23  4507.6   487.7  4508.1   486.9  4518.6   486.9
  4519.2   487.7  4627.1  488.85  4740.8  489.01  4846.5  489.85  4989.1  488.38
  5089.7  489.21  5209.7   491.6  5401.4  494.35  5430.1   495.1    5438  495.78
  5444.5  495.57  5458.8  496.32    5494  496.95  5586.6  499.77  5650.5  500.24
  5757.5  503.85  5792.7  504.12  5842.2   505.5  5856.6  505.56  5859.2  505.03
#Mann= 3 ,-1 , 0
  3545.2     .05       0  4507.6    .035       0  4519.2     .05       0
Bank Sta=4507.6,4519.2
XS Rating Curve= 0 ,0
Exp/Cntr=0.3,0.1

Type RM Length L Ch R = 1 ,13732   ,646,646,646
BEGIN DESCRIPTION:
UNT 022 in RCW 21.0
END DESCRIPTION:
XS GIS Cut Line= 3
      1989502.39     13467351.01      1989158.66     13466601.05
      1988174.99     13465724.99
#Sta/Elev= 30
  3477.8  500.64  3532.7  500.34  3578.7  499.53  3630.2  499.64  3647.7  499.11
  3676.2  499.06  3699.2  498.19  3819.7  495.72  3865.7  494.16  4175.7  487.54
  4232.7   486.5  4346.2  485.99  4346.8  485.19  4357.3  485.19  4357.9  485.99
  4529.3  486.31  4812.7  488.45  4876.3  488.51    4990  487.06  5088.6  487.88
  5223.3  490.65  5351.2  494.56  5443.1  498.32  5471.6  499.12  5499.5  500.82
  5506.7   501.4  5513.4  502.53  5549.3  505.07  5583.8  506.34    5620  508.02
#Mann= 4 ,-1 , 0
  3477.8     .05       0  4346.2    .035       0  4357.9     .05       0
  5583.8      .1       0
Bank Sta=4346.2,4357.9
XS Rating Curve= 0 ,0
Exp/Cntr=0.3,0.1

Type RM Length L Ch R = 1 ,13086   ,44,44,44
BEGIN DESCRIPTION:
Mapping XS d722f5c3
END DESCRIPTION:
XS GIS Cut Line= 6
      1990027.13     13466940.86      1989216.59     13465987.67
      1989341.39     13465949.14      1989334.88     13465853.65
      1989163.44     13465816.76      1988701.19       13465246.
#Sta/Elev= 30
  3244.4  495.56  3661.2  487.98  3767.7  487.21  3796.3  488.01    4238  484.73
  4456.3  486.35  4504.4  484.18  4520.9  486.28  4535.8  485.03  4553.5   485.3
  4558.8   483.9  4586.2  484.97  4591.4  483.66  4618.8  484.35  4664.6  481.86
  4665.2  481.06  4675.7  481.06  4676.3  481.86  4728.1  483.36  4763.3  482.31
  4877.8  483.24  4908.4     485    5010  484.97    5062  485.57  5246.8   488.4
  5339.5  490.54  5374.7   492.6  5411.2  492.18  5539.2  496.02  5654.4   497.7
#Mann= 6 ,-1 , 0
  3244.4     .05       0    4238      .1       0  4664.6     .07       0
  4676.3      .1       0    5010     .05       0    5062      .1       0
Bank Sta=4664.6,4676.3
XS Rating Curve= 0 ,0
Exp/Cntr=0.3,0.1