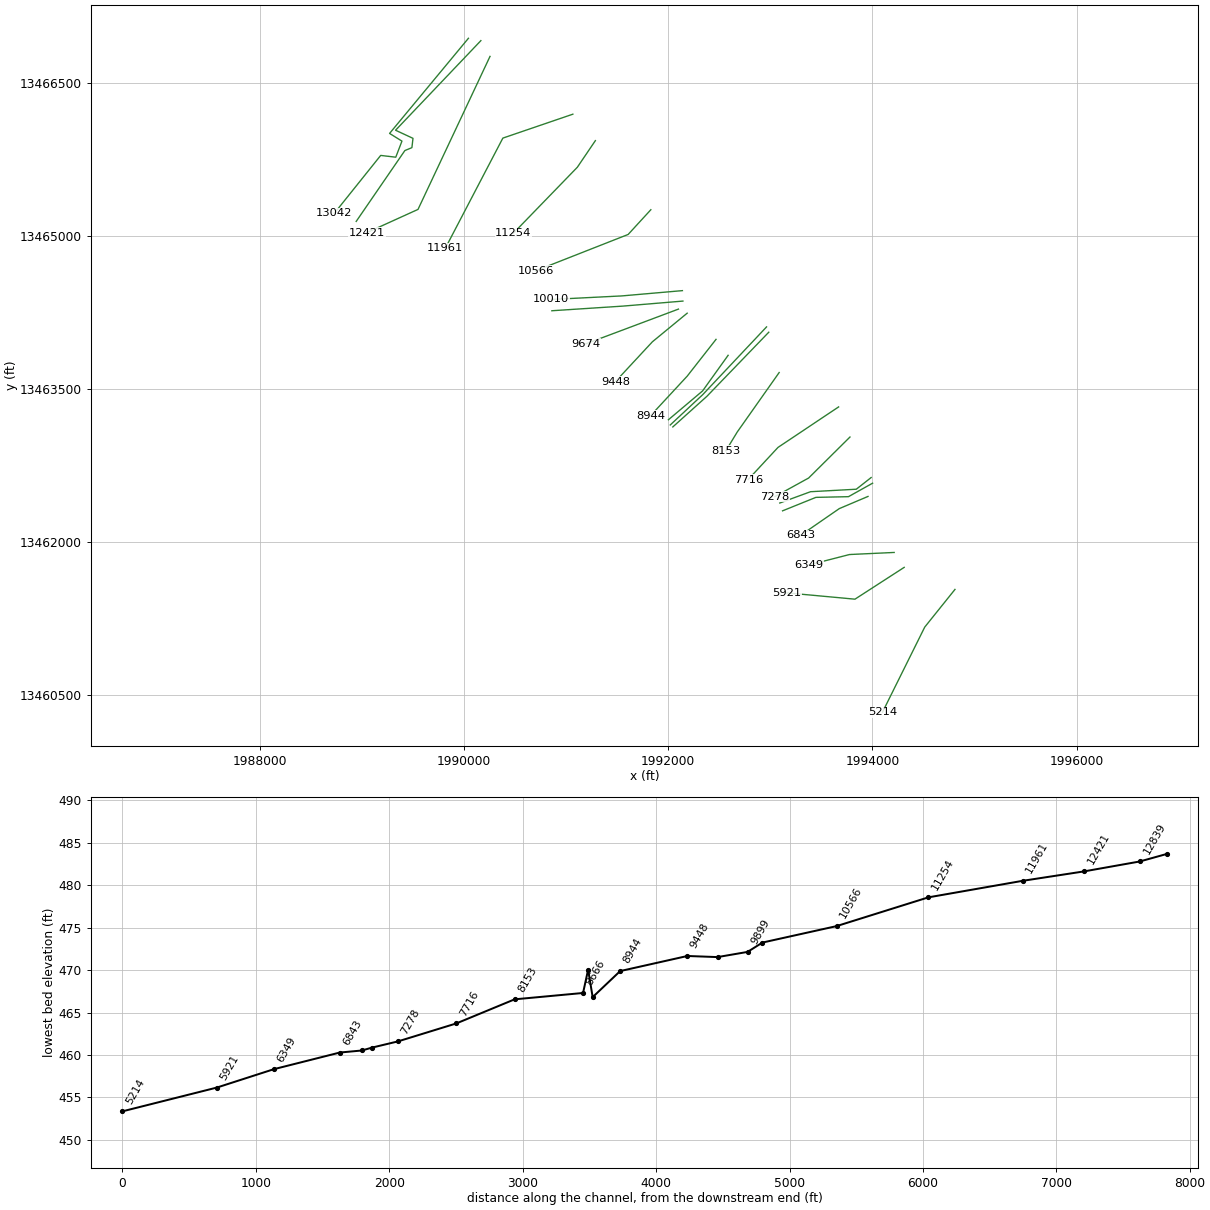
HEC-RAS study UNT 022 in RCW.prj: UNT 022 in RCW Base Level Engineering

--- UNT 022 in RCW.g01 (geometry) --- (continued)

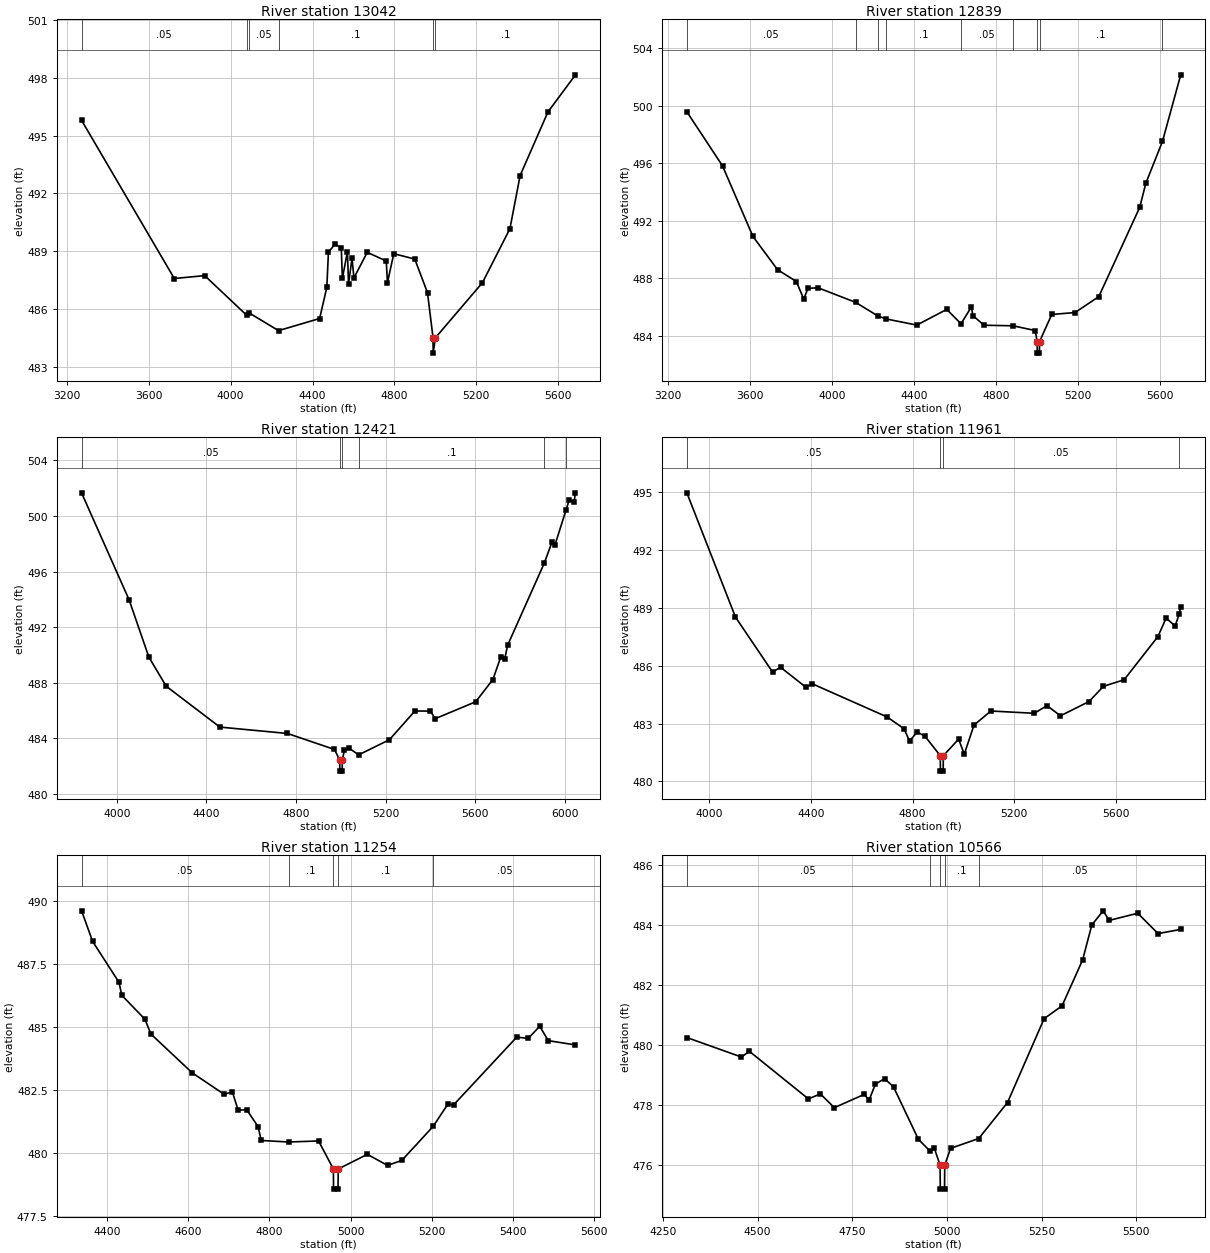
Type RM Length L Ch R = 1 ,13042   ,203,203,203
BEGIN DESCRIPTION:
Mapping XS 795978de
END DESCRIPTION:
XS GIS Cut Line= 6
      1990042.34     13466934.37      1989269.97     13466001.99
      1989391.14     13465926.45      1989330.54     13465769.02
      1989182.97     13465786.38      1988729.74     13465220.39
#Sta/Elev= 30
  3272.2   495.8  3724.9  487.58  3873.4  487.73  4079.3  485.66  4090.4  485.79
    4234  484.87  4434.7   485.5  4469.9  487.12  4477.7  488.94  4509.7  489.37
  4540.5  489.17  4545.8  487.59  4570.5  488.97  4575.9   487.3  4592.9  488.63
  4602.3  487.61  4667.2  488.94  4760.2  488.49  4765.9  487.36  4796.9  488.87
  4899.5  488.59  4961.6  486.84  4988.6   484.5  4989.2   483.7  5000.3   484.5
  5229.8  487.36  5364.2  490.17  5413.8  492.93  5549.9  496.24  5684.3  498.17
#Mann= 6 ,-1 , 0
  3272.2     .05       0  4079.3      .1       0  4090.4     .05       0
    4234      .1       0  4988.6     .07       0  5000.3      .1       0
Bank Sta=4988.6,5000.3
XS Rating Curve= 0 ,0
Exp/Cntr=0.3,0.1

Type RM Length L Ch R = 1 ,12839   ,418,418,418
BEGIN DESCRIPTION:
UNT 022 in RCW 20.0
END DESCRIPTION:
XS GIS Cut Line= 6
      1990164.28     13466911.35      1989328.57     13466033.24
      1989499.14     13465953.82      1989488.72     13465862.67
      1989419.71     13465834.03      1988943.04      13465139.8
#Sta/Elev= 30
  3291.7  499.59  3465.6  495.83  3614.1  490.92  3734.2  488.61    3826  487.79
  3861.6  486.57  3882.7  487.32  3932.4  487.35  4114.9  486.34  4222.6   485.4
  4262.8  485.19  4413.3  484.76  4559.4  485.85  4629.1  484.85  4679.6  486.02
  4687.1  485.42  4741.2  484.75  4882.9  484.71  4991.2  484.38  5000.4  483.61
    5001  482.81  5011.5  482.81  5012.1  483.61  5071.7   485.5  5185.1  485.63
  5301.2  486.74  5500.9  492.95  5530.6  494.62  5611.7  497.53  5700.8  502.16
#Mann= 9 ,-1 , 0
  3291.7     .05       0  4114.9      .1       0  4222.6     .05       0
  4262.8      .1       0  4629.1     .05       0  4882.9      .1       0
  5000.4     .07       0  5012.1      .1       0  5611.7     .05       0
Bank Sta=5000.4,5012.1
XS Rating Curve= 0 ,0
Exp/Cntr=0.3,0.1

Type RM Length L Ch R = 1 ,12421   ,460,460,460
BEGIN DESCRIPTION:
UNT 022 in RCW 19.0
END DESCRIPTION:
XS GIS Cut Line= 3
      1990253.73     13466756.89      1989548.42      13465257.3
      1989049.16     13465030.36
#Sta/Elev= 30
  3842.5  501.66  4054.6  493.97    4143  489.84  4220.3  487.75    4460  484.81
  4761.8  484.35  4971.8   483.2  4995.1  482.44  4995.7  481.64  5006.2  481.64
  5006.8  482.44    5016  483.14  5038.1  483.28  5079.6  482.81  5217.2   483.9
  5331.2  485.97  5399.6  485.96  5422.4  485.42  5602.3  486.63  5679.2  488.23
  5714.1  489.84  5731.7  489.69  5745.1   490.7  5909.6  496.64  5942.8  498.11
  5955.8  497.88  6006.3  500.45  6019.5  501.13  6041.7  501.01  6048.1  501.67
#Mann= 6 ,-1 , 0
  3842.5     .05       0  4995.1     .03       0  5006.8     .05       0
  5079.6      .1       0  5909.6     .05       0  6006.3      .1       0
Bank Sta=4995.1,5006.8
XS Rating Curve= 0 ,0
Exp/Cntr=0.3,0.1

Type RM Length L Ch R = 1 ,11961   ,707,707,707
BEGIN DESCRIPTION:
Mapping XS 1ea0f408
END DESCRIPTION:
XS GIS Cut Line= 3
       1991065.3     13466190.44      1990379.58     13465956.08
      1989815.36     13464875.37
#Sta/Elev= 30
  3911.4  494.97  4102.8  488.52  4248.8  485.67  4280.1  485.92  4379.3  484.89
  4405.3  485.06  4699.7  483.34  4765.9  482.73    4788  482.09  4817.8  482.56
  4848.6  482.34  4908.9  481.33  4909.4  480.53  4920.3  480.53  4920.8  481.33
  4981.1  482.19  5003.2  481.41  5041.7  482.92    5108  483.65    5279  483.53
  5328.8  483.93  5381.8   483.4  5494.2  484.14    5551  484.93  5632.4  485.27
  5765.4  487.51  5797.8  488.47  5833.1  488.06    5849  488.67  5855.2  489.07
#Mann= 4 ,-1 , 0
  3911.4     .05       0  4908.9     .03       0  4920.8     .05       0
    5849      .1       0
Bank Sta=4908.9,4920.8
XS Rating Curve= 0 ,0
Exp/Cntr=0.3,0.1

Type RM Length L Ch R = 1 ,11254   ,688,688,688
BEGIN DESCRIPTION:
Mapping XS 7beb51f8
END DESCRIPTION:
XS GIS Cut Line= 3
      1991285.84     13465931.35      1991109.18     13465670.49
      1990482.03     13465023.37
#Sta/Elev= 30
  4337.6  489.62  4364.6  488.41  4429.8  486.78  4436.5  486.27  4493.5  485.32
  4508.4  484.73  4610.2  483.19  4687.9  482.35    4709  482.43  4723.1  481.71
  4744.2  481.73  4772.5  481.05  4779.7  480.51  4847.2  480.45  4921.2  480.49
  4957.6  479.38  4958.1  478.58  4969.1  478.58  4969.6  479.38  5041.3  479.96
    5091  479.52  5126.2  479.72  5203.4  481.07  5239.4  481.95  5253.6  481.92
  5409.2  484.61  5437.5  484.56  5465.8  485.04  5486.9  484.47  5553.8   484.3
#Mann= 5 ,-1 , 0
  4337.6     .05       0  4847.2      .1       0  4957.6     .07       0
  4969.6      .1       0  5203.4     .05       0
Bank Sta=4957.6,4969.6
XS Rating Curve= 0 ,0
Exp/Cntr=0.3,0.1

Type RM Length L Ch R = 1 ,10566   ,556,556,556
BEGIN DESCRIPTION:
UNT 022 in RCW 18.0
END DESCRIPTION:
XS GIS Cut Line= 3
      1991829.22     13465254.24      1991606.94     13465011.89
      1990699.34     13464655.01
#Sta/Elev= 30
  4313.4  480.25  4457.5   479.6  4478.5  479.79  4634.5   478.2  4665.8  478.37
  4702.8  477.91  4781.4  478.35  4794.8  478.17  4811.1  478.69  4835.5  478.88
  4859.2   478.6  4924.9  476.85  4954.8  476.47  4966.7  476.56  4982.1  475.99
  4982.6  475.19  4993.8  475.19  4994.3  475.99  5009.7  476.55  5084.1  476.88
  5160.1  478.08  5256.8  480.88  5304.2  481.31  5358.4  482.84  5382.8  484.01
  5412.6  484.48  5428.7  484.16    5504   484.4  5557.7  483.72  5617.5  483.86
#Mann= 5 ,-1 , 0
  4313.4     .05       0  4954.8      .1       0  4982.1     .07       0
  4994.3      .1       0  5084.1     .05       0
Bank Sta=4982.1,4994.3
XS Rating Curve= 0 ,0
Exp/Cntr=0.3,0.1

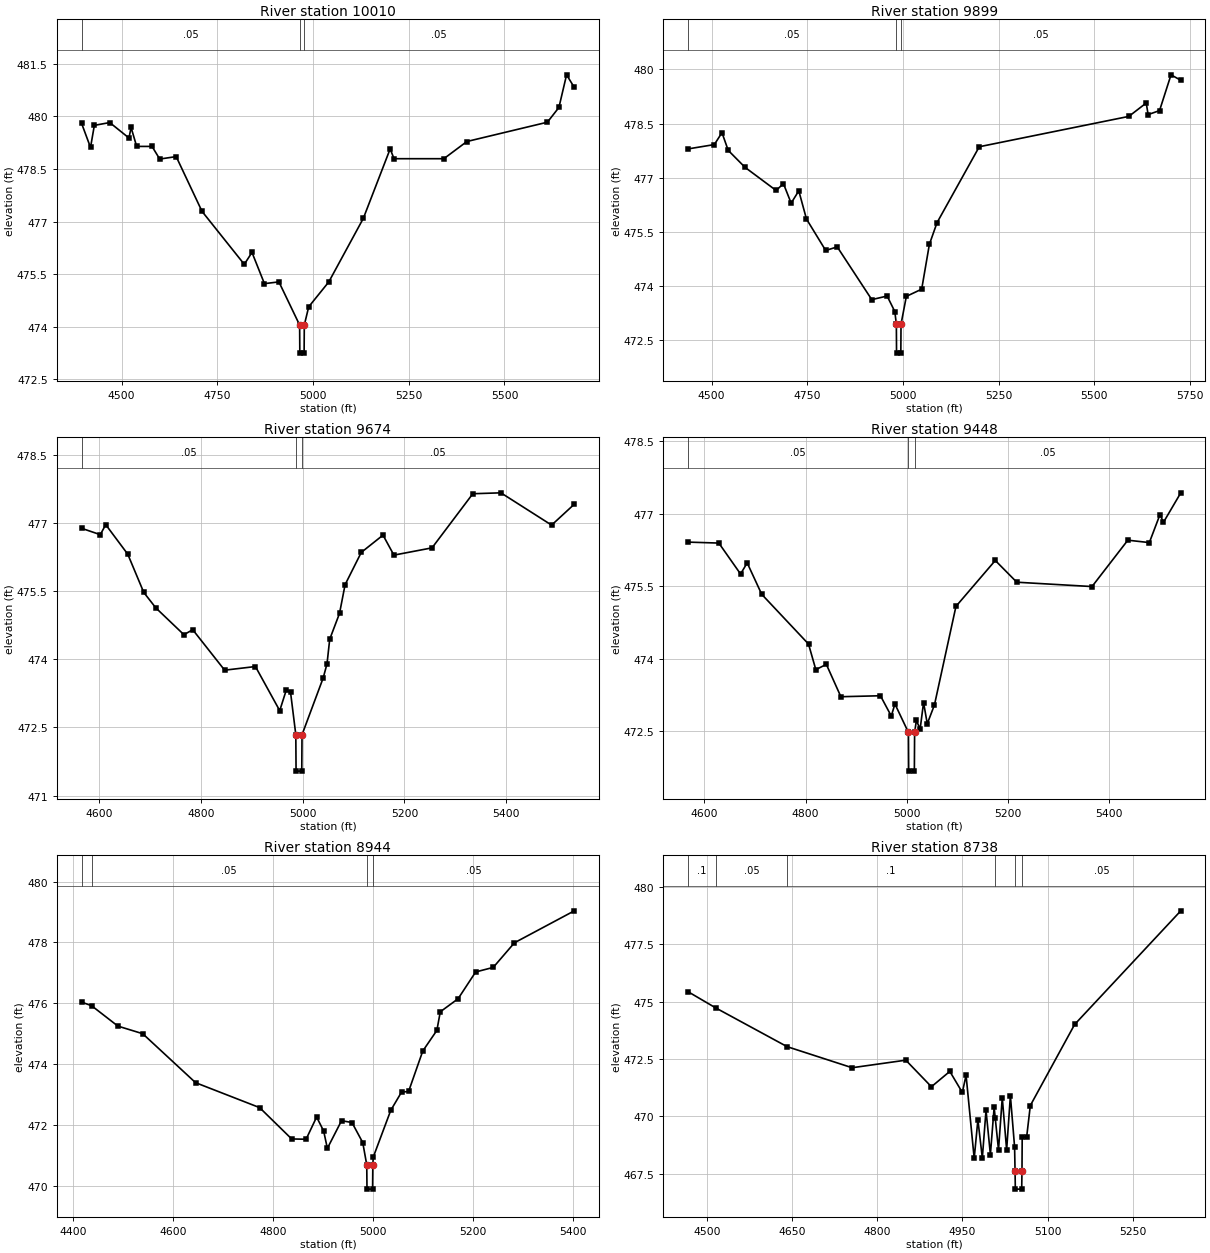
Type RM Length L Ch R = 1 ,10010   ,111,111,111
BEGIN DESCRIPTION:
UNT 022 in RCW 17.0
END DESCRIPTION:
XS GIS Cut Line= 3
      1992138.31      13464461.3      1991544.95      13464409.5
      1990854.84     13464374.78
#Sta/Elev= 30
  4395.7   479.8  4419.1  479.11  4429.1  479.74  4469.3  479.82  4519.5  479.38
    4525  479.68  4539.6  479.14  4579.7  479.14  4599.8  478.78  4642.8  478.85
  4710.2  477.29  4820.6  475.78  4840.7  476.12  4873.2  475.23    4911  475.28
  4965.1  474.05  4965.6  473.25  4976.8  473.25  4977.3  474.05  4988.8  474.57
  5041.3  475.28  5131.4  477.09  5201.5  479.07  5211.5  478.79  5341.7  478.79
  5401.8  479.28    5612  479.83  5642.1  480.25  5662.1  481.18  5682.3  480.82
#Mann= 3 ,-1 , 0
  4395.7     .05       0  4965.1    .035       0  4977.3     .05       0
Bank Sta=4965.1,4977.3
XS Rating Curve= 0 ,0
Exp/Cntr=0.3,0.1

Type RM Length L Ch R = 1 ,9899    ,225,225,225
BEGIN DESCRIPTION:
UNT 022 in RCW 16.0
END DESCRIPTION:
XS GIS Cut Line= 3
      1992143.43     13464358.86       1991555.8     13464309.67
      1990859.58     13464264.12
#Sta/Elev= 30
  4438.5   477.8  4507.2  477.92  4527.2  478.25  4543.5  477.76  4587.5  477.29
  4668.7  476.65  4687.8  476.84  4707.9   476.3  4727.9  476.64    4748  475.86
  4798.2  474.99  4828.3  475.09  4918.6  473.63  4958.7  473.73  4978.8   473.3
  4982.8  472.95  4983.3  472.15  4994.5  472.15    4995  472.95  5008.9  473.72
    5049  473.92  5069.1  475.16  5089.1  475.76  5199.4  477.86  5590.2   478.7
  5635.6  479.07  5640.6  478.75  5670.4  478.86  5700.4  479.85  5725.9   479.7
#Mann= 3 ,-1 , 0
  4438.5     .05       0  4982.8    .035       0    4995     .05       0
Bank Sta=4982.8,4995
XS Rating Curve= 0 ,0
Exp/Cntr=0.3,0.1

Type RM Length L Ch R = 1 ,9674    ,226,226,226
BEGIN DESCRIPTION:
Mapping XS 9a571221
END DESCRIPTION:
XS GIS Cut Line= 2
      1992099.44     13464280.22      1991193.21     13463939.95
#Sta/Elev= 30
  4565.6  476.88  4602.4  476.74  4613.1  476.96  4656.4  476.31  4687.8  475.47
  4711.5  475.13  4766.7  474.54    4784  474.65  4846.7  473.76  4907.2  473.84
  4954.9  472.87  4967.7  473.32  4976.2  473.27  4986.5  472.34    4987  471.54
  4998.2  471.54  4998.7  472.34  5040.3  473.59  5047.8   473.9  5053.1  474.44
  5072.4  475.01  5083.3  475.64  5115.1  476.35  5157.8  476.73  5179.2  476.29
  5254.1  476.45  5334.2  477.64  5389.4  477.66    5489  476.95  5533.6  477.41
#Mann= 3 ,-1 , 0
  4565.6     .05       0  4986.5    .035       0  4998.7     .05       0
Bank Sta=4986.5,4998.7
XS Rating Curve= 0 ,0
Exp/Cntr=0.3,0.1

Type RM Length L Ch R = 1 ,9448    ,504,504,504
BEGIN DESCRIPTION:
UNT 022 in RCW 15.0
END DESCRIPTION:
XS GIS Cut Line= 3
      1992185.14     13464240.23      1991843.75     13463959.38
      1991482.15      13463569.8
#Sta/Elev= 30
  4567.6  476.41  4628.5  476.39  4671.4  475.75  4684.5  475.98  4713.2  475.33
  4805.7   474.3  4820.1  473.77  4840.9  473.88  4869.6  473.21  4947.8  473.23
  4969.2  472.81  4976.4  473.06  5003.1  472.47  5003.6  471.67  5014.8  471.67
  5015.3  472.47  5018.8  472.72  5026.2  472.54    5033  473.09  5040.3  472.65
  5054.5  473.04    5097  475.08  5174.7  476.03  5217.2  475.58  5365.8  475.49
  5436.6  476.45  5479.1   476.4  5500.1  476.98    5507  476.82  5541.2  477.43
#Mann= 3 ,-1 , 0
  4567.6     .05       0  5003.1    .035       0  5015.3     .05       0
Bank Sta=5003.1,5015.3
XS Rating Curve= 0 ,0
Exp/Cntr=0.3,0.1

Type RM Length L Ch R = 1 ,8944    ,206,206,206
BEGIN DESCRIPTION:
UNT 022 in RCW 14.0
END DESCRIPTION:
XS GIS Cut Line= 3
      1992467.71     13463983.74      1992185.14     13463623.04
      1991825.75     13463235.01
#Sta/Elev= 30
  4416.5  476.04  4436.6  475.92  4489.3  475.25    4539     475  4644.9  473.39
  4773.2  472.57  4837.4  471.54  4866.3  471.53  4887.4  472.26  4901.5   471.8
  4908.9  471.23  4937.3  472.14  4958.2  472.08  4979.8  471.42  4987.8  470.69
  4988.3  469.89  4999.5  469.89    5000  470.69  5000.8  470.94  5035.9  472.48
  5057.5  473.08  5071.6   473.1    5100  474.43  5128.3  475.11  5135.1  475.72
  5170.8  476.15    5206  477.03  5241.2  477.18  5283.7  477.99  5403.6  479.04
#Mann= 4 ,-1 , 0
  4416.5      .1       0  4436.6     .05       0  4987.8    .035       0
    5000     .05       0
Bank Sta=4987.8,5000
XS Rating Curve= 0 ,0
Exp/Cntr=0.3,0.1

Type RM Length L Ch R = 1 ,8738    ,34,34,34
BEGIN DESCRIPTION:
Mapping XS 5d5e7178
END DESCRIPTION:
XS GIS Cut Line= 3
       1992586.2     13463827.49      1992336.18     13463478.51
      1992001.52     13463195.94
#Sta/Elev= 30
    4467  475.44  4515.9  474.73  4641.4  473.04  4755.8  472.12  4850.3  472.45
  4895.4  471.29  4927.8  471.96  4949.8  471.04  4956.4  471.79  4970.7  468.16
  4977.2  469.85    4985  468.18  4991.5  470.26  4999.2  468.33  5005.8  470.39
  5007.7  469.93  5013.5  468.54  5020.1  470.81  5027.8  468.53  5034.4   470.9
  5041.8  468.66  5042.6  467.62  5043.1  466.82  5054.3  466.82  5054.8  467.62
  5055.2   469.1    5063  469.09  5069.5  470.47  5147.5  474.01  5334.3  478.97
#Mann= 6 ,-1 , 0
    4467      .1       0  4515.9     .05       0  4641.4      .1       0
  5007.7     .05       0  5042.6     .07       0  5054.8     .05       0
Bank Sta=5042.6,5054.8
XS Rating Curve= 0 ,0
Exp/Cntr=0.3,0.1

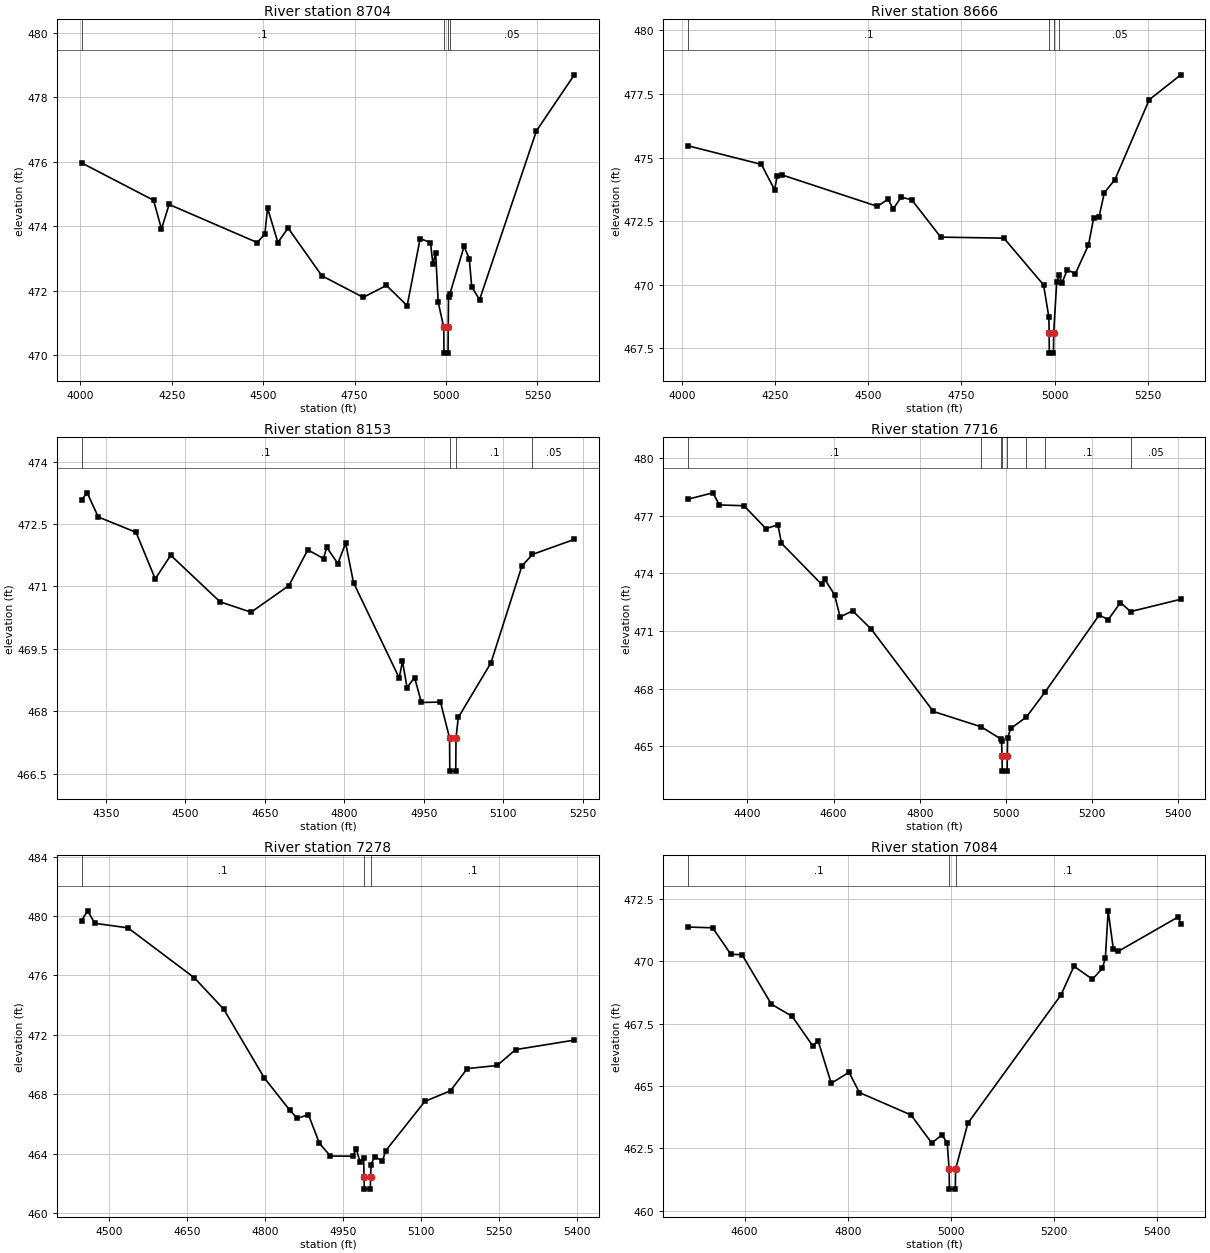
Type RM Length L Ch R = 1 ,8704    ,38,38,38
BEGIN DESCRIPTION:
Mapping XS 53d0e368
END DESCRIPTION:
XS GIS Cut Line= 3
      1992962.73     13464105.95      1992336.18     13463440.75
      1992019.23     13463144.58
#Sta/Elev= 30
  4003.1  475.96  4200.1   474.8  4221.6  473.91  4242.6  474.67  4483.4  473.49
  4504.4  473.75  4511.7  474.56    4540  473.49  4567.9  473.94  4660.2  472.46
  4773.5  471.79    4837  472.16  4893.6  471.53    4929  473.61  4957.3  473.49
  4964.2  472.81  4971.5  473.18  4978.4  471.64  4993.7  470.86  4994.2  470.06
  5005.4  470.06  5005.9  470.86  5006.7   471.8  5010.3  471.89  5049.2  473.37
  5063.4  472.99  5070.2  472.11  5091.7  471.72    5247  476.95  5350.7  478.69
#Mann= 4 ,-1 , 0
  4003.1      .1       0  4993.7     .07       0  5005.9      .1       0
  5010.3     .05       0
Bank Sta=4993.7,5005.9
XS Rating Curve= 0 ,0
Exp/Cntr=0.3,0.1

Type RM Length L Ch R = 1 ,8666    ,513,513,513
BEGIN DESCRIPTION:
UNT 022 in RCW 13.0
END DESCRIPTION:
XS GIS Cut Line= 3
      1992984.42     13464053.84      1992377.85     13463425.12
      1992044.54     13463125.66
#Sta/Elev= 30
  4016.5  475.46  4213.2  474.73  4248.7  473.73  4255.7  474.28  4269.8  474.31
  4524.5  473.08  4552.8  473.36    4567  472.98  4588.1  473.44  4616.4  473.34
  4694.3  471.87  4863.8  471.83  4970.2  469.99  4984.4  468.72  4985.1  468.11
  4985.6  467.31  4996.8  467.31  4997.3  468.11  5005.4   470.1  5012.3  470.38
  5019.6  470.07  5033.8  470.59  5055.3  470.43  5090.6  471.56  5104.8  472.64
    5119  472.67  5133.2  473.62  5161.6  474.13  5253.5  477.27  5338.2  478.25
#Mann= 4 ,-1 , 0
  4016.5      .1       0  4985.1     .07       0  4997.3      .1       0
  5012.3     .05       0
Bank Sta=4985.1,4997.3
XS Rating Curve= 0 ,0
Exp/Cntr=0.3,0.1

Type RM Length L Ch R = 1 ,8153    ,437,437,437
BEGIN DESCRIPTION:
UNT 022 in RCW 12.0
END DESCRIPTION:
XS GIS Cut Line= 3
      1993086.16     13463658.59        1992675.       13463075.
      1992563.18     13462890.41
#Sta/Elev= 30
  4304.3  473.08  4314.9  473.25  4335.8  472.67  4407.2   472.3  4443.3  471.18
  4472.5  471.75  4565.6  470.63  4624.1  470.38  4695.5  471.02  4731.2  471.88
  4760.8  471.67  4766.9  471.94  4787.8  471.55  4802.6  472.04  4817.4  471.09
  4903.6   468.8  4909.8   469.2  4918.4  468.57  4932.6  468.81  4945.5  468.21
  4981.5  468.22  4998.6  467.36  4999.1  466.56  5010.3  466.56  5010.8  467.36
  5015.1  467.85  5076.6  469.16  5135.1  471.49  5155.1  471.77    5234  472.13
#Mann= 4 ,-1 , 0
  4304.3      .1       0  4998.6     .07       0  5010.8      .1       0
  5155.1     .05       0
Bank Sta=4998.6,5010.8
XS Rating Curve= 0 ,0
Exp/Cntr=0.3,0.1

Type RM Length L Ch R = 1 ,7716    ,438,438,438
BEGIN DESCRIPTION:
UNT 022 in RCW 11.0
END DESCRIPTION:
XS GIS Cut Line= 3
      1993668.56     13463321.74        1993075.       13462925.
      1992782.28     13462609.94
#Sta/Elev= 30
  4262.1  477.85  4319.9  478.18  4334.9  477.55  4391.9  477.51    4443  476.32
  4470.9  476.52    4479  475.56  4572.1  473.43  4579.1   473.7  4602.2  472.89
  4615.2  471.73  4644.2  472.05  4687.4   471.1  4831.7  466.82    4943  466.02
  4987.7   465.4    4990  465.26  4991.2  464.52  4991.7  463.72  5002.9  463.72
  5003.4  464.52  5004.1  465.46  5011.5  465.94  5047.7  466.53  5091.1  467.83
  5216.7  471.83  5237.7  471.59    5266  472.48  5289.6  472.01  5406.1  472.65
#Mann= 8 ,-1 , 0
  4262.1      .1       0    4943     .16       0  4987.7      .1       0
  4991.2     .07       0  5003.4      .1       0  5047.7     .16       0
  5091.1      .1       0  5289.6     .05       0
Bank Sta=4991.2,5003.4
XS Rating Curve= 0 ,0
Exp/Cntr=0.3,0.1

Type RM Length L Ch R = 1 ,7278    ,194,194,194
BEGIN DESCRIPTION:
UNT 022 in RCW 10.0
END DESCRIPTION:
XS GIS Cut Line= 3
      1993779.67     13463026.59        1993375.       13462625.
      1993045.29     13462443.26
#Sta/Elev= 30
  4447.8  479.69  4459.3  480.35  4473.4  479.51  4537.1   479.2  4664.4  475.84
    4721  473.72  4798.7   469.1  4848.2   466.9  4862.4  466.37  4883.6  466.62
  4904.8  464.68    4926  463.83  4968.4  463.82  4975.5  464.29  4982.6  463.46
  4989.7  463.67  4990.5   462.4    4991   461.6  5002.5   461.6    5003   462.4
  5003.8  463.25  5010.8  463.79  5025.9   463.5  5031.7  464.17  5107.3  467.51
  5156.6  468.23  5188.7  469.72  5246.3  469.93  5281.6     471  5394.4  471.64
#Mann= 3 ,-1 , 0
  4447.8      .1       0  4990.5     .07       0    5003      .1       0
Bank Sta=4990.5,5003
XS Rating Curve= 0 ,0
Exp/Cntr=0.3,0.1

Type RM Length L Ch R = 1 ,7084    ,76,76,76
BEGIN DESCRIPTION:
Mapping XS dd761911
END DESCRIPTION:
XS GIS Cut Line= 4
      1993987.39     13462629.57      1993841.59     13462515.02
      1993393.67     13462490.71      1993092.12     13462379.79
#Sta/Elev= 30
  4490.4  471.37  4538.1  471.34  4573.4  470.28  4595.2  470.26    4652  468.28
  4692.4  467.79  4732.5   466.6  4742.5  466.82    4768  465.11  4802.6  465.55
  4822.6  464.74  4922.8  463.84  4962.8  462.72  4982.9  463.04  4992.9  462.72
  4996.6  461.67  4997.1  460.87  5008.6  460.87  5009.1  461.67  5032.9  463.51
  5213.5  468.65  5238.6   469.8  5274.4  469.28  5293.5  469.71  5299.5  470.13
  5304.9  472.02  5314.8  470.51  5324.7   470.4  5441.2  471.78  5445.7  471.48
#Mann= 3 ,-1 , 0
  4490.4      .1       0  4996.6     .07       0  5009.1      .1       0
Bank Sta=4996.6,5009.1
XS Rating Curve= 0 ,0
Exp/Cntr=0.3,0.1

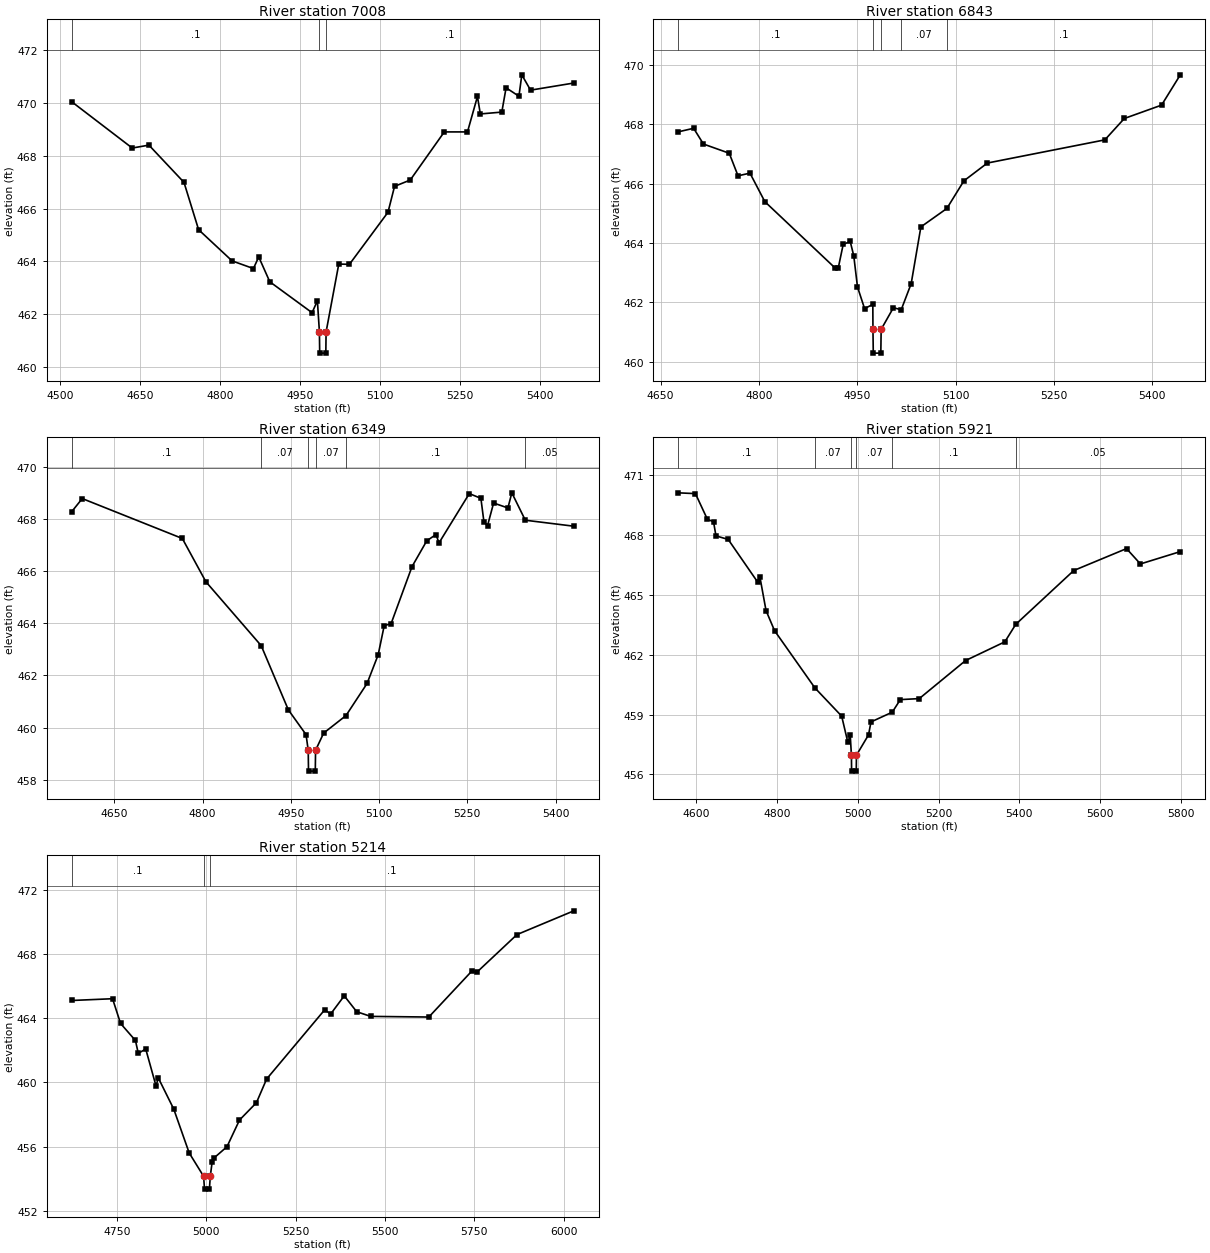
Type RM Length L Ch R = 1 ,7008    ,165,165,165
BEGIN DESCRIPTION:
Mapping XS b2132ee4
END DESCRIPTION:
XS GIS Cut Line= 4
      1994001.33     13462574.05       1993765.2      13462442.1
      1993445.76     13462435.15      1993119.71     13462303.35
#Sta/Elev= 30
    4522  470.04  4635.4  468.29  4666.7   468.4  4732.5  466.99  4759.9   465.2
  4822.7  464.02  4862.7  463.73  4872.7  464.17  4893.4  463.23  4972.7  462.06
  4982.7  462.51  4986.5  461.33    4987  460.53  4998.5  460.53    4999  461.33
  5022.8   463.9  5042.8  463.89  5115.1  465.86  5127.4  466.84  5156.9  467.08
  5220.7   468.9  5264.2   468.9  5282.9  470.24  5288.3  469.58  5328.6  469.65
  5336.6  470.57  5360.7  470.25  5366.1  471.06  5382.5  470.48  5463.7  470.75
#Mann= 3 ,-1 , 0
    4522      .1       0  4986.5     .07       0    4999      .1       0
Bank Sta=4986.5,4999
XS Rating Curve= 0 ,0
Exp/Cntr=0.3,0.1

Type RM Length L Ch R = 1 ,6843    ,494,494,494
BEGIN DESCRIPTION:
UNT 022 in RCW 9.0
END DESCRIPTION:
XS GIS Cut Line= 3
      1993956.65     13462444.47        1993675.       13462325.
      1993296.68     13462063.57
#Sta/Elev= 30
  4676.8  467.74  4700.3  467.86  4715.2  467.33  4754.6  467.02    4768  466.26
  4786.2  466.35  4808.9  465.39  4915.4  463.17  4920.9  463.16  4928.4  463.95
  4939.1  464.05  4944.5  463.57  4950.2  462.52    4961  461.79  4973.6  461.93
  4973.8  461.09  4974.3  460.29  4985.8  460.29  4986.3  461.09    5005  461.82
  5016.9  461.75  5032.1  462.63  5046.9  464.54  5086.5  465.16  5112.5  466.09
  5148.3  466.69  5327.5  467.47  5357.2  468.19    5414  468.64  5442.6  469.66
#Mann= 5 ,-1 , 0
  4676.8      .1       0  4973.8     .07       0  4986.3      .1       0
  5016.9     .07       0  5086.5      .1       0
Bank Sta=4973.8,4986.3
XS Rating Curve= 0 ,0
Exp/Cntr=0.3,0.1

Type RM Length L Ch R = 1 ,6349    ,428,428,428
BEGIN DESCRIPTION:
UNT 022 in RCW 8.0
END DESCRIPTION:
XS GIS Cut Line= 3
      1994212.74     13461895.43        1993775.       13461875.
      1993372.86     13461771.73
#Sta/Elev= 30
  4577.6  468.28  4595.4  468.78  4765.5  467.25  4805.6  465.59  4899.6  463.14
  4945.7  460.68  4975.8  459.73  4979.5  459.13    4980  458.33  4991.5  458.33
    4992  459.13  5005.8  459.79  5043.7  460.46  5079.5  461.69  5098.4  462.79
  5108.7  463.91  5120.3  463.98  5155.9  466.17    5181  467.16  5196.6   467.4
  5201.8  467.08  5253.3  468.97    5273  468.79  5278.1   467.9  5284.3  467.74
  5294.6  468.61  5318.9  468.42  5325.6     469  5348.5  467.95    5431  467.72
#Mann= 6 ,-1 , 0
  4577.6      .1       0  4899.6     .07       0  4979.5     .07       0
    4992     .07       0  5043.7      .1       0  5348.5     .05       0
Bank Sta=4979.5,4992
XS Rating Curve= 0 ,0
Exp/Cntr=0.3,0.1

Type RM Length L Ch R = 1 ,5921    ,707,707,707
BEGIN DESCRIPTION:
UNT 022 in RCW 7.0
END DESCRIPTION:
XS GIS Cut Line= 3
      1994310.78     13461749.15      1993828.63     13461437.54
      1993162.36     13461499.17
#Sta/Elev= 30
  4555.5  470.13  4598.1  470.09  4627.7   468.8  4642.9  468.68  4648.9  467.97
  4679.2  467.79  4751.8  465.66  4757.7  465.91  4772.9  464.22    4794  463.21
  4893.8  460.34  4960.2  458.92  4975.4  457.61  4981.4  457.97  4984.3  456.96
  4984.8  456.16  4996.3  456.16  4996.8  456.96  5026.7  457.98  5032.8  458.63
  5085.5  459.12  5105.4  459.75  5152.3   459.8  5266.9  461.71  5364.2  462.65
  5391.3  463.53  5534.9  466.23  5665.5  467.33  5699.9  466.56  5798.7  467.18
#Mann= 6 ,-1 , 0
  4555.5      .1       0  4893.8     .07       0  4984.3     .07       0
  4996.8     .07       0  5085.5      .1       0  5391.3     .05       0
Bank Sta=4984.3,4996.8
XS Rating Curve= 0 ,0
Exp/Cntr=0.3,0.1

Type RM Length L Ch R = 1 ,5214    ,637,637,637
BEGIN DESCRIPTION:
UNT 022 in RCW 6.0
END DESCRIPTION:
XS GIS Cut Line= 3
       1994808.2     13461533.01      1994512.22      13461164.1
      1994098.13     13460329.67
#Sta/Elev= 30
  4623.9   465.1    4738  465.21  4760.4  463.67    4802  462.61    4810  461.81
  4830.8  462.08  4859.6  459.78    4866  460.28  4909.2  458.34  4952.4  455.61
  4992.7  454.16  4995.2  453.36  5008.9  453.36  5011.4  454.16  5016.4  455.02
  5022.9  455.32  5058.1     456  5093.1  457.66  5140.5  458.74  5168.9  460.21
  5331.4  464.52  5348.2  464.26  5386.1  465.39    5421   464.4  5460.2  464.11
  5622.7  464.07  5743.4  466.94  5757.2  466.86  5869.2   469.2  6028.4  470.68
#Mann= 3 ,-1 , 0
  4623.9      .1       0  4992.7     .07       0  5011.4      .1       0
Bank Sta=4992.7,5011.4
XS Rating Curve= 0 ,0
Exp/Cntr=0.3,0.1