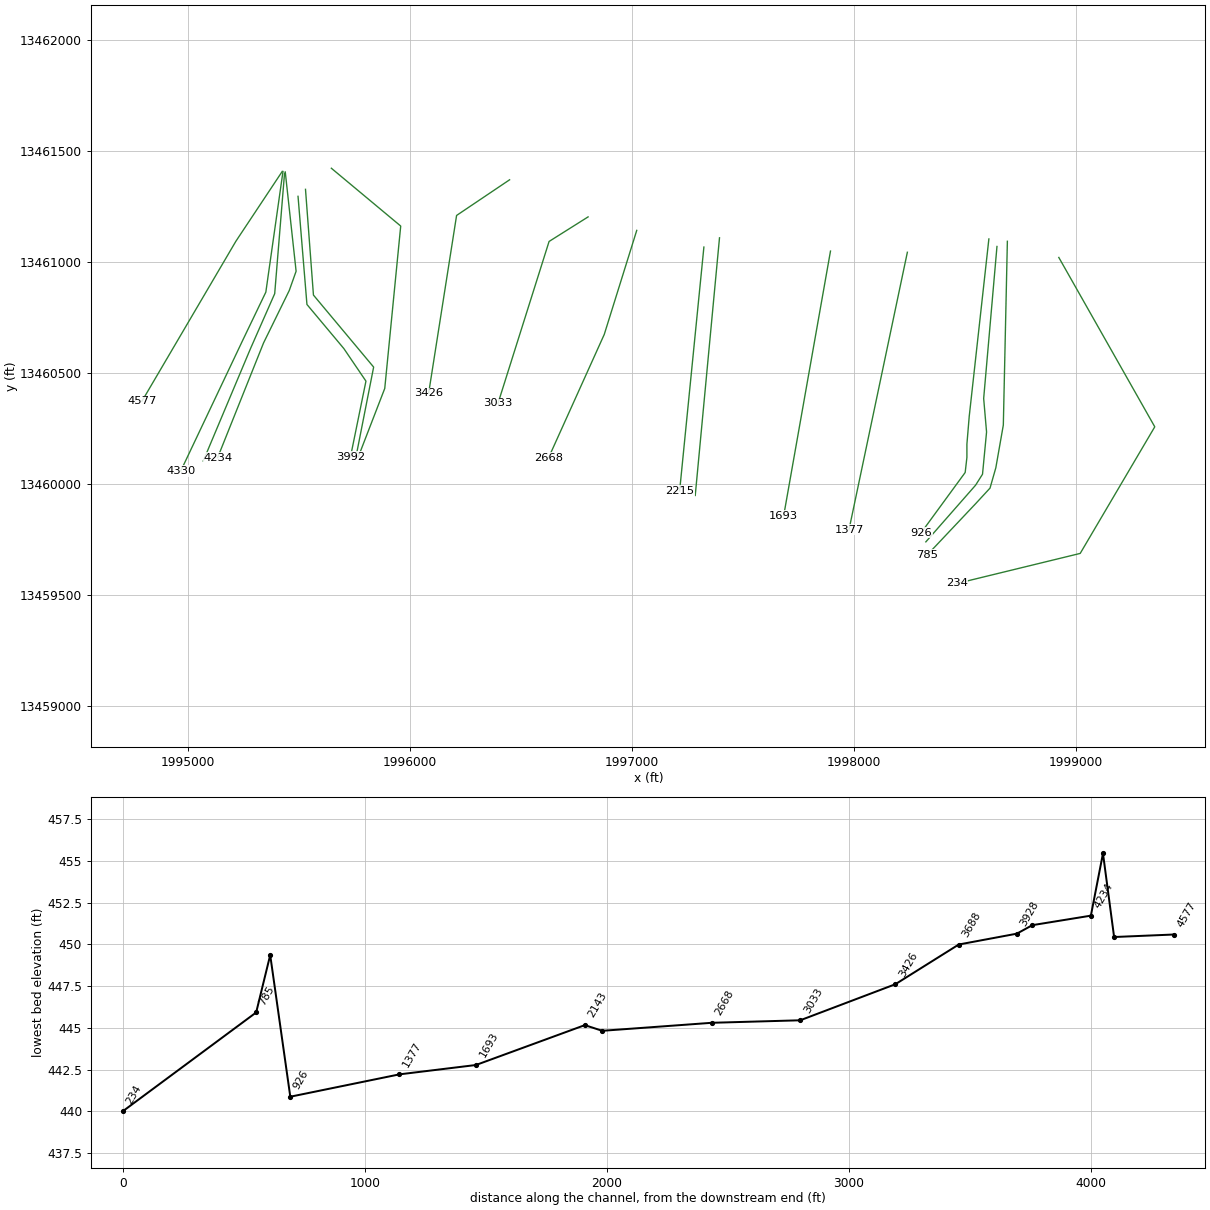
HEC-RAS study UNT 022 in RCW.prj: UNT 022 in RCW Base Level Engineering

--- UNT 022 in RCW.g01 (geometry) --- (continued)

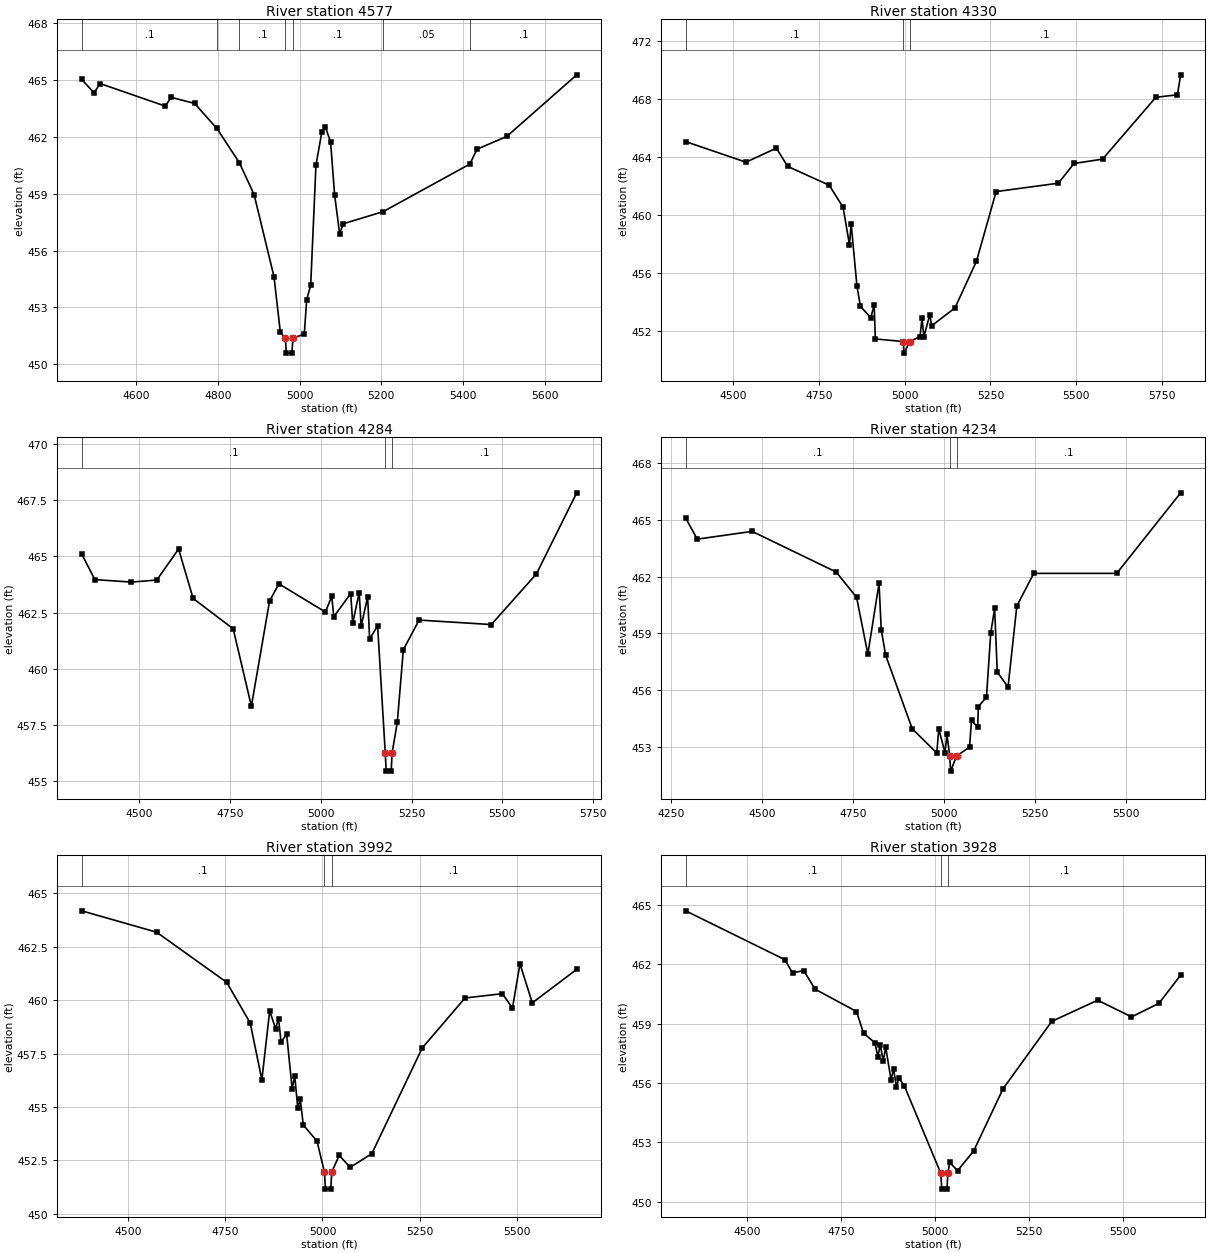
Type RM Length L Ch R = 1 ,4577    ,247,247,247
BEGIN DESCRIPTION:
UNT 022 in RCW 5.0
END DESCRIPTION:
XS GIS Cut Line= 3
      1995424.07     13461409.07      1995215.35     13461094.65
      1994792.15     13460374.13
#Sta/Elev= 30
  4465.7  465.04  4495.9  464.33  4510.9  464.82  4670.3  463.63  4685.3  464.09
  4742.5  463.77  4796.9  462.45  4851.9  460.65  4888.2  458.96  4936.9  454.63
  4952.6  451.68  4964.7  451.39  4967.2  450.59  4980.9  450.59  4983.4  451.39
  5011.2  451.59    5017   453.4  5026.9  454.18  5039.8  460.52  5054.2  462.26
    5063  462.52  5075.6  461.74  5085.5  458.94  5097.8   456.9    5107  457.42
  5204.6  458.06  5416.9  460.57  5434.2  461.35  5507.4  462.03  5678.7  465.28
#Mann= 7 ,-1 , 0
  4465.7      .1       0  4796.9     .05       0  4851.9      .1       0
  4964.7     .07       0  4983.4      .1       0  5204.6     .05       0
  5416.9      .1       0
Bank Sta=4964.7,4983.4
XS Rating Curve= 0 ,0
Exp/Cntr=0.3,0.1

Type RM Length L Ch R = 1 ,4330    ,46,46,46
BEGIN DESCRIPTION:
Mapping XS 05b61c3f
END DESCRIPTION:
XS GIS Cut Line= 4
      1995427.57     13461409.08      1995350.33     13460865.49
      1995246.16     13460648.47      1994966.89     13460059.39
#Sta/Elev= 30
  4362.3  465.04  4538.1  463.62  4626.7  464.59  4659.3  463.33  4780.5  462.03
  4820.9  460.51  4839.4  457.93  4844.4  459.36  4861.3  455.05  4871.4  453.67
  4901.7  452.88  4911.4  453.78  4914.8  451.42    4996  451.24  4998.5  450.44
  5014.8  451.24    5045  451.58  5050.7  452.85  5056.2  451.58  5073.3  453.08
  5078.9  452.33  5146.8  453.56  5209.4  456.79  5266.6  461.59  5447.9  462.17
  5493.4  463.53  5576.5  463.83  5731.8   468.1  5794.5  468.27    5804  469.65
#Mann= 3 ,-1 , 0
  4362.3      .1       0    4996     .07       0  5014.8      .1       0
Bank Sta=4996,5014.8
XS Rating Curve= 0 ,0
Exp/Cntr=0.3,0.1

Type RM Length L Ch R = 1 ,4284    ,50,50,50
BEGIN DESCRIPTION:
Mapping XS 9b349621
END DESCRIPTION:
XS GIS Cut Line= 4
      1995434.62     13461401.29      1995390.26     13460858.54
      1995280.89     13460610.28       1995068.2     13460104.42
#Sta/Elev= 30
  4340.7  465.11  4377.1  463.97  4477.4  463.86  4547.7  463.95  4607.9  465.33
    4648  463.13  4758.4  461.78  4808.5  458.34  4858.7  463.02  4884.5  463.78
  5012.4  462.53  5030.2  463.22  5035.7  462.32  5082.3  463.35  5087.8  462.03
  5105.7  463.39  5111.1   461.9    5129   463.2  5134.5  461.33  5156.5  461.91
  5177.6  456.25  5180.1  455.45  5193.9  455.45  5196.4  456.25  5210.8  457.63
  5227.4  460.85  5270.8  462.17  5469.9  461.97  5594.1  464.22  5705.3  467.83
#Mann= 3 ,-1 , 0
  4340.7      .1       0  5177.6     .07       0  5196.4      .1       0
Bank Sta=5177.6,5196.4
XS Rating Curve= 0 ,0
Exp/Cntr=0.3,0.1

Type RM Length L Ch R = 1 ,4234    ,242,242,242
BEGIN DESCRIPTION:
Mapping XS 5d67809b
END DESCRIPTION:
XS GIS Cut Line= 5
      1995437.88     13461406.75      1995486.71     13460959.67
        1995456.      13460873.1      1995339.91     13460636.32
      1995133.29     13460120.03
#Sta/Elev= 30
  4289.7  465.11  4321.6  463.99  4472.5   464.4  4703.9  462.25  4759.9  460.91
  4790.8  457.91  4821.6  461.65  4827.6  459.21  4839.8  457.85  4912.9  453.96
  4980.4  452.68  4985.9  453.95  5002.9   452.7  5008.4  453.66    5016  452.52
  5018.5  451.72  5034.8  452.52  5070.4  452.99  5075.9   454.4  5092.8  454.05
  5094.9  455.13  5117.1  455.64  5128.7     459  5139.5  460.34  5146.7  456.96
  5176.4  456.17  5200.6  460.46  5247.2  462.18  5475.2  462.18  5651.1  466.44
#Mann= 3 ,-1 , 0
  4289.7      .1       0    5016     .07       0  5034.8      .1       0
Bank Sta=5016,5034.8
XS Rating Curve= 0 ,0
Exp/Cntr=0.3,0.1

Type RM Length L Ch R = 1 ,3992    ,64,64,64
BEGIN DESCRIPTION:
Mapping XS d1af84c5
END DESCRIPTION:
XS GIS Cut Line= 5
      1995495.39     13461297.12      1995535.53     13460809.93
      1995701.89     13460611.15      1995801.36     13460464.62
      1995731.62     13460123.02
#Sta/Elev= 30
  4380.4  464.18  4573.2  463.18  4753.8  460.83    4814  458.93  4844.1  456.27
  4864.2   459.5  4879.2  458.67    4887  459.12  4893.5  458.04  4907.8   458.4
  4922.1  455.84  4928.6  456.46  4936.4  454.96    4943  455.35  4950.7  454.15
  4985.9   453.4  5005.1  451.95  5007.6  451.15  5021.4  451.15  5023.9  451.95
  5043.1  452.73  5071.3  452.17    5127  452.81  5256.7  457.76  5366.9   460.1
  5462.8   460.3  5488.9  459.63  5508.2   461.7  5539.9  459.87  5654.2  461.44
#Mann= 3 ,-1 , 0
  4380.4      .1       0  5005.1     .07       0  5023.9      .1       0
Bank Sta=5005.1,5023.9
XS Rating Curve= 0 ,0
Exp/Cntr=0.3,0.1

Type RM Length L Ch R = 1 ,3928    ,240,240,240
BEGIN DESCRIPTION:
Mapping XS 477b7028
END DESCRIPTION:
XS GIS Cut Line= 4
      1995529.02      13461328.6      1995564.83     13460852.25
      1995836.01     13460527.81      1995755.39     13460118.21
#Sta/Elev= 30
  4336.6  464.71  4600.9  462.24  4621.2  461.57  4651.1  461.69  4681.2  460.75
  4791.5  459.62  4810.4  458.52  4840.6  458.04  4848.4  457.34  4854.9  457.95
  4862.7   457.1  4869.2  457.82  4883.6  456.16  4890.1  456.72  4897.9  455.81
  4904.4  456.26  4918.7  455.87    5016  451.44  5018.5  450.64  5032.3  450.64
  5034.8  451.44  5039.7  451.99  5060.5  451.57  5103.5  452.57  5181.6  455.71
  5311.3  459.12  5433.6  460.19  5523.7  459.35  5596.7  460.03  5654.6  461.46
#Mann= 3 ,-1 , 0
  4336.6      .1       0    5016     .07       0  5034.8      .1       0
Bank Sta=5016,5034.8
XS Rating Curve= 0 ,0
Exp/Cntr=0.3,0.1

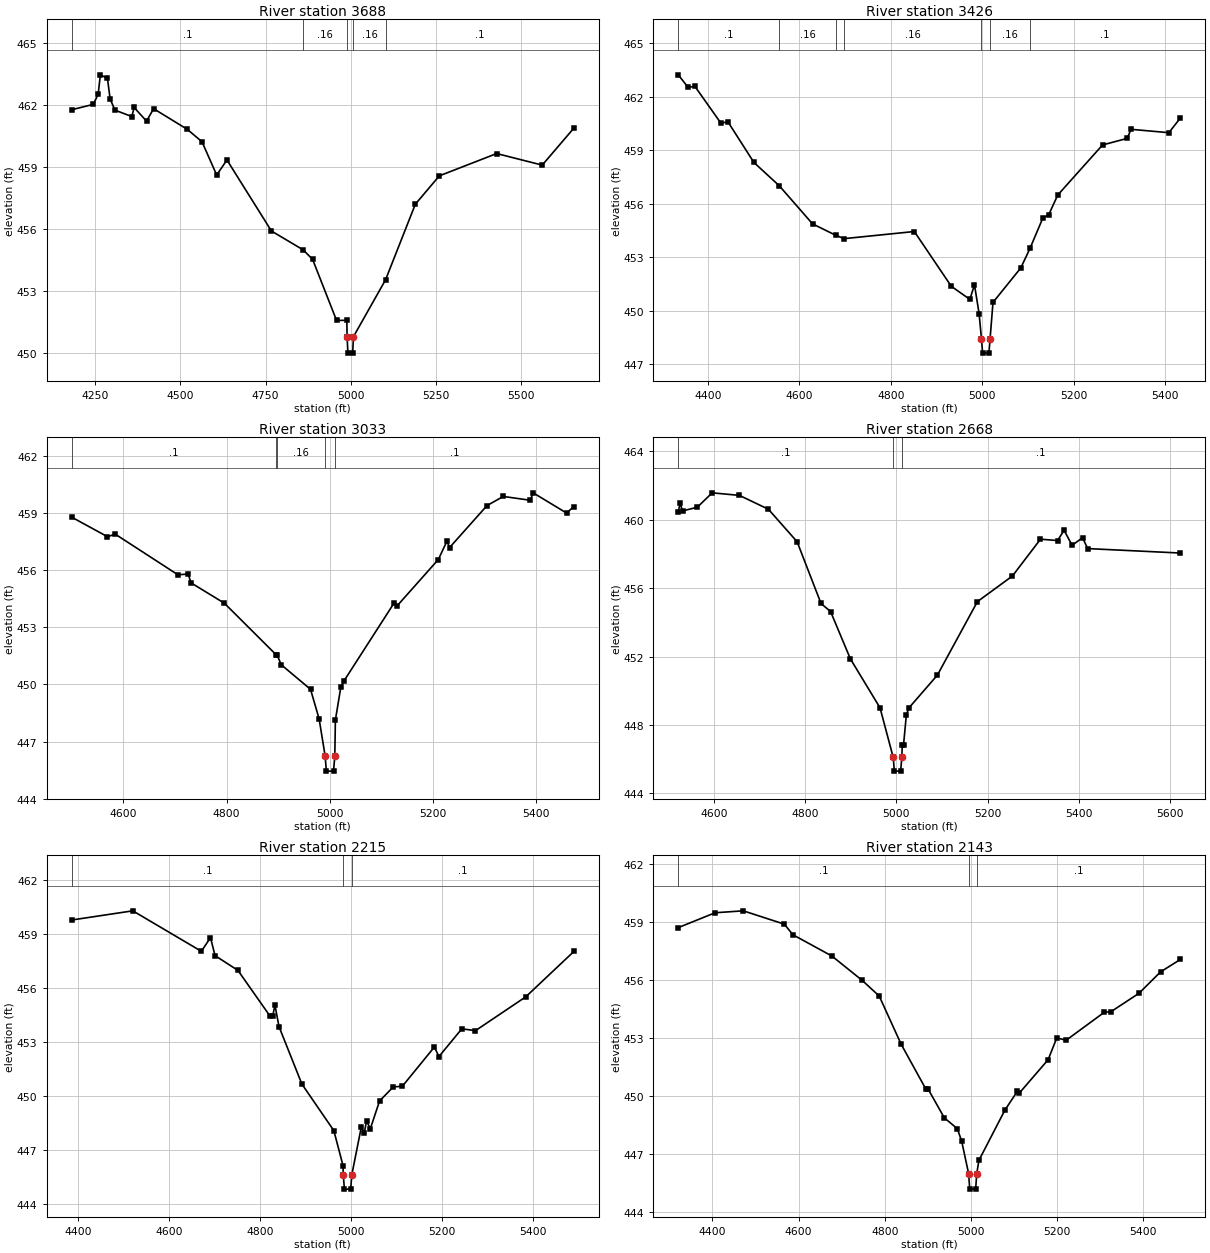
Type RM Length L Ch R = 1 ,3688    ,262,262,262
BEGIN DESCRIPTION:
Mapping XS c0494438
END DESCRIPTION:
XS GIS Cut Line= 4
      1995645.48     13461423.64      1995957.97     13461163.23
      1995886.08     13460431.61      1995766.77     13460122.98
#Sta/Elev= 30
  4181.2  461.77  4244.3  462.03  4258.6  462.52  4265.1  463.46  4285.9  463.29
  4293.7  462.29    4308  461.75  4357.5  461.44    4364  461.88  4400.5  461.22
  4421.3  461.82  4520.2  460.82  4563.2  460.22  4606.3  458.61  4636.4  459.34
  4766.9   455.9  4859.8  454.99  4887.6  454.53    4958  451.57  4988.1  451.58
  4988.8  450.79  4991.3  449.99  5005.1  449.99  5007.6  450.79  5101.7  453.54
  5189.1   457.2  5259.4  458.57  5427.6  459.65  5561.3  459.09    5654  460.88
#Mann= 5 ,-1 , 0
  4181.2      .1       0  4859.8     .16       0  4988.8     .07       0
  5007.6     .16       0  5101.7      .1       0
Bank Sta=4988.8,5007.6
XS Rating Curve= 0 ,0
Exp/Cntr=0.3,0.1

Type RM Length L Ch R = 1 ,3426    ,393,393,393
BEGIN DESCRIPTION:
Mapping XS 81fa2bcc
END DESCRIPTION:
XS GIS Cut Line= 3
      1996448.46     13461371.59      1996209.71     13461210.97
      1996083.83     13460410.16
#Sta/Elev= 30
  4334.9  463.24  4356.4  462.54  4371.4  462.59  4428.4  460.52  4443.4  460.61
  4500.4  458.32  4555.9  457.01  4628.7  454.87  4679.4  454.23  4697.9  454.04
  4851.4  454.44  4932.4  451.36  4972.9  450.63    4983  451.45  4993.1  449.83
  4998.3  448.41  5000.8  447.61  5014.6  447.61  5017.1  448.41  5023.5  450.46
  5084.2  452.39  5104.6   453.5  5132.9  455.22    5145  455.36  5165.2  456.49
  5263.1   459.3    5317  459.67  5325.6  460.18  5408.2  459.99  5433.3  460.81
#Mann= 7 ,-1 , 0
  4334.9      .1       0  4555.9     .16       0  4679.4      .1       0
  4697.9     .16       0  4998.3     .07       0  5017.1     .16       0
  5104.6      .1       0
Bank Sta=4998.3,5017.1
XS Rating Curve= 0 ,0
Exp/Cntr=0.3,0.1

Type RM Length L Ch R = 1 ,3033    ,365,365,365
BEGIN DESCRIPTION:
Mapping XS 9ccea97e
END DESCRIPTION:
XS GIS Cut Line= 3
      1996802.14     13461204.46      1996626.37     13461093.79
      1996396.34     13460364.62
#Sta/Elev= 30
  4500.2  458.77  4569.3  457.75  4584.5  457.88  4705.8  455.75  4725.7  455.79
    4731  455.33  4795.7  454.26  4896.1  451.55  4897.5  451.56  4905.9  451.03
  4962.6  449.74  4979.3  448.18  4990.8  446.25  4993.3  445.45  5007.1  445.45
  5009.6  446.25  5010.7  448.13  5021.2  449.85  5027.3  450.18  5124.4  454.27
  5129.6   454.1    5210  456.55  5226.7  457.51  5231.9  457.18  5304.3  459.38
  5335.8  459.86  5388.2  459.66  5393.7  460.05  5458.4  458.99  5472.5  459.33
#Mann= 5 ,-1 , 0
  4500.2      .1       0  4896.1     .07       0  4897.5     .16       0
  4990.8     .07       0  5009.6      .1       0
Bank Sta=4990.8,5009.6
XS Rating Curve= 0 ,0
Exp/Cntr=0.3,0.1

Type RM Length L Ch R = 1 ,2668    ,453,453,453
BEGIN DESCRIPTION:
UNT 022 in RCW 2.0
END DESCRIPTION:
XS GIS Cut Line= 3
      1997021.33     13461143.67        1996875.       13460675.
      1996624.35     13460119.73
#Sta/Elev= 30
  4521.9  460.44    4526  460.97  4531.3  460.51  4563.8  460.73  4596.3  461.57
    4656  461.42  4719.5  460.61  4782.4  458.71  4834.8   455.1  4855.7  454.63
  4899.2  451.86  4964.1     449    4993   446.1  4995.5   445.3  5009.3   445.3
  5011.8   446.1  5012.9  446.83  5015.6  446.83  5021.7  448.57  5027.2  448.99
  5089.7  450.91  5177.5  455.21  5254.3  456.71  5315.7  458.86    5353  458.78
  5367.4  459.38    5385   458.5  5407.9  458.95  5419.1  458.31  5622.1  458.05
#Mann= 3 ,-1 , 0
  4521.9      .1       0    4993     .07       0  5011.8      .1       0
Bank Sta=4993,5011.8
XS Rating Curve= 0 ,0
Exp/Cntr=0.3,0.1

Type RM Length L Ch R = 1 ,2215    ,72,72,72
BEGIN DESCRIPTION:
Mapping XS 28ea642e
END DESCRIPTION:
XS GIS Cut Line= 2
      1997323.85     13461068.56      1997214.49     13459969.79
#Sta/Elev= 30
  4386.5  459.78  4520.7  460.29  4671.5  458.04  4691.6   458.8  4701.6   457.8
  4751.9  456.98  4822.2  454.45  4828.2  454.42  4833.3  455.05  4842.3  453.85
  4892.6  450.66  4962.9  448.07    4983  446.13  4983.6  445.62  4986.1  444.82
  4999.9  444.82  5002.4  445.62  5023.2  448.26  5029.7  447.94  5034.7  448.59
  5043.3  448.19  5063.4  449.72  5093.5   450.5  5113.6  450.54    5184  452.72
    5194  452.19  5244.3  453.73  5274.4  453.63    5385  455.51  5490.7  458.03
#Mann= 3 ,-1 , 0
  4386.5      .1       0  4983.6     .07       0  5002.4      .1       0
Bank Sta=4983.6,5002.4
XS Rating Curve= 0 ,0
Exp/Cntr=0.3,0.1

Type RM Length L Ch R = 1 ,2143    ,450,450,450
BEGIN DESCRIPTION:
Mapping XS a532ba0d
END DESCRIPTION:
XS GIS Cut Line= 2
      1997394.17     13461110.26      1997284.85      13459949.4
#Sta/Elev= 30
  4320.5   458.7  4406.1  459.47  4471.5  459.57  4566.8  458.88  4586.9  458.33
  4677.3  457.23  4747.6  455.97  4787.2  455.16    4838  452.67  4895.8  450.33
  4900.8  450.34  4938.5  448.85  4968.6  448.29  4978.7  447.65  4994.9  445.96
  4997.4  445.16  5011.2  445.16  5013.7  445.96  5018.8  446.65  5079.1  449.25
  5107.9  450.22  5112.9  450.14  5179.5  451.86  5199.6  452.99  5221.5  452.87
  5310.1  454.32    5325  454.34  5390.5   455.3  5440.7  456.41  5486.5  457.05
#Mann= 3 ,-1 , 0
  4320.5      .1       0  4994.9     .07       0  5013.7      .1       0
Bank Sta=4994.9,5013.7
XS Rating Curve= 0 ,0
Exp/Cntr=0.3,0.1

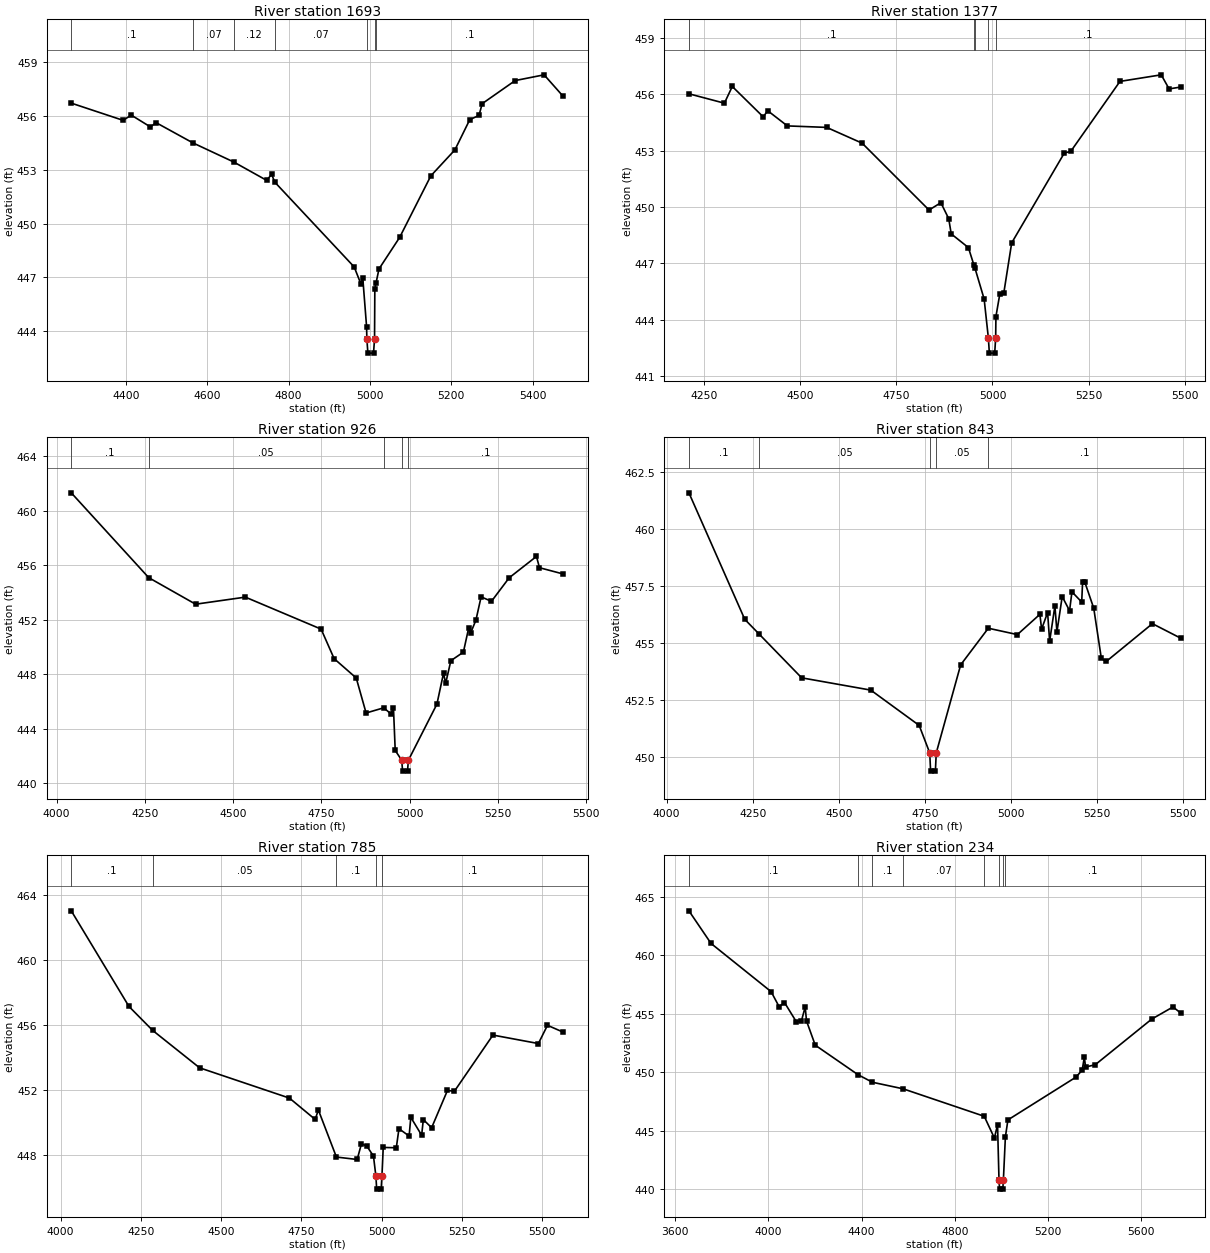
Type RM Length L Ch R = 1 ,1693    ,316,316,316
BEGIN DESCRIPTION:
Mapping XS e814d0fd
END DESCRIPTION:
XS GIS Cut Line= 2
      1997894.18     13461050.43      1997683.43     13459858.82
#Sta/Elev= 30
  4265.2  456.73  4392.6  455.77  4412.9  456.06    4460   455.4  4473.8  455.64
  4564.4  454.51  4665.1  453.44  4745.7  452.42  4758.2  452.75  4765.8  452.32
  4961.3  447.58  4977.4  446.65  4982.4  446.95  4991.7  444.25  4992.4  443.57
  4994.9  442.77  5008.8  442.77  5011.3  443.57    5012  446.37    5015  446.69
  5022.2  447.47    5073  449.23  5149.8  452.67    5209  454.12  5245.6  455.81
  5268.2  456.04  5276.1   456.7  5357.3  457.99  5428.4  458.31  5475.3  457.11
#Mann= 7 ,-1 , 0
  4265.2      .1       0  4564.4     .07       0  4665.1     .12       0
  4765.8     .07       0  4992.4     .07       0  5011.3     .07       0
    5015      .1       0
Bank Sta=4992.4,5011.3
XS Rating Curve= 0 ,0
Exp/Cntr=0.3,0.1

Type RM Length L Ch R = 1 ,1377    ,451,451,451
BEGIN DESCRIPTION:
Mapping XS 67b999d7
END DESCRIPTION:
XS GIS Cut Line= 2
      1998240.52     13461045.14      1997977.51     13459795.21
#Sta/Elev= 30
  4211.8  456.02  4303.9  455.52  4324.4  456.41  4404.8  454.79  4416.3  455.12
  4467.4  454.31  4569.6  454.23  4661.6  453.39  4835.3  449.83    4866  450.22
  4886.4  449.37  4892.9  448.56  4937.5  447.83    4952  446.89  4954.5  446.74
  4978.4  445.09  4989.4  443.01  4991.9  442.21  5005.8  442.21  5008.3  443.01
    5009  444.16  5019.2  445.37  5029.5  445.42  5049.9  448.08  5186.7  452.87
  5203.2  452.95  5331.1  456.68  5438.2  457.03  5458.7  456.28  5489.1  456.38
#Mann= 5 ,-1 , 0
  4211.8      .1       0    4952     .12       0  4954.5      .1       0
  4989.4     .07       0  5008.3      .1       0
Bank Sta=4989.4,5008.3
XS Rating Curve= 0 ,0
Exp/Cntr=0.3,0.1

Type RM Length L Ch R = 1 ,926     ,83,83,83
BEGIN DESCRIPTION:
Mapping XS 21d5001b
END DESCRIPTION:
XS GIS Cut Line= 6
      1998607.71      13461105.1      1998519.17     13460305.59
      1998508.75     13460180.59      1998508.75      13460120.7
      1998500.94     13460052.99      1998303.04     13459782.17
#Sta/Elev= 30
  4041.6  461.31    4261  455.08  4393.8  453.13  4534.7  453.65  4749.3   451.3
  4786.2  449.13  4848.8  447.71  4876.7  445.14  4926.6  445.52  4946.9  445.08
  4954.2  445.53  4959.2  442.39  4977.6  441.67  4980.1  440.87    4994  440.87
  4996.5  441.67  5077.3  445.79    5096  448.06  5102.1  447.32  5116.8  448.98
  5152.3  449.61    5167  451.35  5173.2  451.04  5187.8  451.96  5202.5  453.67
  5231.8  453.34    5282  455.07  5359.3  456.64  5367.8  455.81  5434.9  455.35
#Mann= 5 ,-1 , 0
  4041.6      .1       0    4261     .05       0  4926.6      .1       0
  4977.6     .07       0  4996.5      .1       0
Bank Sta=4977.6,4996.5
XS Rating Curve= 0 ,0
Exp/Cntr=0.3,0.1

Type RM Length L Ch R = 1 ,843     ,58,58,58
BEGIN DESCRIPTION:
Mapping XS 48551b96
END DESCRIPTION:
XS GIS Cut Line= 6
      1998644.17     13461071.19      1998584.27     13460386.32
      1998597.29     13460235.28      1998579.06     13460045.17
      1998547.81      13459995.7      1998323.83     13459740.46
#Sta/Elev= 30
  4064.7  461.59  4226.9  456.03  4268.8  455.38  4392.1  453.46  4592.9  452.92
  4733.4  451.37  4764.1  450.16  4766.6  449.36  4780.5  449.36    4783  450.16
  4853.9  454.03  4934.2  455.64  5018.6  455.36    5084  456.25    5089   455.6
  5106.4  456.33  5112.3  455.07  5127.6  456.62  5133.5  455.48  5148.8  457.03
  5170.2  456.41  5177.1  457.24  5205.4  456.79    5208  457.65  5214.8  457.65
  5240.4  456.52  5262.5  454.31  5276.8  454.18  5410.8  455.84  5493.3   455.2
#Mann= 5 ,-1 , 0
  4064.7      .1       0  4268.8     .05       0  4764.1     .07       0
    4783     .05       0  4934.2      .1       0
Bank Sta=4764.1,4783
XS Rating Curve= 0 ,0
Exp/Cntr=0.3,0.1

Type RM Length L Ch R = 1 ,785     ,551,551,551
BEGIN DESCRIPTION:
Mapping XS 16dcae60
END DESCRIPTION:
XS GIS Cut Line= 6
      1998691.04     13461094.68      1998672.81     13460266.53
      1998638.96     13460073.82      1998612.92     13459982.67
      1998550.42     13459914.97      1998329.56     13459681.12
#Sta/Elev= 30
  4033.3  463.01    4213  457.14  4286.7  455.67  4433.1  453.37  4713.1  451.51
  4793.2   450.2  4803.2  450.78  4859.4  447.89  4924.1  447.74  4937.5  448.71
  4954.6  448.55  4974.9  447.95  4982.4  446.72  4984.9  445.92  4998.8  445.92
  5001.3  446.72  5005.3  448.48    5046  448.46  5054.3  449.63    5086  449.18
  5091.2  450.33    5125  449.23  5130.2  450.19  5156.1  449.69  5205.4  451.98
    5227  451.93  5347.1  455.38  5488.7  454.86    5517  455.98  5565.9  455.56
#Mann= 5 ,-1 , 0
  4033.3      .1       0  4286.7     .05       0  4859.4      .1       0
  4982.4     .07       0  5001.3      .1       0
Bank Sta=4982.4,5001.3
XS Rating Curve= 0 ,0
Exp/Cntr=0.3,0.1

Type RM Length L Ch R = 1 ,234     ,0,0,0
BEGIN DESCRIPTION:
UNT 022 in RCW 1.0
END DESCRIPTION:
XS GIS Cut Line= 4
      1998922.79     13461021.77      1999355.11     13460258.72
      1999019.17      13459688.4      1998463.64     13459552.99
#Sta/Elev= 30
  3659.3   463.8  3754.2  461.01  4011.9  456.89  4046.4   455.6  4069.3  455.96
  4120.6   454.3  4142.3   454.4  4158.2  455.58  4163.9  454.38  4201.4  452.31
  4385.3  449.78  4446.7  449.14  4578.1  448.58  4926.5  446.23    4970  444.37
  4983.6   445.5  4989.8   440.8  4992.3     440  5006.2     440  5008.7   440.8
  5017.2  444.46  5028.1  445.92  5319.5  449.57  5346.6  450.17  5356.1  451.29
  5361.2  450.44  5402.9  450.64  5645.1  454.54  5736.5  455.58    5770  455.05
#Mann= 8 ,-1 , 0
  3659.3      .1       0  4385.3     .07       0  4446.7      .1       0
  4578.1     .07       0  4926.5     .12       0  4989.8     .07       0
  5008.7     .12       0  5017.2      .1       0
Bank Sta=4989.8,5008.7
XS Rating Curve= 0 ,0
Exp/Cntr=0.3,0.1
LCMann Table=0

Chan Stop Cuts=-1
Use User Specified Reach Order=0
Composite Channel Slope=5