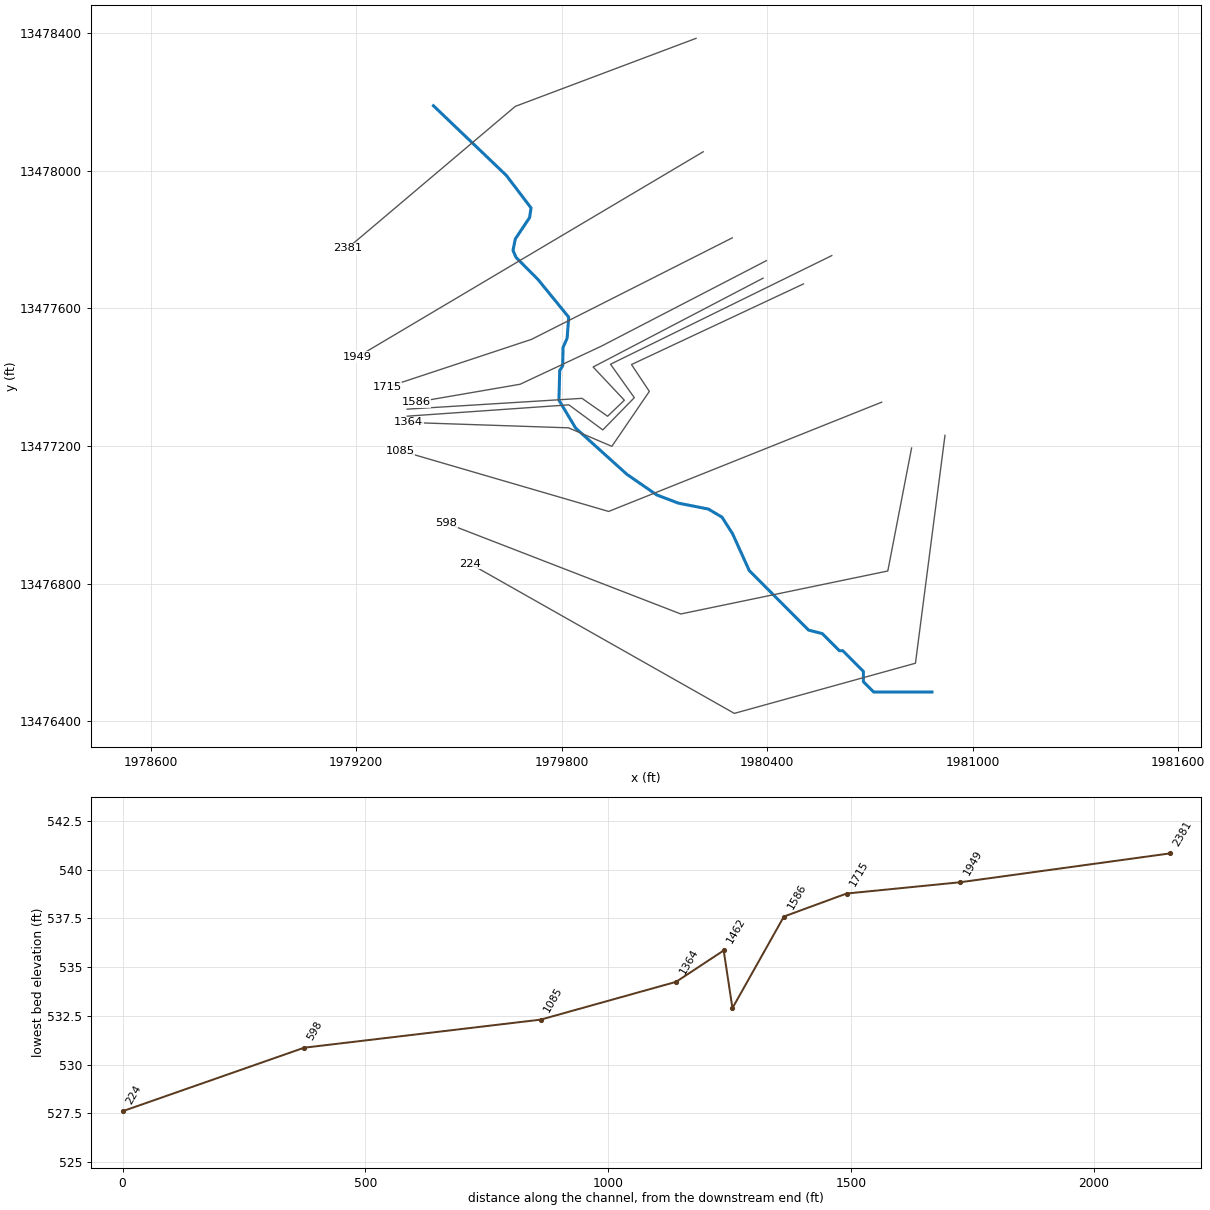
--- UNT 023 in RCW.prj (project) ---

Proj Title=UNT 023 in RCW Base Level Engineering
Current Plan=p01
Default Exp/Contr=0.3,0.1
English Units
Geom File=g01
Flow File=f01
Plan File=p01
BEGIN DESCRIPTION:
UNT 023 in RCW
END DESCRIPTION:

--- UNT 023 in RCW.p01 (plan) ---

Plan Title=Multiple Run
Short Identifier=Multiple
Geom File=g01
Flow File=f01
Subcritical Flow
K Sum by GR= 0
Std Step Tol= 0.01
Critical Tol= 0.01
Num of Std Step Trials= 20
Max Error Tol= 0.3
Flow Tol Ratio= 0.001
Split Flow NTrial= 30
Split Flow Tol= 0.02
Split Flow Ratio= 0.02
Log Output Level= 0
Friction Slope Method= 1
Unsteady Friction Slope Method= 2
Unsteady Bridges Friction Slope Method= 1
Parabolic Critical Depth
Global Vel Dist=  1 , 1 , 1
Global Log Level= 0
CheckData=True
Encroach Param= -1, 0, 0, 0
BEGIN DESCRIPTION:
Multiple Run
END DESCRIPTION:

--- UNT 023 in RCW.f01 (steady flow) ---

Flow Title=Multiple
Number of Profiles=7
Profile Names=10-year,25-year,50-year,1pct_min,100-year,1pct_plu,500-year
River Rch & RM= UNT 023 in RCW,Reach-1,2381
     201     278     342     210     419     836     638
Boundary for River Rch & Prof#=UNT 023 in RCW,Reach-1,1
Up Type=0
Dn Type=3
Dn Slope=0.005
Boundary for River Rch & Prof#=UNT 023 in RCW,Reach-1,2
Up Type=0
Dn Type=3
Dn Slope=0.005
Boundary for River Rch & Prof#=UNT 023 in RCW,Reach-1,3
Up Type=0
Dn Type=3
Dn Slope=0.005
Boundary for River Rch & Prof#=UNT 023 in RCW,Reach-1,4
Up Type=0
Dn Type=3
Dn Slope=0.005
Boundary for River Rch & Prof#=UNT 023 in RCW,Reach-1,5
Up Type=0
Dn Type=3
Dn Slope=0.005
Boundary for River Rch & Prof#=UNT 023 in RCW,Reach-1,6
Up Type=0
Dn Type=3
Dn Slope=0.005
Boundary for River Rch & Prof#=UNT 023 in RCW,Reach-1,7
Up Type=0
Dn Type=3
Dn Slope=0.005

--- UNT 023 in RCW.g01 (geometry) ---

Geom Title=Existing Conditions

River Reach=UNT 023 in RCW,Reach-1
Reach XY= 30
      1979425.80     13478189.54      1979638.26     13477987.24
      1979710.66     13477892.45      1979706.49     13477864.33
      1979664.83     13477802.35      1979658.05     13477769.01
      1979667.03     13477748.30      1979730.80     13477684.54
      1979820.70     13477574.64      1979816.00     13477513.51
      1979804.06     13477486.39      1979803.07     13477432.98
      1979794.39     13477419.53      1979792.13     13477333.39
      1979840.95     13477252.01      1979990.69     13477117.46
      1980077.50     13477057.78      1980140.43     13477033.91
      1980228.32     13477016.55      1980268.08     13476993.07
      1980298.81     13476945.15      1980347.62     13476837.72
      1980520.80     13476664.54      1980560.80     13476654.54
      1980610.80     13476604.54      1980620.80     13476604.54
      1980680.80     13476544.54      1980680.80     13476514.54
      1980710.80     13476484.54      1980880.80     13476484.54

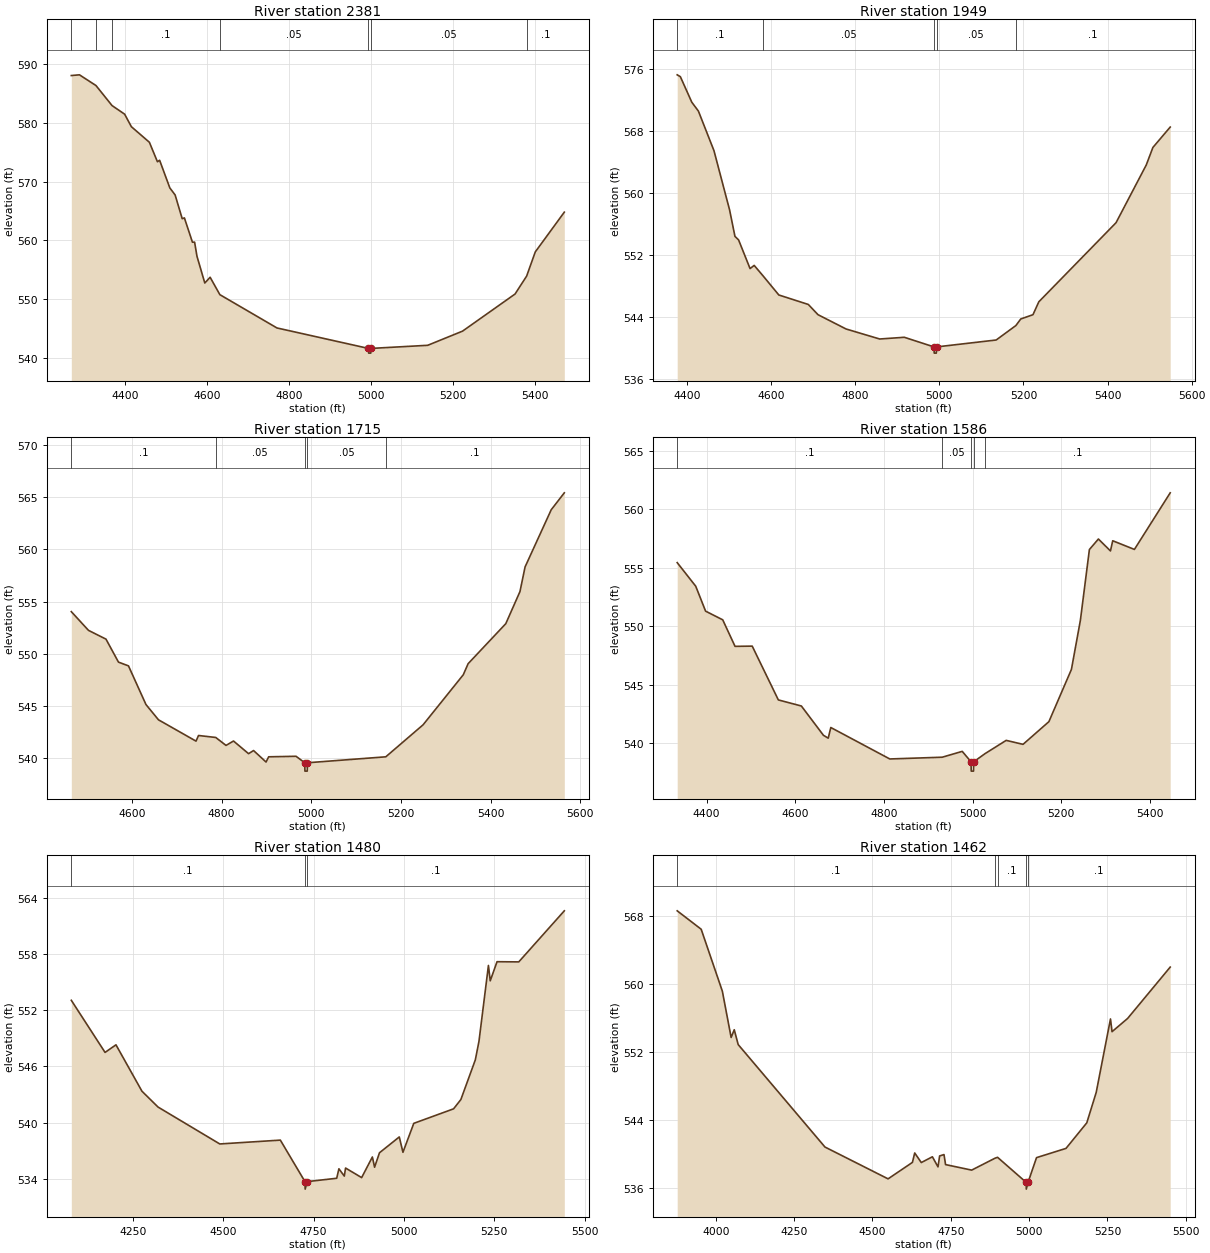
Type RM Length L Ch R = 1,2381,432,432,432
BEGIN DESCRIPTION:
UNT 023 in RCW 3.0
END DESCRIPTION:
XS GIS Cut Line= 3
      1980192.40     13478385.55      1979664.63     13478187.64
      1979174.98     13477774.98
#Sta/Elev= 30
  4268.2  588.04  4288.1  588.16  4328.4  586.34  4367.7  582.93  4398.4  581.47
  4414.9  579.34  4458.9  576.69  4478.5  573.38  4483.9  573.63  4508.8  568.93
  4521.7  567.74  4539.0  563.70  4544.4  563.83  4564.0  559.70  4569.3  559.71
  4575.1  557.31  4594.2  552.76  4607.2  553.74  4631.0  550.78  4770.4  545.12
  4993.9  541.64  4994.4  540.84  4999.4  540.84  4999.9  541.64  5138.6  542.17
  5223.7  544.58  5351.9  550.89  5380.2  553.94  5401.3  558.05  5472.2  564.81
#Mann=7,-1,0
  4268.2     0.1       0  4328.4    0.16       0  4367.7     0.1       0
  4631.0    0.05       0  4993.9    0.03       0  4999.9    0.05       0
  5380.2     0.1       0
Bank Sta=4993.9,4999.9
Exp/Cntr=0.3,0.1

Type RM Length L Ch R = 1,1949,234,234,234
BEGIN DESCRIPTION:
Mapping XS 8ee4c6ea
END DESCRIPTION:
XS GIS Cut Line= 2
      1980213.24     13478055.69      1979204.13     13477459.24
#Sta/Elev= 30
  4376.8  575.21  4384.3  574.97  4411.5  571.68  4427.2  570.54  4464.2  565.44
  4501.3  557.82  4514.1  554.40  4522.8  553.94  4550.0  550.25  4559.8  550.66
  4580.2  549.36  4618.4  546.85  4688.5  545.63  4711.6  544.31  4778.3  542.47
  4858.2  541.18  4916.8  541.40  4987.4  540.16  4987.9  539.36  4992.9  539.36
  4993.4  540.16  5135.2  541.05  5182.0  542.91  5193.7  543.76  5222.7  544.31
  5236.6  545.97  5420.2  556.16  5492.1  563.60  5507.8  565.85  5549.0  568.48
#Mann=5,-1,0
  4376.8     0.1       0  4580.2    0.05       0  4987.4    0.03       0
  4993.4    0.05       0  5182.0     0.1       0
Bank Sta=4987.4,4993.4
Exp/Cntr=0.3,0.1

Type RM Length L Ch R = 1,1715,129,129,129
BEGIN DESCRIPTION:
Mapping XS 0d915eb8
END DESCRIPTION:
XS GIS Cut Line= 3
      1980298.03     13477805.26      1979712.08     13477510.11
      1979291.09     13477371.22
#Sta/Elev= 30
  4465.0  554.04  4503.3  552.25  4542.3  551.41  4570.2  549.21  4592.5  548.85
  4631.5  545.15  4659.4  543.69  4743.1  541.65  4748.7  542.19  4787.1  542.00
  4810.0  541.24  4826.7  541.66  4860.3  540.45  4871.4  540.75  4899.3  539.65
  4905.1  540.15  4966.2  540.20  4985.5  539.58  4986.0  538.78  4991.1  538.78
  4991.6  539.58  5166.3  540.15  5249.4  543.21  5339.1  548.00  5349.9  549.06
  5433.9  552.89  5465.5  555.96  5476.9  558.32  5535.2  563.79  5564.4  565.41
#Mann=5,-1,0
  4465.0     0.1       0  4787.1    0.05       0  4985.5    0.03       0
  4991.6    0.05       0  5166.3     0.1       0
Bank Sta=4985.5,4991.6
Exp/Cntr=0.3,0.1

Type RM Length L Ch R = 1,1586,106,106,106
BEGIN DESCRIPTION:
Mapping XS f70e7267
END DESCRIPTION:
XS GIS Cut Line= 4
      1980397.56     13477738.96      1979915.81     13477490.28
      1979678.83     13477379.60      1979375.47     13477327.52
#Sta/Elev= 30
  4333.9  555.43  4375.7  553.41  4397.9  551.28  4436.5  550.54  4464.3  548.27
  4503.0  548.29  4561.9  543.69  4613.8  543.17  4663.7  540.66  4674.4  540.42
  4680.2  541.33  4813.2  538.64  4931.4  538.79  4976.5  539.29  4996.3  538.40
  4996.8  537.60  5001.9  537.60  5002.4  538.40  5027.7  539.09  5075.6  540.23
  5113.6  539.89  5171.9  541.83  5222.7  546.30  5242.9  550.50  5263.2  556.55
  5283.5  557.45  5310.7  556.43  5315.8  557.30  5364.7  556.56  5445.4  561.40
#Mann=5,-1,0
  4333.9     0.1       0  4931.4    0.05       0  4996.3    0.03       0
  5002.4    0.05       0  5027.7     0.1       0
Bank Sta=4996.3,5002.4
Exp/Cntr=0.3,0.1

Type RM Length L Ch R = 1,1480,18,18,18
BEGIN DESCRIPTION:
Mapping XS a260b8fc
END DESCRIPTION:
XS GIS Cut Line= 6
      1980387.84     13477687.99      1979891.94     13477429.73
      1979983.08     13477333.16      1979934.25     13477286.50
      1979859.38     13477338.58      1979349.20     13477307.17
#Sta/Elev= 30
  4079.4  553.05  4172.8  547.49  4203.0  548.30  4274.9  543.35  4319.4  541.66
  4490.3  537.72  4657.9  538.13  4726.1  533.70  4726.6  532.90  4732.2  533.70
  4813.9  534.06  4820.0  535.07  4834.9  534.29  4838.4  535.15  4882.9  534.13
  4912.6  536.33  4918.7  535.24  4932.3  536.78  4987.1  538.47  4997.2  536.83
  5027.2  539.92  5137.4  541.47  5157.5  542.46  5197.5  546.69  5207.6  548.67
  5233.8  556.77  5238.8  555.13  5257.6  557.17  5317.8  557.15  5443.8  562.60
#Mann=3,-1,0
  4079.4     0.1       0  4726.1    0.07       0  4732.2     0.1       0
Bank Sta=4726.1,4732.2
Exp/Cntr=0.3,0.1

Type RM Length L Ch R = 1,1462,98,98,98
BEGIN DESCRIPTION:
Mapping XS 9c4e3a4b
END DESCRIPTION:
XS GIS Cut Line= 6
      1980588.53     13477753.72      1979942.72     13477437.76
      1980012.16     13477340.54      1979920.15     13477246.79
      1979821.19     13477319.70      1979349.46     13477286.75
#Sta/Elev= 30
  3877.2  568.65  3953.7  566.48  4021.2  559.19  4049.3  553.73  4059.2  554.64
  4071.8  552.89  4348.7  540.82  4550.1  537.07  4627.8  539.01  4635.1  540.12
  4656.1  538.99  4691.5  539.67  4709.4  538.48  4714.6  539.77  4728.5  539.93
  4733.6  538.75  4816.9  538.10  4891.2  539.50  4899.4  539.61  4990.7  536.66
  4991.2  535.86  4996.8  536.66  5023.8  539.57  5117.9  540.66  5184.2  543.67
  5214.3  547.26  5259.8  555.91  5264.8  554.41  5314.5  555.97  5450.4  562.02
#Mann=5,-1,0
  3877.2     0.1       0  4891.2    0.05       0  4899.4     0.1       0
  4990.7    0.07       0  4996.8     0.1       0
Bank Sta=4990.7,4996.8
Exp/Cntr=0.3,0.1

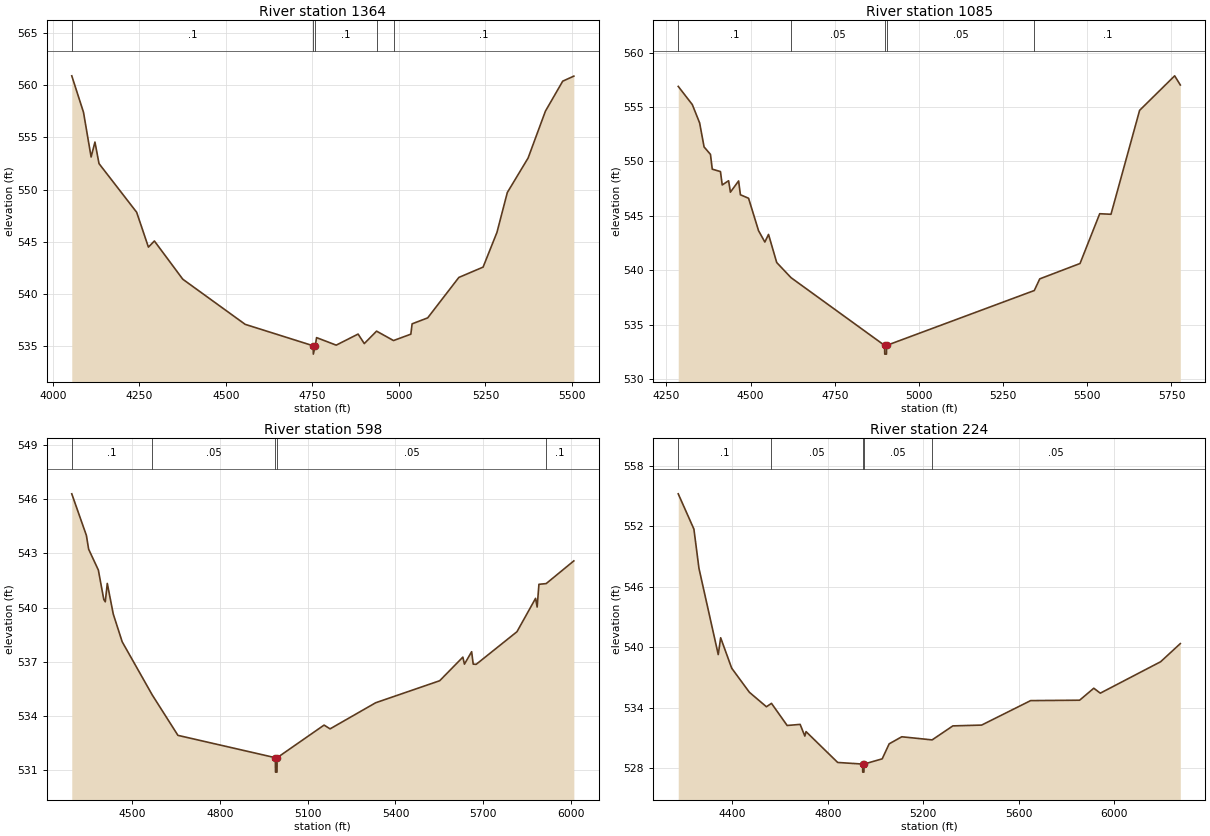
Type RM Length L Ch R = 1,1364,279,279,279
BEGIN DESCRIPTION:
Mapping XS 1f5d3fdf
END DESCRIPTION:
XS GIS Cut Line= 6
      1980505.69     13477671.28      1980003.91     13477436.89
      1980056.00     13477358.77      1979946.62     13477199.04
      1979819.89     13477252.86      1979352.92     13477268.49
#Sta/Elev= 30
  4054.7  560.89  4088.6  557.40  4110.6  553.12  4121.7  554.55  4133.4  552.49
  4242.2  547.83  4276.2  544.49  4293.4  545.08  4375.5  541.42  4555.8  537.10
  4752.2  535.05  4752.7  534.25  4758.3  535.05  4762.0  535.83  4818.8  535.11
  4882.0  536.17  4899.9  535.26  4935.4  536.45  4984.4  535.55  5034.4  536.16
  5038.1  537.15  5083.1  537.72  5173.1  541.59  5243.2  542.58  5283.2  545.90
  5313.2  549.72  5373.2  553.02  5423.3  557.51  5473.3  560.38  5505.4  560.86
#Mann=5,-1,0
  4054.7     0.1       0  4752.2    0.07       0  4758.3     0.1       0
  4935.4    0.05       0  4984.4     0.1       0
Bank Sta=4752.2,4758.3
Exp/Cntr=0.3,0.1

Type RM Length L Ch R = 1,1085,487,487,487
BEGIN DESCRIPTION:
Mapping XS a4c8dfee
END DESCRIPTION:
XS GIS Cut Line= 3
      1980734.04     13477327.38      1979937.20     13477009.69
      1979328.90     13477186.46
#Sta/Elev= 30
  4284.9  556.89  4326.7  555.22  4348.5  553.53  4361.7  551.33  4380.6  550.65
  4386.0  549.29  4410.3  549.07  4415.6  547.84  4434.5  548.23  4439.9  547.18
  4464.2  548.21  4469.6  546.94  4493.8  546.62  4523.5  543.64  4542.2  542.60
  4553.1  543.30  4577.4  540.72  4619.9  539.33  4897.8  533.11  4898.3  532.31
  4903.4  532.31  4903.9  533.11  5342.5  538.15  5358.7  539.22  5478.3  540.63
  5536.8  545.20  5570.3  545.15  5655.3  554.69  5759.4  557.86  5776.2  557.02
#Mann=5,-1,0
  4284.9     0.1       0  4619.9    0.05       0  4897.8   0.035       0
  4903.9    0.05       0  5342.5     0.1       0
Bank Sta=4897.8,4903.9
Exp/Cntr=0.3,0.1

Type RM Length L Ch R = 1,598,374,374,374
BEGIN DESCRIPTION:
Mapping XS f18002bc
END DESCRIPTION:
XS GIS Cut Line= 4
      1980821.44     13477194.09      1980752.01     13476836.50
      1980147.84     13476711.50      1979463.81     13476975.39
#Sta/Elev= 30
  4294.6  546.31  4344.6  544.00  4352.2  543.24  4385.4  542.08  4403.9  540.45
  4409.0  540.32  4415.9  541.34  4436.3  539.64  4466.8  538.10  4569.5  535.15
  4657.1  532.91  4989.8  531.67  4990.3  530.87  4995.4  530.87  4995.9  531.67
  5156.2  533.48  5176.6  533.27  5332.5  534.72  5550.9  535.94  5630.0  537.25
  5635.4  536.86  5660.0  537.55  5665.4  536.86  5675.5  536.85  5814.8  538.66
  5878.3  540.51  5883.7  540.03  5889.8  541.29  5914.5  541.33  6009.0  542.59
#Mann=5,-1,0
  4294.6     0.1       0  4569.5    0.05       0  4989.8    0.03       0
  4995.9    0.05       0  5914.5     0.1       0
Bank Sta=4989.8,4995.9
Exp/Cntr=0.3,0.1

Type RM Length L Ch R = 1,224,0,0,0
BEGIN DESCRIPTION:
UNT 023 in RCW 1.0
END DESCRIPTION:
XS GIS Cut Line= 4
      1980918.98     13477231.07      1980832.74     13476568.27
      1980304.09     13476422.43      1979533.28     13476857.31
#Sta/Elev= 30
  4174.0  555.24  4239.6  551.74  4260.8  547.84  4341.5  539.28  4351.6  540.95
  4397.8  537.93  4471.8  535.54  4543.2  534.10  4564.3  534.44  4630.0  532.24
  4684.3  532.35  4704.0  531.19  4709.1  531.63  4841.5  528.57  4945.8  528.41
  4946.3  527.61  4951.4  527.61  4951.9  528.41  5027.9  528.93  5057.1  530.42
  5109.8  531.12  5236.9  530.81  5323.6  532.20  5444.1  532.28  5649.2  534.71
  5854.3  534.75  5913.6  535.94  5940.9  535.45  6193.5  538.57  6275.8  540.37
#Mann=5,-1,0
  4174.0     0.1       0  4564.3    0.05       0  4945.8    0.07       0
  4951.9    0.05       0  5236.9    0.05       0
Bank Sta=4945.8,4951.9
Exp/Cntr=0.3,0.1

Chan Stop Cuts=-1