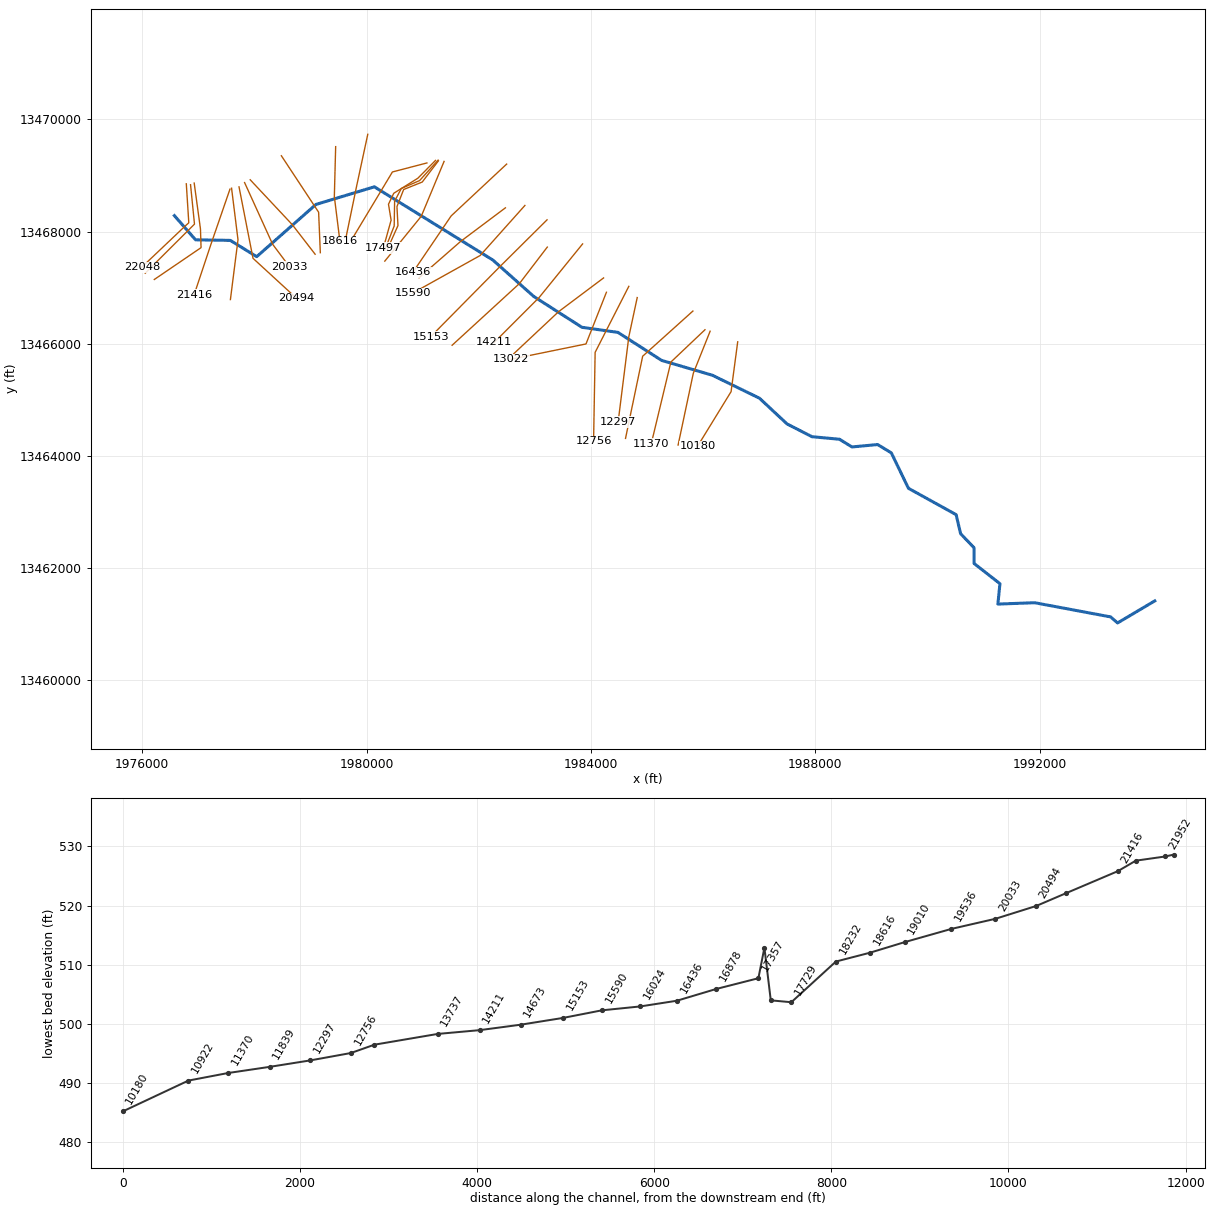
--- UNT 024 in RCW.prj (project) ---

Proj Title=UNT 024 in RCW Base Level Engineering
Current Plan=p01
Default Exp/Contr=0.3,0.1
English Units
Geom File=g01
Flow File=f01
Plan File=p01
Y Axis Title=Elevation
X Axis Title(PF)=Main Channel Distance
X Axis Title(XS)=Station
BEGIN DESCRIPTION:
UNT 024 in RCW
END DESCRIPTION:
DSS Export Rating Curves= 0
DSS Export Rating Curve Sorted= 0
DSS Export Volume Flow Curves= 0
DXF OffsetX= 0
DXF OffsetY= 0
DXF ScaleX= 1
DXF ScaleY= 10

--- UNT 024 in RCW.p01 (plan) ---

Plan Title=Multiple Run
Short Identifier=Multiple
Geom File=g01
Flow File=f01
Subcritical Flow
K Sum by GR= 0
Std Step Tol= 0.01
Critical Tol= 0.01
Num of Std Step Trials= 20
Max Error Tol= 0.3
Flow Tol Ratio= 0.001
Split Flow NTrial= 30
Split Flow Tol= 0.02
Split Flow Ratio= 0.02
Log Output Level= 0
Friction Slope Method= 1
Unsteady Friction Slope Method= 2
Unsteady Bridges Friction Slope Method= 1
Parabolic Critical Depth
Global Vel Dist=  1 , 1 , 1
Global Log Level= 0
CheckData=True
Encroach Param= -1, 0, 0, 0
BEGIN DESCRIPTION:
Multiple Run
END DESCRIPTION:

--- UNT 024 in RCW.f01 (steady flow) ---

Flow Title=Multiple
Program Version=5.05
Number of Profiles= 7
Profile Names=10-year,25-year,50-year,1pct_min,100-year,1pct_plu,500-year
River Rch & RM=UNT 024 in RCW,Reach-1         ,22048
     166     227     276     168     335     669     501
River Rch & RM=UNT 024 in RCW,Reach-1         ,20494
     297     417     518     321     640    1276     991
River Rch & RM=UNT 024 in RCW,Reach-1         ,17729
     352     497     620     385     768    1533    1198
River Rch & RM=UNT 024 in RCW,Reach-1         ,13737
     357     502     624     386     770    1537    1193
River Rch & RM=UNT 024 in RCW,Reach-1         ,12756
     519     741     930     580    1158    2310    1823
River Rch & RM=UNT 024 in RCW,Reach-1         ,8296
     519     741     930     580    1158    2310    1823
River Rch & RM=UNT 024 in RCW,Reach-1         ,2968
     761    1106    1403     885    1765    3521    2838
Boundary for River Rch & Prof#=UNT 024 in RCW,Reach-1         , 1
Up Type= 0
Dn Type= 3
Dn Slope=0.00613
Boundary for River Rch & Prof#=UNT 024 in RCW,Reach-1         , 2
Up Type= 0
Dn Type= 3
Dn Slope=0.00613
Boundary for River Rch & Prof#=UNT 024 in RCW,Reach-1         , 3
Up Type= 0
Dn Type= 3
Dn Slope=0.00613
Boundary for River Rch & Prof#=UNT 024 in RCW,Reach-1         , 4
Up Type= 0
Dn Type= 3
Dn Slope=0.00613
Boundary for River Rch & Prof#=UNT 024 in RCW,Reach-1         , 5
Up Type= 0
Dn Type= 3
Dn Slope=0.00613
Boundary for River Rch & Prof#=UNT 024 in RCW,Reach-1         , 6
Up Type= 0
Dn Type= 3
Dn Slope=0.00613
Boundary for River Rch & Prof#=UNT 024 in RCW,Reach-1         , 7
Up Type= 0
Dn Type= 3
Dn Slope=0.00613
DSS Import GetInterval= 0
DSS Import GetPeak= 0
DSS Import FillOption= 0

--- UNT 024 in RCW.g01 (geometry) ---

Geom Title=Existing Conditions

River Reach=UNT 024 in RCW,Reach-1
Reach XY= 30
      1976573.23     13468285.62      1976950.80     13467854.54
      1977570.80     13467844.54      1978040.80     13467554.54
      1979097.40     13468485.55      1980138.40     13468799.72
      1982250.80     13467494.54      1982980.80     13466844.54
      1983840.80     13466294.54      1984480.80     13466204.54
      1985260.80     13465704.54      1986164.44     13465440.42
      1987004.78     13465030.55      1987495.82     13464572.36
      1987940.80     13464344.54      1988431.15     13464298.92
      1988653.77     13464161.70      1989110.80     13464204.54
      1989355.28     13464056.66      1989660.80     13463424.54
      1990510.80     13462954.54      1990590.80     13462614.54
      1990830.80     13462364.54      1990830.80     13462084.54
      1991291.91     13461723.94      1991255.45     13461360.22
      1991910.80     13461384.54      1993264.65     13461131.76
      1993389.13     13461023.95      1994052.49     13461416.79

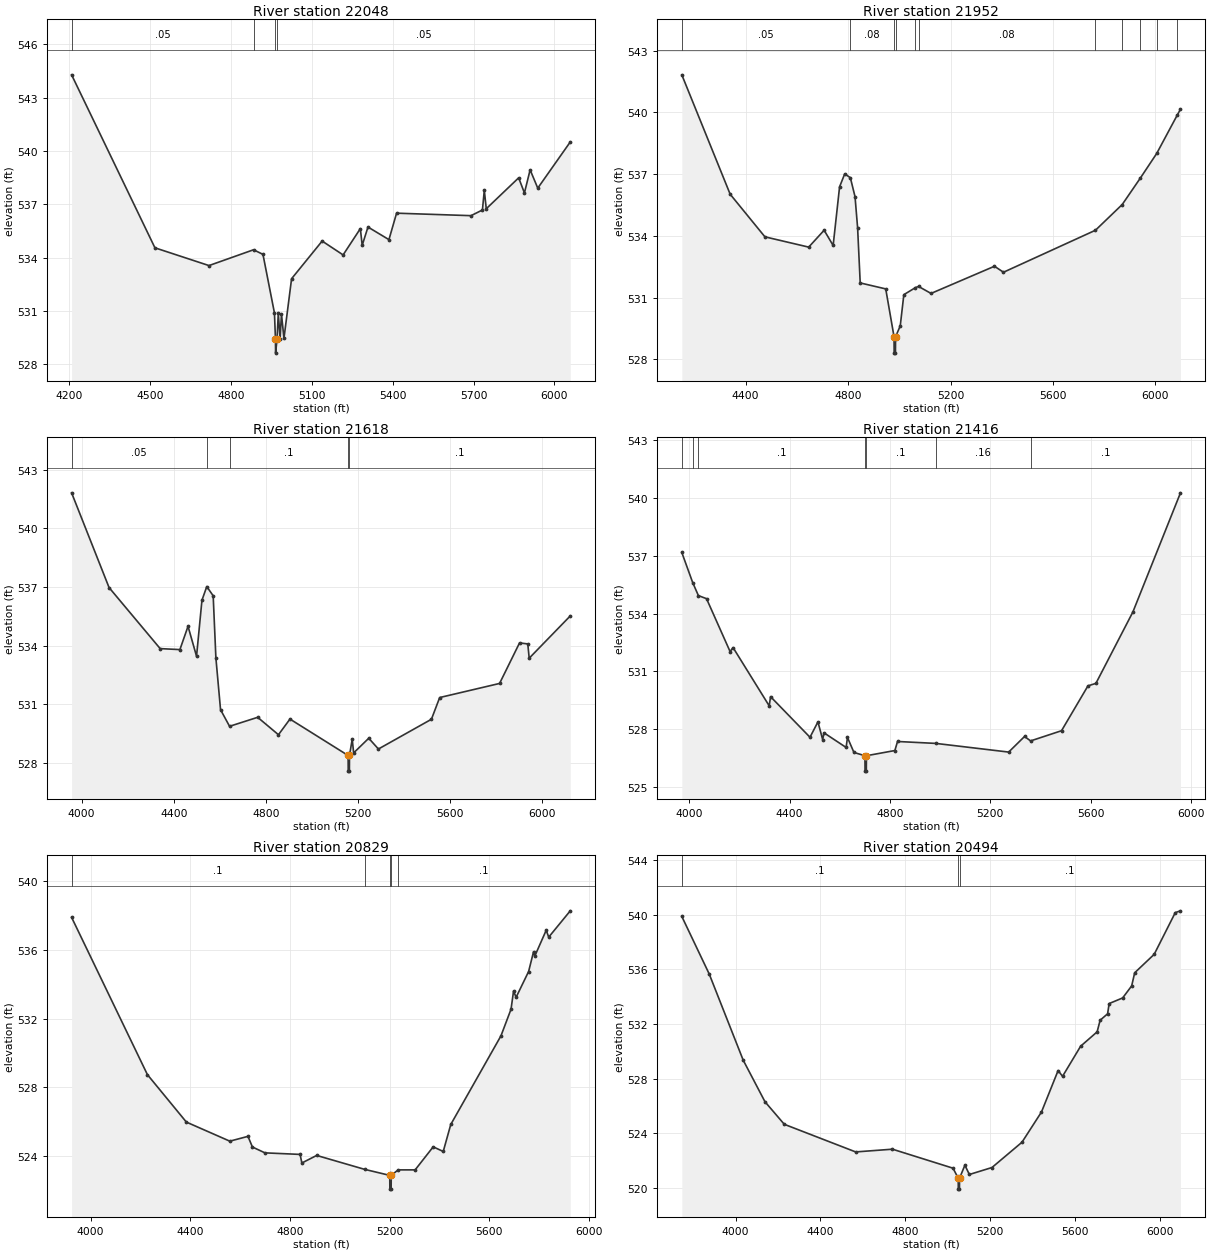
Type RM Length L Ch R = 1,22048,96,96,96
BEGIN DESCRIPTION:
UNT 024 in RCW 34.0
END DESCRIPTION:
XS GIS Cut Line= 4
      1976785.71     13468853.27      1976829.98     13468157.96
      1976768.55     13468103.33      1975992.47     13467367.19
#Sta/Elev= 30
  4209.9  544.29  4518.8  534.55  4719.2  533.55  4884.4  534.44  4919.3  534.18
  4961.9  530.88  4965.6  529.42  4966.1  528.62  4971.6  529.42  4976.1  530.87
  4982.8  529.44  4987.9  530.82  4997.1  529.45  5025.4  532.81  5138.7  534.93
  5216.4  534.15  5280.3  535.63  5287.2  534.69  5308.6  535.72  5386.3  535.01
  5414.6  536.50  5690.5  536.36  5732.9  536.68  5739.8  537.79  5747.1  536.75
  5867.2  538.49  5888.6  537.64  5909.7  538.94  5938.0  537.91  6058.5  540.51
#Mann=4,-1,0
  4209.9    0.05       0  4884.4    0.08       0  4965.6   0.035       0
  4971.6    0.05       0
Bank Sta=4965.6,4971.6
Exp/Cntr=0.3,0.1

Type RM Length L Ch R = 1,21952,334,334,334
BEGIN DESCRIPTION:
Mapping XS 4e612bfc
END DESCRIPTION:
XS GIS Cut Line= 3
      1976861.22     13468837.68      1976931.54     13468134.52
      1976053.47     13467259.77
#Sta/Elev= 30
  4151.4  541.82  4340.1  536.02  4475.7  533.95  4646.6  533.45  4706.8  534.27
  4742.0  533.53  4767.1  536.38  4787.2  537.01  4809.2  536.82  4827.4  535.90
  4837.5  534.38  4847.6  531.71  4947.2  531.42  4979.6  529.10  4980.1  528.30
  4985.1  528.30  4985.6  529.10  5003.8  529.62  5017.9  531.14  5062.9  531.48
  5075.3  531.54  5124.0  531.20  5371.5  532.52  5406.8  532.23  5765.7  534.27
  5870.2  535.52  5941.2  536.81  6004.7  538.00  6085.6  539.88  6097.5  540.15
#Mann=11,-1,0
  4151.4    0.05       0  4809.2    0.08       0  4979.6    0.07       0
  4985.6    0.08       0  5062.9    0.05       0  5075.3    0.08       0
  5765.7     0.1       0  5870.2    0.08       0  5941.2     0.1       0
  6004.7    0.08       0  6085.6     0.1       0
Bank Sta=4979.6,4985.6
Exp/Cntr=0.3,0.1

Type RM Length L Ch R = 1,21618,202,202,202
BEGIN DESCRIPTION:
Mapping XS 71b27717
END DESCRIPTION:
XS GIS Cut Line= 4
      1976926.33     13468866.31      1977038.31     13468045.98
      1977048.73     13467715.25      1976215.37     13467147.52
#Sta/Elev= 30
  3956.2  541.81  4119.0  536.97  4341.1  533.85  4426.9  533.80  4462.2  534.99
  4499.2  533.46  4522.7  536.32  4543.6  537.02  4571.5  536.55  4583.3  533.37
  4603.5  530.73  4642.7  529.88  4764.9  530.34  4855.2  529.45  4905.2  530.25
  5157.9  528.39  5158.4  527.59  5163.4  527.59  5163.9  528.39  5175.8  529.22
  5181.9  528.52  5247.6  529.27  5289.6  528.72  5520.0  530.24  5555.9  531.35
  5816.2  532.07  5902.9  534.14  5938.8  534.09  5944.9  533.36  6123.4  535.52
#Mann=5,-1,0
  3956.2    0.05       0  4543.6    0.08       0  4642.7     0.1       0
  5157.9    0.07       0  5163.9     0.1       0
Bank Sta=5157.9,5163.9
Exp/Cntr=0.3,0.1

Type RM Length L Ch R = 1,21416,587,587,587
BEGIN DESCRIPTION:
UNT 024 in RCW 33.0
END DESCRIPTION:
XS GIS Cut Line= 3
      1977564.11     13468758.25      1977225.00     13467775.00
      1976924.99     13466874.97
#Sta/Elev= 30
  3970.0  537.18  4013.3  535.62  4036.1  534.94  4068.6  534.78  4162.6  532.03
  4174.4  532.24  4318.6  529.21  4323.9  529.69  4481.2  527.58  4512.9  528.38
  4531.7  527.46  4537.0  527.81  4625.3  527.05  4630.6  527.57  4656.5  526.79
  4700.3  526.62  4700.8  525.82  4705.8  525.82  4706.3  526.62  4819.7  526.89
  4830.3  527.36  4983.2  527.26  5273.6  526.81  5336.9  527.62  5361.0  527.39
  5484.4  527.92  5589.8  530.25  5621.5  530.38  5769.0  534.09  5958.8  540.28
#Mann=7,-1,0
  3970.0     0.1       0  4013.3    0.08       0  4036.1     0.1       0
  4700.3    0.07       0  4706.3     0.1       0  4983.2    0.16       0
  5361.0     0.1       0
Bank Sta=4700.3,4706.3
Exp/Cntr=0.3,0.1

Type RM Length L Ch R = 1,20829,335,335,335
BEGIN DESCRIPTION:
UNT 024 in RCW 32.0
END DESCRIPTION:
XS GIS Cut Line= 3
      1977592.77     13468775.18      1977707.35     13467855.93
      1977572.05     13466789.14
#Sta/Elev= 30
  3923.4  537.89  4227.7  528.74  4384.1  525.98  4558.5  524.87  4631.4  525.15
  4649.2  524.53  4699.5  524.19  4840.6  524.10  4847.7  523.60  4907.2  524.04
  5099.7  523.23  5200.5  522.88  5201.0  522.08  5206.0  522.08  5206.5  522.88
  5234.2  523.20  5302.4  523.20  5374.9  524.54  5415.2  524.27  5445.4  525.84
  5647.0  531.00  5687.4  532.55  5697.4  533.60  5707.7  533.24  5757.9  534.74
  5777.7  535.89  5782.8  535.64  5828.5  537.14  5838.6  536.74  5925.1  538.27
#Mann=5,-1,0
  3923.4     0.1       0  5099.7    0.12       0  5200.5    0.07       0
  5206.5    0.12       0  5234.2     0.1       0
Bank Sta=5200.5,5206.5
Exp/Cntr=0.3,0.1

Type RM Length L Ch R = 1,20494,461,461,461
BEGIN DESCRIPTION:
UNT 024 in RCW 31.0
END DESCRIPTION:
XS GIS Cut Line= 3
      1977725.57     13468798.68      1977975.00     13467525.00
      1978749.01     13466814.27
#Sta/Elev= 30
  3746.9  539.87  3876.0  535.66  4036.0  529.36  4138.6  526.32  4229.6  524.67
  4565.8  522.65  4739.1  522.85  5024.4  521.46  5048.7  520.73  5049.2  519.93
  5054.5  519.93  5055.0  520.73  5080.2  521.68  5101.2  521.00  5207.7  521.51
  5349.1  523.36  5440.9  525.57  5519.2  528.60  5540.2  528.18  5625.3  530.38
  5703.0  531.43  5717.2  532.28  5752.3  532.75  5759.7  533.50  5823.2  533.91
  5865.7  534.79  5879.9  535.75  5971.8  537.10  6071.1  540.15  6095.6  540.28
#Mann=3,-1,0
  3746.9     0.1       0  5048.7    0.07       0  5055.0     0.1       0
Bank Sta=5048.7,5055
Exp/Cntr=0.3,0.1

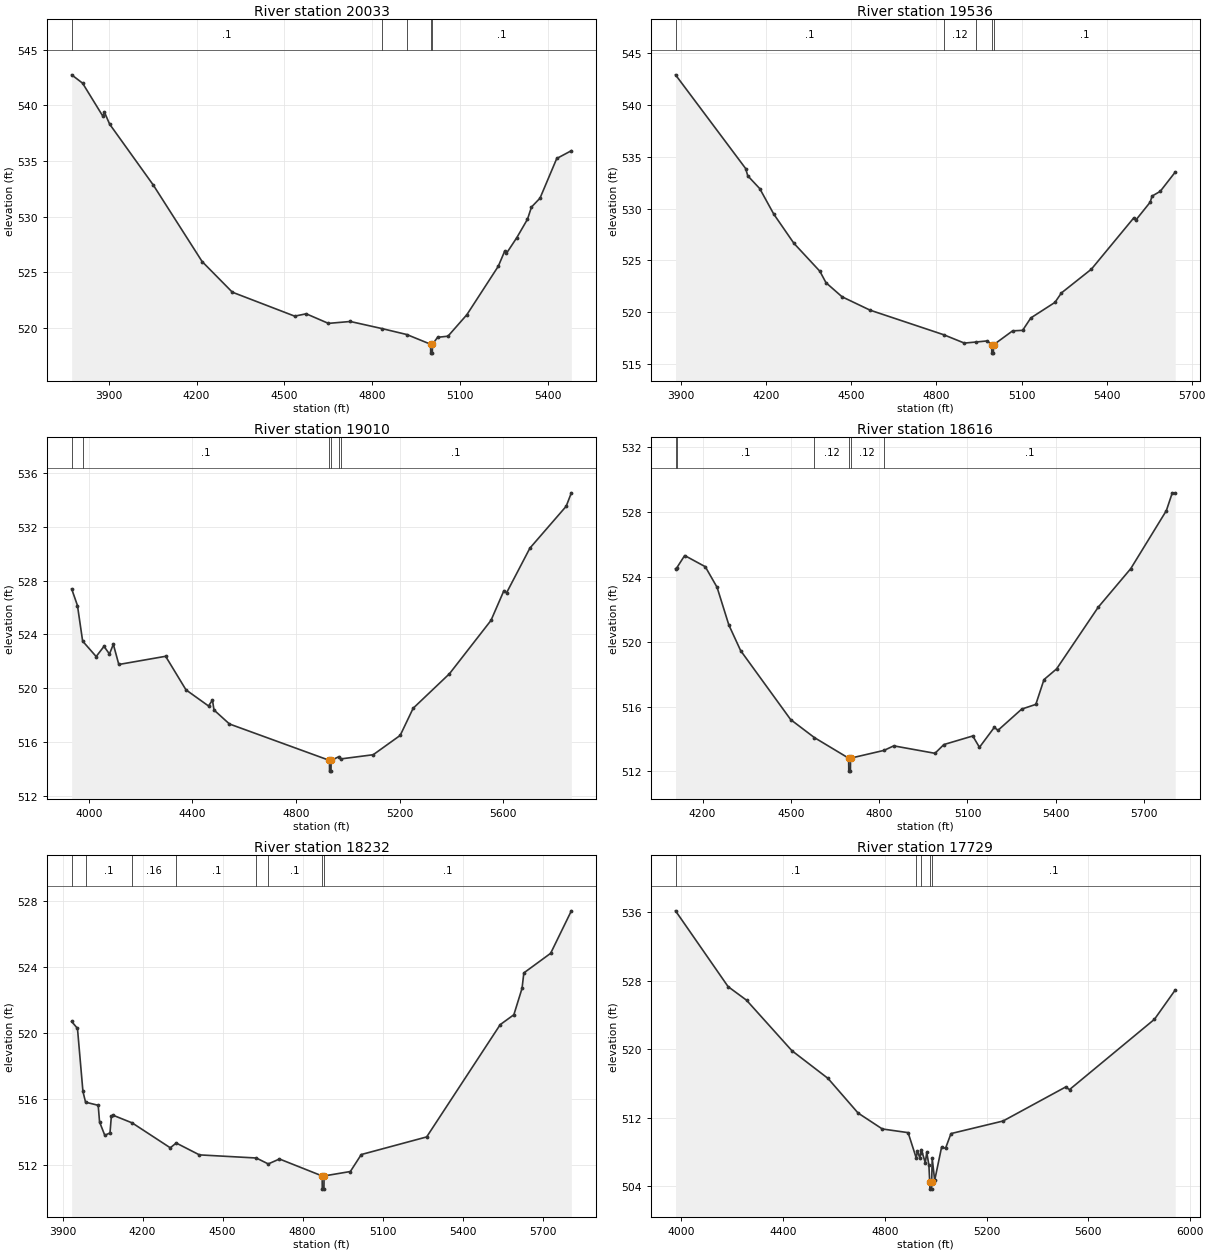
Type RM Length L Ch R = 1,20033,497,497,497
BEGIN DESCRIPTION:
UNT 024 in RCW 30.0
END DESCRIPTION:
XS GIS Cut Line= 3
      1977824.98     13468875.03      1978325.00     13467775.00
      1978624.97     13467375.03
#Sta/Elev= 30
  3772.9  542.74  3810.3  541.99  3879.5  539.03  3885.0  539.39  3902.6  538.32
  4051.9  532.85  4218.9  525.98  4322.2  523.23  4535.3  521.08  4574.8  521.29
  4650.6  520.43  4725.3  520.60  4832.6  519.97  4918.5  519.43  4999.9  518.56
  5000.4  517.76  5005.8  517.76  5006.3  518.56  5024.0  519.18  5059.4  519.28
  5124.0  521.21  5231.2  525.55  5253.1  526.90  5259.4  526.72  5294.8  528.13
  5331.2  529.78  5344.8  530.87  5374.0  531.67  5431.2  535.23  5481.2  535.93
#Mann=5,-1,0
  3772.9     0.1       0  4832.6    0.12       0  4918.5     0.1       0
  4999.9    0.07       0  5006.3     0.1       0
Bank Sta=4999.9,5006.3
Exp/Cntr=0.3,0.1

Type RM Length L Ch R = 1,19536,526,526,526
BEGIN DESCRIPTION:
UNT 024 in RCW 29.0
END DESCRIPTION:
XS GIS Cut Line= 3
      1977924.98     13468925.02      1978675.00     13468125.00
      1979082.35     13467598.12
#Sta/Elev= 30
  3879.5  542.92  4126.9  533.87  4134.3  533.17  4176.7  531.93  4226.1  529.47
  4296.9  526.66  4388.8  523.95  4410.2  522.85  4466.9  521.49  4565.6  520.20
  4825.0  517.83  4898.2  517.02  4938.2  517.12  4979.3  517.23  4994.6  516.85
  4995.1  516.05  5000.6  516.05  5001.1  516.85  5068.5  518.20  5103.8  518.25
  5132.8  519.45  5217.9  520.95  5240.6  521.86  5346.5  524.16  5495.9  529.11
  5504.1  528.93  5553.9  530.63  5560.2  531.21  5589.2  531.67  5642.1  533.53
#Mann=5,-1,0
  3879.5     0.1       0  4825.0    0.12       0  4938.2     0.1       0
  4994.6    0.07       0  5001.1     0.1       0
Bank Sta=4994.6,5001.1
Exp/Cntr=0.3,0.1

Type RM Length L Ch R = 1,19010,394,394,394
BEGIN DESCRIPTION:
UNT 024 in RCW 28.0
END DESCRIPTION:
XS GIS Cut Line= 3
      1978480.77     13469353.34      1979144.85     13468346.38
      1979175.00     13467625.03
#Sta/Elev= 30
  3934.2  527.39  3956.6  526.15  3976.6  523.50  4028.8  522.35  4059.0  523.11
  4080.0  522.54  4095.1  523.26  4116.2  521.76  4296.8  522.37  4375.4  519.87
  4462.4  518.67  4477.5  519.11  4483.5  518.37  4543.1  517.33  4928.9  514.62
  4929.4  513.82  4934.9  513.82  4935.4  514.62  4965.8  514.90  4973.0  514.73
  5097.7  515.04  5201.9  516.48  5251.9  518.50  5392.0  521.07  5552.2  525.04
  5602.2  527.26  5612.2  527.09  5702.3  530.42  5842.4  533.54  5862.4  534.54
#Mann=6,-1,0
  3934.2    0.08       0  3976.6     0.1       0  4928.9    0.07       0
  4935.4     0.1       0  4965.8    0.12       0  4973.0     0.1       0
Bank Sta=4928.9,4935.4
Exp/Cntr=0.3,0.1

Type RM Length L Ch R = 1,18616,384,384,384
BEGIN DESCRIPTION:
UNT 024 in RCW 27.0
END DESCRIPTION:
XS GIS Cut Line= 3
      1979448.67     13469516.10      1979425.00     13468625.00
      1979525.00     13467825.04
#Sta/Elev= 30
  4108.2  524.52  4111.8  524.55  4139.3  525.33  4209.3  524.64  4249.3  523.37
  4289.4  521.04  4329.4  519.46  4499.4  515.20  4580.0  514.09  4696.3  512.82
  4696.8  512.02  4702.3  512.02  4702.8  512.82  4816.4  513.30  4849.6  513.58
  4989.6  513.12  5019.8  513.66  5118.0  514.19  5140.7  513.49  5191.1  514.72
  5203.7  514.54  5284.3  515.85  5332.2  516.14  5359.9  517.67  5402.7  518.33
  5543.8  522.13  5654.7  524.52  5775.6  528.10  5795.8  529.20  5805.8  529.16
#Mann=6,-1,0
  4108.2    0.08       0  4111.8     0.1       0  4580.0    0.12       0
  4696.3    0.07       0  4702.8    0.12       0  4816.4     0.1       0
Bank Sta=4696.3,4702.8
Exp/Cntr=0.3,0.1

Type RM Length L Ch R = 1,18232,503,503,503
BEGIN DESCRIPTION:
UNT 024 in RCW 26.0
END DESCRIPTION:
XS GIS Cut Line= 3
      1980021.14     13469736.32      1979825.00     13468825.00
      1979634.22     13467903.94
#Sta/Elev= 30
  3934.2  520.71  3956.0  520.29  3976.5  516.46  3986.3  515.81  4033.7  515.62
  4038.8  514.61  4058.3  513.80  4077.9  513.94  4083.0  514.96  4089.0  515.02
  4161.2  514.55  4303.8  513.04  4326.1  513.33  4413.0  512.61  4626.2  512.42
  4671.0  512.06  4713.0  512.36  4873.0  511.33  4873.5  510.53  4879.7  510.53
  4880.2  511.33  4978.7  511.60  5019.6  512.63  5264.7  513.70  5540.4  520.52
  5591.5  521.12  5622.1  522.72  5628.9  523.66  5729.3  524.85  5807.0  527.43
#Mann=8,-1,0
  3934.2    0.08       0  3986.3     0.1       0  4161.2    0.16       0
  4326.1     0.1       0  4626.2    0.12       0  4671.0     0.1       0
  4873.0    0.07       0  4880.2     0.1       0
Bank Sta=4873,4880.2
Exp/Cntr=0.3,0.1

Type RM Length L Ch R = 1,17729,232,232,232
BEGIN DESCRIPTION:
UNT 024 in RCW 25.0
END DESCRIPTION:
XS GIS Cut Line= 3
      1981075.05     13469225.01      1980460.60     13469064.48
      1979775.00     13467925.00
#Sta/Elev= 30
  3977.2  536.17  4184.0  527.31  4256.3  525.73  4434.7  519.83  4576.7  516.59
  4695.1  512.54  4790.3  510.68  4891.8  510.25  4923.8  507.28  4928.2  508.13
  4937.9  507.29  4941.1  507.83  4943.7  508.27  4959.3  506.74  4965.1  507.95
  4973.5  506.45  4976.8  504.45  4977.4  503.65  4983.8  503.65  4984.4  504.45
  4986.5  507.25  4996.2  504.67  5023.4  508.56  5038.9  508.42  5060.3  510.14
  5265.2  511.61  5510.9  515.58  5526.4  515.28  5860.5  523.50  5942.1  526.92
#Mann=5,-1,0
  3977.2     0.1       0  4923.8    0.07       0  4941.1     0.1       0
  4976.8    0.07       0  4984.4     0.1       0
Bank Sta=4976.8,4984.4
Exp/Cntr=0.3,0.1

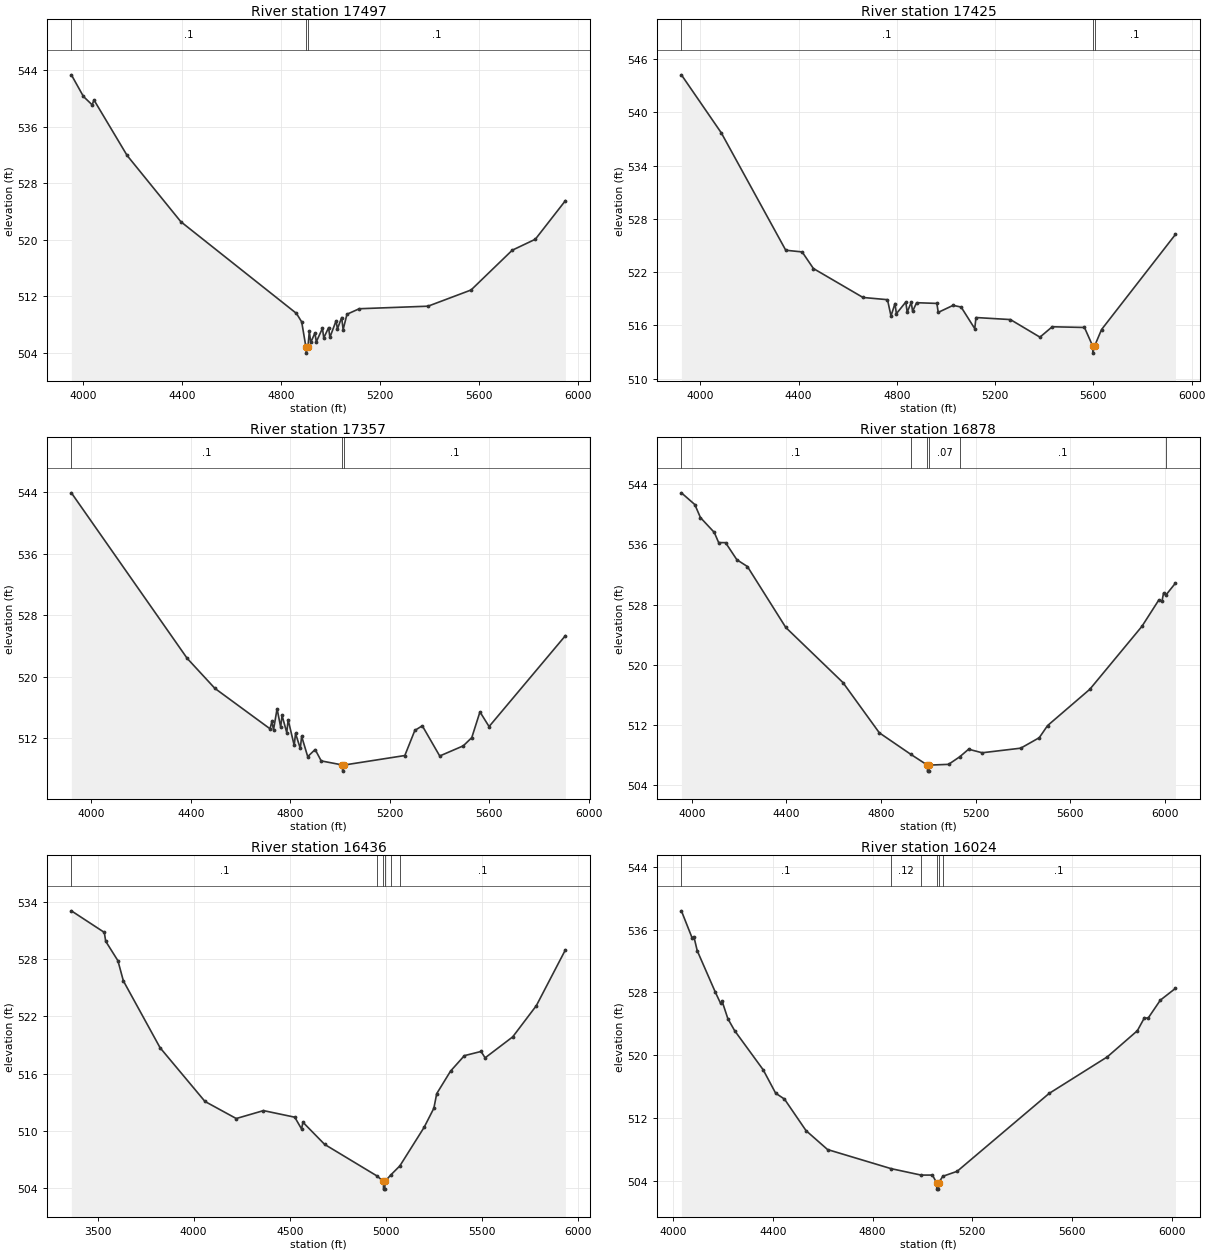
Type RM Length L Ch R = 1,17497,72,72,72
BEGIN DESCRIPTION:
Mapping XS 420f1883
END DESCRIPTION:
XS GIS Cut Line= 6
      1981228.83     13469270.21      1980913.73     13468952.50
      1980484.04     13468684.27      1980390.29     13468488.96
      1980437.17     13468205.11      1980299.15     13467707.72
#Sta/Elev= 30
  3951.8  543.34  4000.6  540.28  4036.0  539.09  4043.1  539.79  4177.4  531.93
  4394.8  522.56  4862.5  509.59  4883.8  508.39  4901.2  504.77  4901.8  503.97
  4908.9  504.77  4914.6  507.06  4920.4  505.48  4937.5  506.83  4942.9  505.57
  4967.8  507.48  4973.1  506.12  4992.7  507.58  4998.0  506.20  5023.0  508.55
  5028.3  507.39  5045.6  509.01  5051.5  507.29  5067.0  509.47  5116.7  510.25
  5395.0  510.61  5569.1  512.90  5735.8  518.53  5829.2  520.08  5950.9  525.54
#Mann=3,-1,0
  3951.8     0.1       0  4901.2    0.07       0  4908.9     0.1       0
Bank Sta=4901.2,4908.9
Exp/Cntr=0.3,0.1

Type RM Length L Ch R = 1,17425,68,68,68
BEGIN DESCRIPTION:
UNT 024 in RCW 24.0
END DESCRIPTION:
XS GIS Cut Line= 6
      1981275.00     13469274.99      1980944.98     13468910.84
      1980619.46     13468770.21      1980499.67     13468543.65
      1980491.85     13468100.94      1980325.00     13467675.01
#Sta/Elev= 30
  3923.0  544.22  4085.5  537.68  4347.8  524.46  4414.5  524.27  4460.4  522.40
  4662.2  519.14  4761.9  518.89  4776.2  517.06  4792.5  518.46  4798.1  517.31
  4836.5  518.63  4842.1  517.48  4858.5  518.59  4864.1  517.59  4880.5  518.55
  4962.9  518.47  4968.5  517.46  5028.9  518.25  5061.7  518.06  5117.1  515.63
  5122.1  516.88  5262.4  516.65  5382.5  514.67  5432.5  515.84  5563.7  515.76
  5597.2  513.67  5597.8  512.87  5604.9  513.67  5633.3  515.53  5934.0  526.24
#Mann=3,-1,0
  3923.0     0.1       0  5597.2    0.07       0  5604.9     0.1       0
Bank Sta=5597.2,5604.9
Exp/Cntr=0.3,0.1

Type RM Length L Ch R = 1,17357,479,479,479
BEGIN DESCRIPTION:
Mapping XS a61aa54d
END DESCRIPTION:
XS GIS Cut Line= 6
      1981280.93     13469262.42      1980991.85     13468884.79
      1980661.12     13468751.98      1980541.33     13468447.29
      1980559.56     13468108.75      1980364.23     13467671.22
#Sta/Elev= 30
  3919.6  543.93  4385.2  522.39  4496.7  518.48  4718.4  513.22  4725.8  514.17
  4732.5  513.09  4746.7  515.83  4761.3  513.44  4766.7  514.96  4785.8  512.71
  4791.1  514.41  4815.6  511.06  4821.0  512.62  4840.1  510.66  4845.5  512.24
  4869.9  509.60  4899.8  510.52  4924.3  509.04  5009.8  508.51  5010.4  507.71
  5017.5  508.51  5260.4  509.74  5300.7  513.01  5330.7  513.61  5400.7  509.68
  5495.4  511.00  5529.6  512.07  5562.5  515.42  5599.2  513.51  5906.1  525.34
#Mann=3,-1,0
  3919.6     0.1       0  5009.8    0.07       0  5017.5     0.1       0
Bank Sta=5009.8,5017.5
Exp/Cntr=0.3,0.1

Type RM Length L Ch R = 1,16878,442,442,442
BEGIN DESCRIPTION:
UNT 024 in RCW 23.0
END DESCRIPTION:
XS GIS Cut Line= 3
      1981381.61     13469252.84      1980975.00     13468275.00
      1980324.99     13467474.99
#Sta/Elev= 30
  3955.7  542.86  4012.5  541.30  4036.3  539.57  4094.8  537.60  4113.3  536.25
  4142.5  536.24  4190.3  533.97  4234.9  533.07  4397.3  524.97  4639.1  517.65
  4793.0  510.97  4927.1  508.09  4996.2  506.68  4996.8  505.88  5003.3  505.88
  5004.0  506.68  5085.8  506.78  5132.8  507.78  5170.6  508.79  5228.1  508.32
  5391.1  508.93  5469.4  510.32  5504.6  511.93  5683.5  516.76  5903.8  525.12
  5974.4  528.58  5988.7  528.47  5995.2  529.53  6006.8  529.34  6045.5  530.86
#Mann=6,-1,0
  3955.7     0.1       0  4927.1    0.07       0  4996.2    0.07       0
  5004.0    0.07       0  5132.8     0.1       0  6006.8    0.05       0
Bank Sta=4996.2,5004
Exp/Cntr=0.3,0.1

Type RM Length L Ch R = 1,16436,412,412,412
BEGIN DESCRIPTION:
UNT 024 in RCW 22.0
END DESCRIPTION:
XS GIS Cut Line= 3
      1982497.07     13469205.12      1981507.48     13468280.63
      1980824.99     13467274.99
#Sta/Elev= 30
  3364.0  533.07  3535.3  530.81  3542.6  529.88  3606.1  527.84  3634.4  525.73
  3825.4  518.72  4058.9  513.09  4221.6  511.30  4363.3  512.13  4526.0  511.44
  4561.1  510.21  4568.5  510.91  4681.3  508.59  4954.5  505.27  4987.0  504.70
  4987.7  503.90  4994.2  503.90  4994.8  504.70  5025.1  505.38  5072.7  506.34
  5198.5  510.37  5249.4  512.38  5264.3  513.91  5336.2  516.27  5408.1  517.89
  5494.9  518.33  5515.9  517.66  5659.6  519.86  5782.4  523.13  5933.6  528.98
#Mann=6,-1,0
  3364.0     0.1       0  4954.5    0.12       0  4987.0    0.07       0
  4994.8    0.12       0  5025.1    0.07       0  5072.7     0.1       0
Bank Sta=4987,4994.8
Exp/Cntr=0.3,0.1

Type RM Length L Ch R = 1,16024,434,434,434
BEGIN DESCRIPTION:
UNT 024 in RCW 21.0
END DESCRIPTION:
XS GIS Cut Line= 3
      1982474.97     13468424.98      1981675.00     13467825.00
      1980935.56     13467179.07
#Sta/Elev= 30
  4033.3  538.39  4076.0  534.96  4083.3  535.11  4096.8  533.31  4169.7  528.01
  4190.6  526.60  4196.8  526.86  4219.7  524.65  4246.8  523.13  4361.4  518.14
  4411.4  515.16  4446.8  514.41  4533.3  510.39  4619.7  507.98  4874.4  505.55
  4994.5  504.73  5040.4  504.73  5057.2  503.74  5057.9  502.94  5064.6  502.94
  5065.3  503.74  5081.7  504.57  5139.5  505.21  5508.4  515.13  5741.9  519.79
  5862.4  523.12  5890.9  524.78  5905.1  524.70  5954.5  527.01  6015.1  528.51
#Mann=6,-1,0
  4033.3     0.1       0  4874.4    0.12       0  4994.5    0.07       0
  5057.2    0.07       0  5065.3    0.07       0  5081.7     0.1       0
Bank Sta=5057.2,5065.3
Exp/Cntr=0.3,0.1

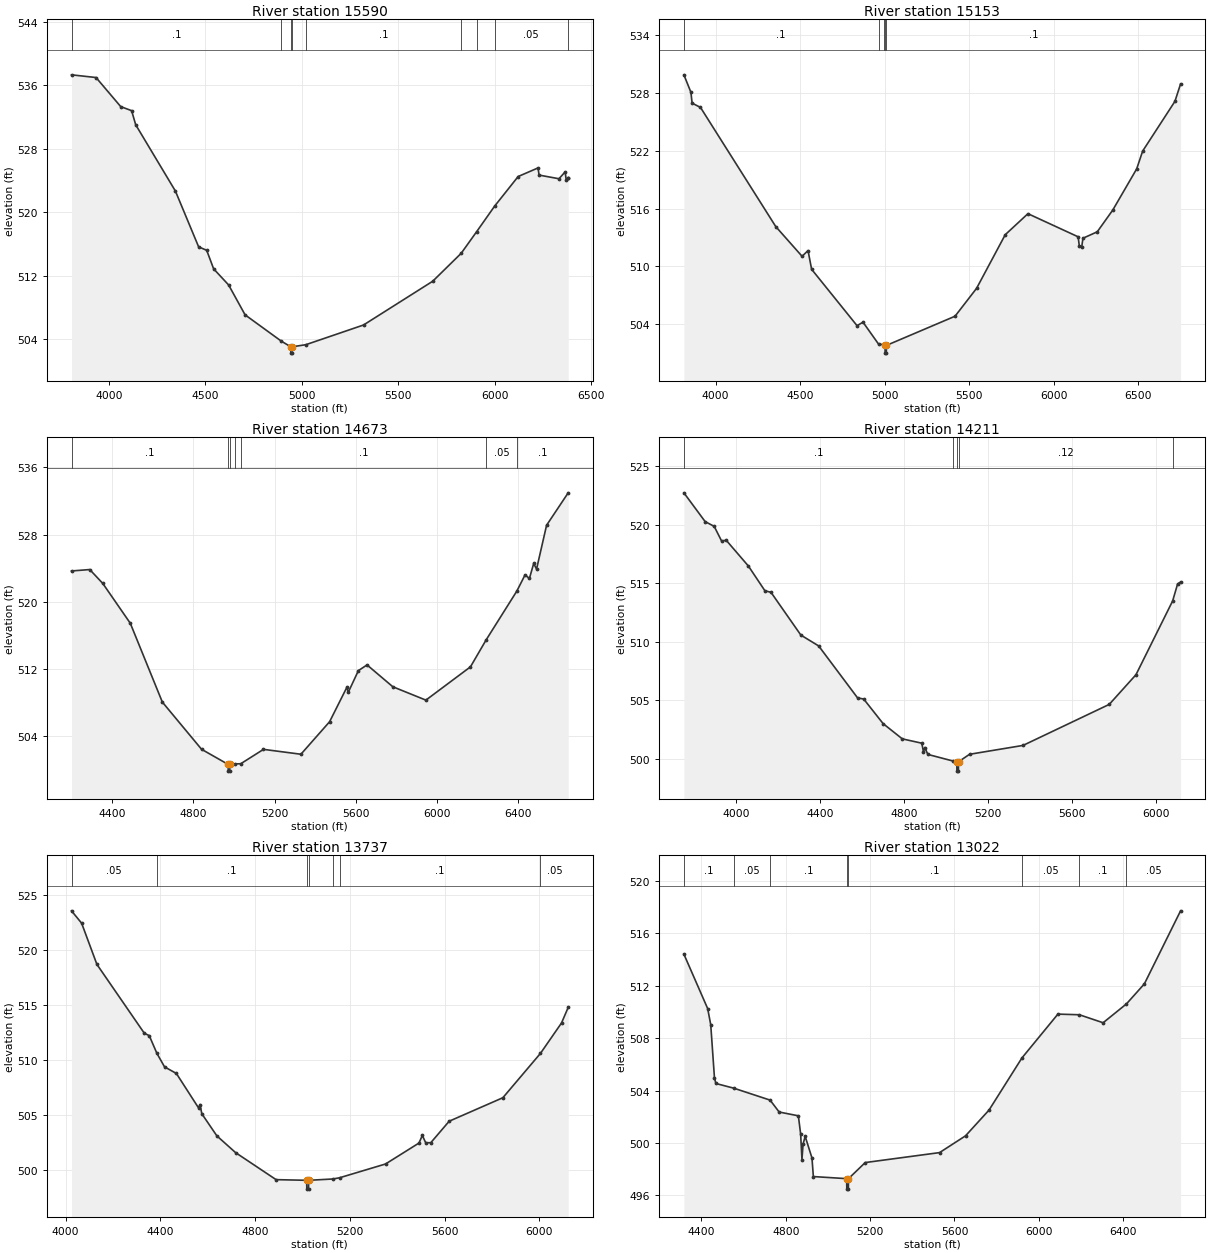
Type RM Length L Ch R = 1,15590,437,437,437
BEGIN DESCRIPTION:
UNT 024 in RCW 20.0
END DESCRIPTION:
XS GIS Cut Line= 3
      1982822.59     13468467.26      1982025.00     13467575.00
      1980821.75     13466904.78
#Sta/Elev= 30
  3807.0  537.31  3934.2  536.97  4062.1  533.31  4118.5  532.80  4139.8  531.02
  4345.5  522.68  4465.8  515.66  4507.7  515.22  4543.6  512.89  4621.3  510.86
  4706.6  507.10  4894.8  503.78  4943.3  503.08  4943.9  502.28  4950.7  502.28
  4951.4  503.08  5021.2  503.34  5320.4  505.82  5679.1  511.33  5826.4  514.84
  5907.1  517.58  5999.8  520.78  6121.8  524.51  6224.7  525.59  6230.4  524.69
  6333.3  524.23  6365.3  525.09  6371.0  524.07  6379.7  524.32  6381.1  524.32
#Mann=9,-1,0
  3807.0     0.1       0  4894.8    0.12       0  4943.3    0.07       0
  4951.4    0.12       0  5021.2     0.1       0  5826.4    0.05       0
  5907.1     0.1       0  5999.8    0.05       0  6379.7     0.1       0
Bank Sta=4943.3,4951.4
Exp/Cntr=0.3,0.1

Type RM Length L Ch R = 1,15153,480,480,480
BEGIN DESCRIPTION:
UNT 024 in RCW 19.0
END DESCRIPTION:
XS GIS Cut Line= 3
      1983217.55     13468211.18      1982375.00     13467375.00
      1981143.94     13466128.90
#Sta/Elev= 30
  3812.3  529.88  3853.8  528.07  3860.9  526.94  3910.4  526.50  4355.9  514.13
  4511.4  511.05  4546.8  511.64  4568.0  509.70  4836.7  503.85  4872.1  504.21
  4964.3  501.93  4995.1  501.88  5002.3  501.80  5003.0  501.00  5009.8  501.00
  5010.5  501.80  5416.6  504.83  5543.9  507.72  5713.6  513.29  5847.9  515.47
  6144.9  513.07  6152.0  512.11  6166.1  512.01  6173.2  512.92  6258.0  513.59
  6349.9  515.85  6491.3  520.12  6526.7  521.97  6717.6  527.13  6751.0  528.94
#Mann=5,-1,0
  3812.3     0.1       0  4964.3    0.12       0  4995.1     0.1       0
  5002.3    0.07       0  5010.5     0.1       0
Bank Sta=5002.3,5010.5
Exp/Cntr=0.3,0.1

Type RM Length L Ch R = 1,14673,462,462,462
BEGIN DESCRIPTION:
UNT 024 in RCW 18.0
END DESCRIPTION:
XS GIS Cut Line= 3
      1983221.86     13467725.03      1982725.00     13467075.00
      1981524.97     13465974.97
#Sta/Elev= 30
  4199.9  523.67  4289.8  523.84  4354.2  522.18  4489.4  517.45  4647.2  508.07
  4840.4  502.45  4971.4  500.65  4972.1  499.85  4978.9  499.85  4979.6  500.65
  5006.0  500.71  5033.5  500.73  5145.4  502.44  5329.8  501.86  5471.0  505.73
  5556.1  509.83  5562.9  509.23  5612.8  511.81  5655.4  512.49  5782.4  509.89
  5945.2  508.30  6164.7  512.26  6242.2  515.48  6393.2  521.28  6433.5  523.20
  6455.1  522.78  6476.1  524.56  6490.3  523.90  6539.6  529.11  6646.0  532.97
#Mann=7,-1,0
  4199.9     0.1       0  4971.4    0.07       0  4979.6     0.1       0
  5006.0    0.07       0  5033.5     0.1       0  6242.2    0.05       0
  6393.2     0.1       0
Bank Sta=4971.4,4979.6
Exp/Cntr=0.3,0.1

Type RM Length L Ch R = 1,14211,474,474,474
BEGIN DESCRIPTION:
UNT 024 in RCW 17.0
END DESCRIPTION:
XS GIS Cut Line= 3
      1983851.21     13467781.47      1983075.00     13466825.00
      1982274.98     13466024.98
#Sta/Elev= 30
  3753.4  522.74  3854.4  520.28  3897.6  519.87  3932.7  518.62  3954.9  518.68
  4060.6  516.47  4138.9  514.36  4167.7  514.23  4309.9  510.57  4394.7  509.64
  4580.0  505.19  4608.8  505.10  4701.5  502.99  4792.6  501.69  4885.3  501.32
  4893.3  500.58  4899.7  500.95  4914.1  500.36  5032.5  499.80  5051.8  499.73
  5052.5  498.93  5059.3  498.93  5060.1  499.73  5112.5  500.37  5367.0  501.13
  5777.2  504.64  5904.4  507.18  6078.8  513.49  6102.4  514.94  6116.6  515.11
#Mann=5,-1,0
  3753.4     0.1       0  5032.5    0.12       0  5051.8    0.07       0
  5060.1    0.12       0  6078.8    0.05       0
Bank Sta=5051.8,5060.1
Exp/Cntr=0.3,0.1

Type RM Length L Ch R = 1,13737,715,715,715
BEGIN DESCRIPTION:
UNT 024 in RCW 16.0
END DESCRIPTION:
XS GIS Cut Line= 3
      1984225.03     13467175.02      1983425.00     13466575.00
      1982625.02     13465825.02
#Sta/Elev= 30
  4025.2  523.53  4067.9  522.41  4132.5  518.67  4332.5  512.43  4353.4  512.21
  4385.8  510.60  4417.9  509.38  4467.9  508.78  4561.7  505.65  4567.9  505.96
  4575.2  505.13  4638.8  503.12  4717.9  501.60  4888.8  499.15  5017.8  499.09
  5018.6  498.29  5025.7  498.29  5026.4  499.09  5128.7  499.21  5156.7  499.32
  5350.8  500.57  5492.0  502.47  5506.1  503.16  5520.3  502.50  5541.8  502.50
  5619.5  504.45  5846.1  506.58  6004.7  510.60  6093.7  513.36  6121.8  514.77
#Mann=7,-1,0
  4025.2    0.05       0  4385.8     0.1       0  5017.8    0.07       0
  5026.4     0.1       0  5128.7    0.07       0  5156.7     0.1       0
  6004.7    0.05       0
Bank Sta=5017.8,5026.4
Exp/Cntr=0.3,0.1

Type RM Length L Ch R = 1,13022,266,266,266
BEGIN DESCRIPTION:
UNT 024 in RCW 15.0
END DESCRIPTION:
XS GIS Cut Line= 3
      1984276.24     13466919.86      1983911.67     13465998.00
      1982574.99     13465725.00
#Sta/Elev= 30
  4316.8  514.42  4429.6  510.26  4444.1  509.03  4461.8  504.96  4468.5  504.54
  4553.8  504.18  4725.6  503.27  4768.6  502.36  4859.7  502.07  4870.5  500.68
  4876.7  498.73  4882.1  499.92  4892.0  500.50  4924.2  498.85  4930.8  497.43
  5088.7  497.27  5089.5  496.47  5096.6  496.47  5097.4  497.27  5176.8  498.50
  5529.3  499.26  5652.4  500.54  5764.0  502.51  5919.9  506.49  6090.6  509.84
  6192.5  509.79  6305.0  509.18  6415.7  510.62  6500.7  512.15  6672.4  517.73
#Mann=8,-1,0
  4316.8     0.1       0  4553.8    0.05       0  4725.6     0.1       0
  5088.7    0.07       0  5097.4     0.1       0  5919.9    0.05       0
  6192.5     0.1       0  6415.7    0.05       0
Bank Sta=5088.7,5097.4
Exp/Cntr=0.3,0.1

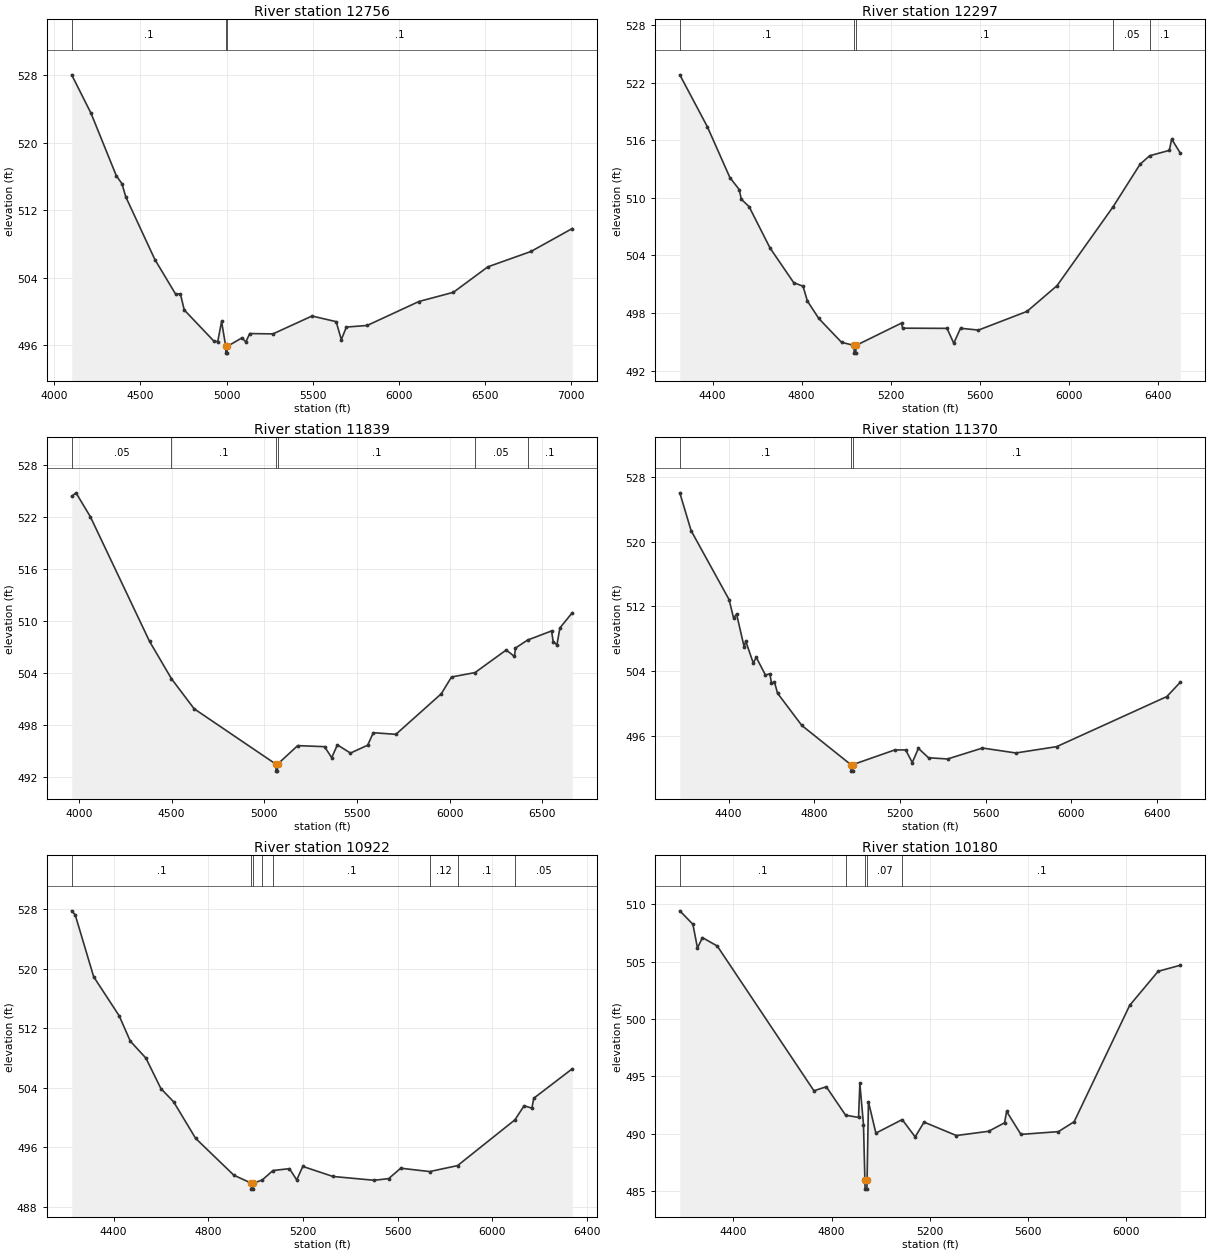
Type RM Length L Ch R = 1,12756,459,459,459
BEGIN DESCRIPTION:
UNT 024 in RCW 14.0
END DESCRIPTION:
XS GIS Cut Line= 3
      1984674.99     13467024.98      1984074.86     13465848.70
      1984047.08     13464265.37
#Sta/Elev= 30
  4101.4  528.05  4213.6  523.49  4359.8  516.11  4393.0  515.14  4415.3  513.58
  4584.1  506.15  4704.2  502.06  4732.1  502.08  4754.3  500.18  4926.5  496.48
  4948.7  496.43  4971.0  498.81  4995.1  495.86  4995.9  495.06  5003.0  495.06
  5003.8  495.86  5089.3  496.87  5111.7  496.39  5134.2  497.38  5268.9  497.34
  5495.6  499.46  5635.7  498.79  5665.7  496.66  5694.9  498.15  5815.7  498.34
  6115.7  501.18  6315.8  502.27  6515.8  505.29  6765.8  507.11  7005.5  509.83
#Mann=3,-1,0
  4101.4     0.1       0  4995.1    0.07       0  5003.8     0.1       0
Bank Sta=4995.1,5003.8
Exp/Cntr=0.3,0.1

Type RM Length L Ch R = 1,12297,458,458,458
BEGIN DESCRIPTION:
UNT 024 in RCW 13.0
END DESCRIPTION:
XS GIS Cut Line= 3
      1984824.99     13466824.97      1984675.00     13466125.00
      1984484.58     13464605.64
#Sta/Elev= 30
  4253.1  522.80  4376.6  517.40  4478.1  512.09  4519.8  510.85  4529.2  509.84
  4564.1  509.07  4657.9  504.77  4764.4  501.15  4806.2  500.78  4825.8  499.24
  4876.9  497.42  4979.0  494.94  5035.2  494.61  5035.9  493.81  5043.1  493.81
  5043.9  494.61  5248.3  496.94  5253.3  496.41  5452.7  496.39  5482.9  494.84
  5513.2  496.40  5593.8  496.21  5811.9  498.16  5946.5  500.84  6197.9  509.05
  6319.4  513.49  6362.1  514.37  6450.5  514.93  6461.1  516.11  6500.2  514.63
#Mann=5,-1,0
  4253.1     0.1       0  5035.2    0.07       0  5043.9     0.1       0
  6197.9    0.05       0  6362.1     0.1       0
Bank Sta=5035.2,5043.9
Exp/Cntr=0.3,0.1

Type RM Length L Ch R = 1,11839,469,469,469
BEGIN DESCRIPTION:
UNT 024 in RCW 12.0
END DESCRIPTION:
XS GIS Cut Line= 3
      1985817.95     13466584.84      1984922.08     13465779.25
      1984616.53     13464313.97
#Sta/Elev= 30
  3960.9  524.40  3984.1  524.80  4061.8  522.04  4381.0  507.68  4499.4  503.37
  4621.6  499.91  5063.2  493.52  5064.0  492.72  5071.2  492.72  5072.0  493.52
  5180.6  495.66  5325.6  495.54  5364.1  494.27  5394.8  495.75  5465.5  494.80
  5558.2  495.71  5588.9  497.15  5710.5  496.96  5955.6  501.64  6010.7  503.57
  6137.6  504.08  6305.8  506.68  6350.7  505.94  6355.8  506.91  6421.4  507.83
  6550.8  508.88  6559.3  507.66  6579.7  507.27  6595.8  509.23  6662.5  510.98
#Mann=6,-1,0
  3960.9    0.05       0  4499.4     0.1       0  5063.2    0.07       0
  5072.0     0.1       0  6137.6    0.05       0  6421.4     0.1       0
Bank Sta=5063.2,5072
Exp/Cntr=0.3,0.1

Type RM Length L Ch R = 1,11370,448,448,448
BEGIN DESCRIPTION:
UNT 024 in RCW 11.0
END DESCRIPTION:
XS GIS Cut Line= 3
      1986033.18     13466251.46      1985425.00     13465675.00
      1985075.25     13464218.36
#Sta/Elev= 30
  4172.6  526.02  4225.2  521.36  4402.4  512.85  4423.4  510.58  4437.6  511.05
  4473.2  506.96  4480.0  507.74  4515.2  505.03  4529.4  505.72  4571.9  503.55
  4593.3  503.69  4600.2  502.53  4614.3  502.69  4628.5  501.30  4741.8  497.32
  4970.8  492.48  4971.6  491.68  4978.8  491.68  4979.6  492.48  5175.1  494.29
  5226.5  494.30  5257.4  492.74  5286.0  494.49  5333.2  493.33  5422.3  493.18
  5585.1  494.53  5740.7  493.92  5931.2  494.70  6445.3  500.88  6508.6  502.66
#Mann=3,-1,0
  4172.6     0.1       0  4970.8    0.07       0  4979.6     0.1       0
Bank Sta=4970.8,4979.6
Exp/Cntr=0.3,0.1

Type RM Length L Ch R = 1,10922,742,742,742
BEGIN DESCRIPTION:
UNT 024 in RCW 10.0
END DESCRIPTION:
XS GIS Cut Line= 3
      1986125.00     13466225.01      1985825.00     13465475.00
      1985554.02     13464195.87
#Sta/Elev= 30
  4223.2  527.79  4238.0  527.26  4316.1  518.93  4423.8  513.69  4470.9  510.28
  4536.9  508.00  4600.2  503.91  4654.0  502.13  4746.9  497.22  4908.5  492.27
  4982.2  491.20  4983.0  490.40  4990.2  490.40  4991.0  491.20  5028.1  491.62
  5073.7  492.90  5143.4  493.15  5174.1  491.64  5199.8  493.45  5327.4  492.10
  5501.2  491.59  5562.5  491.81  5613.6  493.21  5736.1  492.76  5853.8  493.56
  6096.2  499.71  6135.0  501.60  6167.8  501.28  6175.8  502.61  6338.5  506.57
#Mann=8,-1,0
  4223.2     0.1       0  4982.2    0.07       0  4991.0     0.1       0
  5028.1    0.12       0  5073.7     0.1       0  5736.1    0.12       0
  5853.8     0.1       0  6096.2    0.05       0
Bank Sta=4982.2,4991
Exp/Cntr=0.3,0.1

Type RM Length L Ch R = 1,10180,67,67,67
BEGIN DESCRIPTION:
UNT 024 in RCW 9.0
END DESCRIPTION:
XS GIS Cut Line= 3
      1986616.53     13466036.23      1986498.47     13465147.31
      1985901.27     13464175.11
#Sta/Elev= 30
  4182.0  509.43  4235.2  508.26  4253.9  506.19  4274.0  507.10  4334.6  506.36
  4728.0  493.75  4778.4  494.10  4857.0  491.62  4909.6  491.43  4914.9  494.39
  4929.7  490.81  4935.4  485.98  4936.2  485.18  4943.5  485.18  4944.3  485.98
  4949.9  492.79  4980.2  490.06  5087.3  491.24  5140.1  489.73  5176.3  491.02
  5307.7  489.85  5439.1  490.22  5503.9  490.96  5512.5  491.95  5570.5  489.95
  5723.2  490.19  5787.1  491.05  6013.2  501.19  6129.2  504.16  6219.7  504.69
#Mann=5,-1,0
  4182.0     0.1       0  4857.0    0.07       0  4935.4    0.07       0
  4944.3    0.07       0  5087.3     0.1       0
Bank Sta=4935.4,4944.3
Exp/Cntr=0.3,0.1