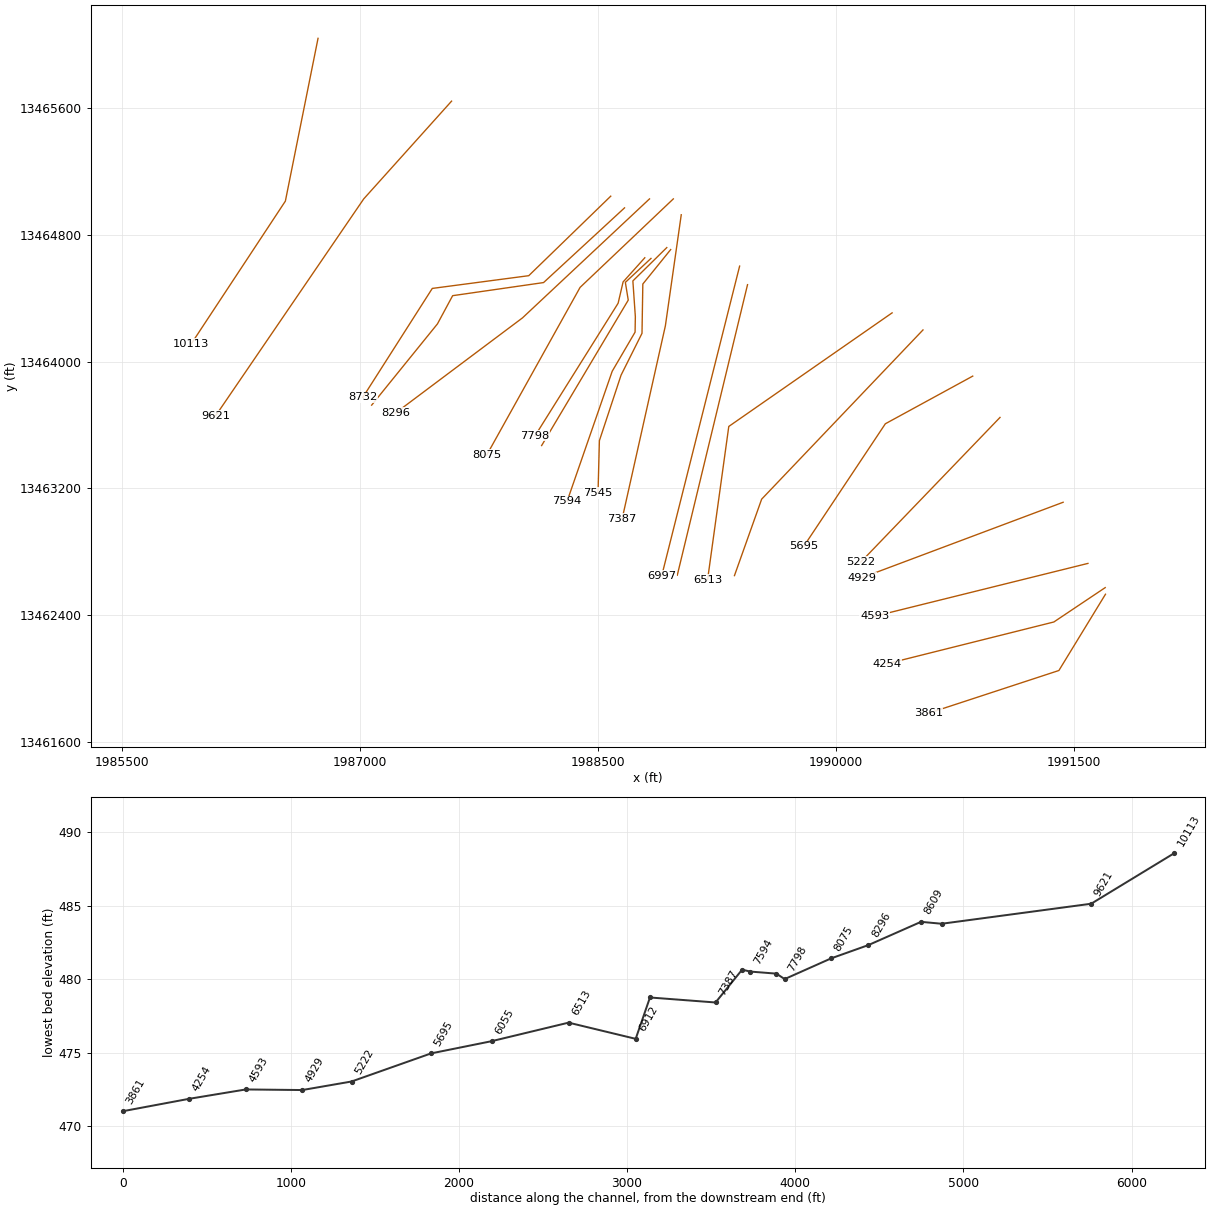
HEC-RAS study UNT 024 in RCW.prj: UNT 024 in RCW Base Level Engineering

--- UNT 024 in RCW.g01 (geometry) --- (continued)

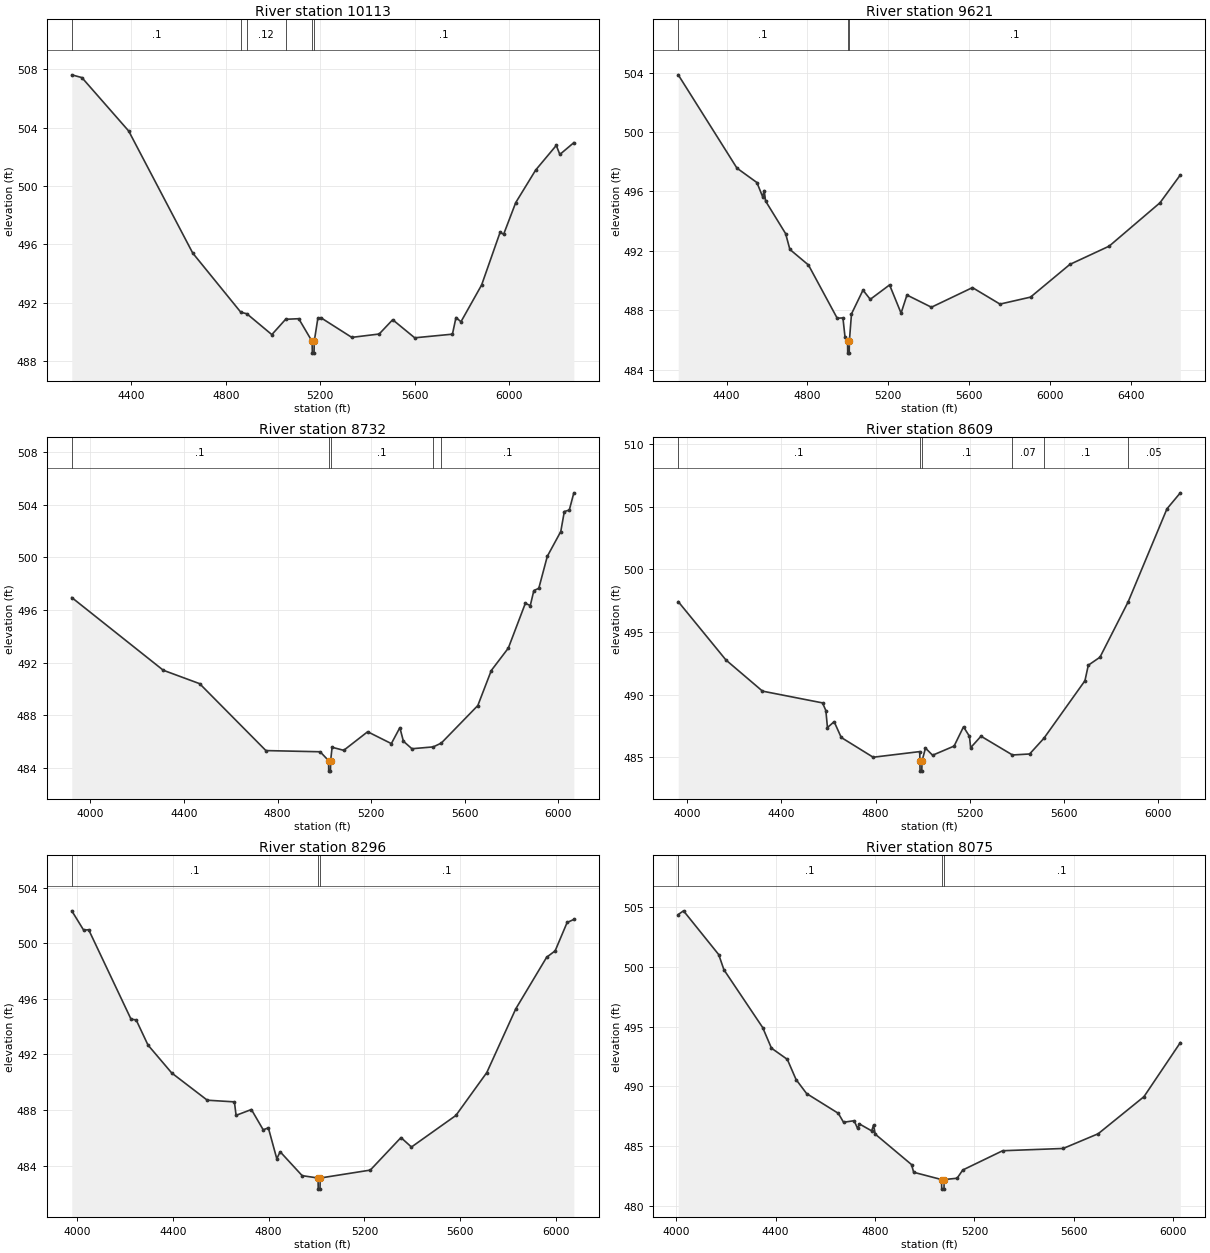
Type RM Length L Ch R = 1,10113,492,492,492
BEGIN DESCRIPTION:
UNT 024 in RCW 8.0
END DESCRIPTION:
XS GIS Cut Line= 3
      1986737.19     13466037.10      1986531.46     13465011.02
      1985937.70     13464109.96
#Sta/Elev= 30
  4147.9  507.62  4190.8  507.43  4388.8  503.77  4660.0  495.40  4863.7  491.34
  4889.0  491.24  4994.9  489.81  5053.3  490.86  5108.8  490.90  5165.5  489.34
  5166.3  488.54  5173.6  488.54  5174.4  489.34  5189.8  490.94  5202.3  490.97
  5333.3  489.62  5449.3  489.85  5506.5  490.83  5599.8  489.59  5759.5  489.84
  5774.5  490.98  5795.6  490.69  5883.0  493.21  5961.2  496.82  5976.3  496.69
  6027.5  498.86  6111.8  501.09  6199.1  502.78  6214.2  502.16  6273.5  502.97
#Mann=6,-1,0
  4147.9     0.1       0  4863.7    0.07       0  4889.0    0.12       0
  5053.3     0.1       0  5165.5    0.07       0  5174.4     0.1       0
Bank Sta=5165.5,5174.4
Exp/Cntr=0.3,0.1

Type RM Length L Ch R = 1,9621,889,889,889
BEGIN DESCRIPTION:
UNT 024 in RCW 7.0
END DESCRIPTION:
XS GIS Cut Line= 3
      1987578.36     13465641.27      1987025.00     13465025.00
      1986092.43     13463658.43
#Sta/Elev= 30
  4161.2  503.85  4451.6  497.57  4550.3  496.60  4578.7  495.64  4586.2  496.06
  4592.9  495.36  4692.3  493.16  4713.2  492.10  4805.2  491.05  4947.2  487.47
  4975.6  487.49  4986.1  486.18  4998.5  485.92  4999.3  485.12  5006.6  485.12
  5007.4  485.92  5017.9  487.76  5074.8  489.36  5110.7  488.74  5206.3  489.71
  5263.1  487.81  5292.1  489.03  5413.2  488.21  5616.1  489.53  5752.2  488.42
  5903.3  488.89  6097.7  491.09  6292.1  492.32  6543.5  495.24  6643.9  497.11
#Mann=3,-1,0
  4161.2     0.1       0  4998.5    0.07       0  5007.4     0.1       0
Bank Sta=4998.5,5007.4
Exp/Cntr=0.3,0.1

Type RM Length L Ch R = 1,8732,123,123,123
BEGIN DESCRIPTION:
UNT 024 in RCW 6.0
END DESCRIPTION:
XS GIS Cut Line= 4
      1988580.90     13465042.24      1988064.44     13464540.97
      1987456.81     13464460.68      1987019.23     13463773.99
#Sta/Elev= 30
  3920.2  496.94  4311.4  491.42  4467.0  490.40  4750.3  485.32  4982.3  485.23
  5018.2  484.56  5019.0  483.76  5026.3  483.76  5027.2  484.56  5033.4  485.57
  5083.2  485.34  5185.4  486.75  5286.7  485.85  5323.1  487.06  5338.3  486.03
  5374.7  485.46  5465.9  485.60  5500.4  485.89  5656.5  488.74  5714.1  491.40
  5786.9  493.10  5859.7  496.50  5880.8  496.33  5896.1  497.47  5917.2  497.64
  5953.6  500.07  6011.2  501.95  6026.4  503.47  6047.6  503.58  6067.1  504.89
#Mann=5,-1,0
  3920.2     0.1       0  5018.2    0.07       0  5027.2     0.1       0
  5465.9    0.07       0  5500.4     0.1       0
Bank Sta=5018.2,5027.2
Exp/Cntr=0.3,0.1

Type RM Length L Ch R = 1,8609,313,313,313
BEGIN DESCRIPTION:
UNT 024 in RCW 5.0
END DESCRIPTION:
XS GIS Cut Line= 5
      1988667.73     13464968.48      1988157.76     13464497.57
      1987585.09     13464414.97      1987489.36     13464237.15
      1987074.98     13463724.98
#Sta/Elev= 30
  3961.5  497.43  4164.1  492.77  4319.5  490.28  4574.6  489.34  4588.8  488.73
  4595.6  487.37  4624.0  487.84  4654.1  486.58  4789.8  485.00  4987.8  485.45
  4988.4  484.69  4989.2  483.89  4996.5  483.89  4997.4  484.69  5012.0  485.73
  5042.4  485.16  5133.7  485.89  5173.7  487.43  5199.0  486.67  5204.0  485.76
  5248.1  486.68  5381.8  485.18  5454.7  485.26  5515.2  486.51  5689.7  491.11
  5704.0  492.35  5753.6  492.99  5873.3  497.41  6038.2  504.84  6095.0  506.12
#Mann=6,-1,0
  3961.5     0.1       0  4988.4    0.07       0  4997.4     0.1       0
  5381.8    0.07       0  5515.2     0.1       0  5873.3    0.05       0
Bank Sta=4988.4,4997.4
Exp/Cntr=0.3,0.1

Type RM Length L Ch R = 1,8296,221,221,221
BEGIN DESCRIPTION:
UNT 024 in RCW 4.0
END DESCRIPTION:
XS GIS Cut Line= 3
      1988825.03     13465025.03      1988025.00     13464275.00
      1987225.02     13463675.01
#Sta/Elev= 30
  3977.9  502.34  4027.5  500.95  4048.5  500.98  4225.4  494.54  4246.8  494.49
  4296.2  492.68  4395.3  490.67  4543.8  488.71  4657.1  488.59  4664.0  487.62
  4728.0  488.04  4777.3  486.58  4798.8  486.72  4834.0  484.50  4848.1  485.00
  4940.0  483.28  5006.3  483.11  5007.1  482.31  5014.4  482.31  5015.3  483.11
  5224.5  483.68  5352.6  486.02  5396.4  485.34  5581.8  487.61  5711.0  490.70
  5831.8  495.28  5961.0  499.00  5996.4  499.46  6046.4  501.50  6074.5  501.72
#Mann=3,-1,0
  3977.9     0.1       0  5006.3    0.07       0  5015.3     0.1       0
Bank Sta=5006.3,5015.3
Exp/Cntr=0.3,0.1

Type RM Length L Ch R = 1,8075,277,277,277
BEGIN DESCRIPTION:
UNT 024 in RCW 3.0
END DESCRIPTION:
XS GIS Cut Line= 3
      1988975.00     13465025.00      1988387.79     13464467.19
      1987799.82     13463410.58
#Sta/Elev= 30
  4008.7  504.37  4029.9  504.68  4171.5  501.02  4192.5  499.75  4348.3  494.92
  4383.5  493.20  4447.4  492.26  4482.6  490.57  4525.0  489.40  4652.4  487.75
  4673.5  487.00  4716.0  487.13  4730.1  486.48  4737.4  486.86  4786.7  486.28
  4794.0  486.76  4800.9  486.01  4947.0  483.46  4955.4  482.82  5067.5  482.21
  5068.3  481.41  5077.4  481.41  5078.2  482.21  5130.1  482.32  5153.0  483.01
  5313.3  484.62  5556.8  484.81  5697.5  486.04  5881.6  489.14  6027.8  493.66
#Mann=3,-1,0
  4008.7     0.1       0  5067.5    0.07       0  5078.2     0.1       0
Bank Sta=5067.5,5078.2
Exp/Cntr=0.3,0.1

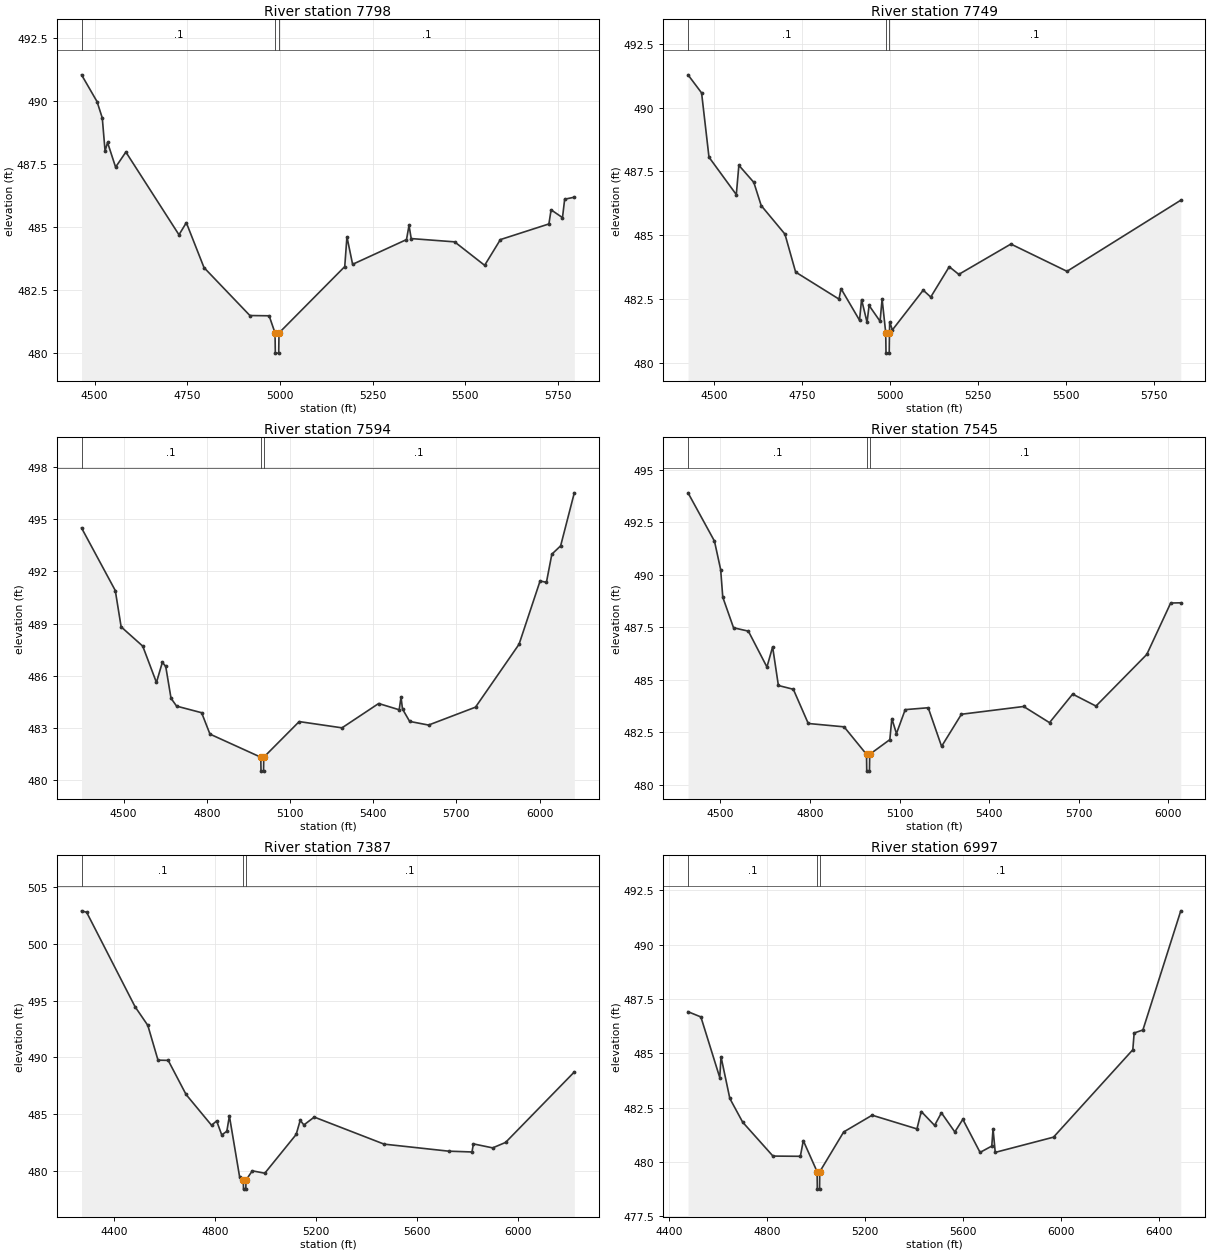
Type RM Length L Ch R = 1,7798,49,49,49
BEGIN DESCRIPTION:
Mapping XS cbee0c2d
END DESCRIPTION:
XS GIS Cut Line= 4
      1988795.37     13464653.85      1988658.63     13464501.48
      1988627.38     13464367.36      1988103.96     13463531.46
#Sta/Elev= 30
  4465.0  491.03  4506.7  489.97  4520.9  489.32  4528.4  488.01  4535.1  488.35
  4556.8  487.37  4584.5  487.97  4727.7  484.69  4747.5  485.17  4795.2  483.39
  4918.9  481.49  4970.8  481.48  4986.7  480.80  4987.5  480.00  4996.6  480.00
  4997.4  480.80  5174.7  483.43  5180.6  484.61  5195.9  483.52  5341.2  484.50
  5348.0  485.06  5353.9  484.54  5471.0  484.41  5551.9  483.48  5594.4  484.50
  5725.2  485.12  5731.1  485.68  5761.8  485.37  5767.7  486.10  5793.7  486.18
#Mann=3,-1,0
  4465.0     0.1       0  4986.7    0.07       0  4997.4     0.1       0
Bank Sta=4986.7,4997.4
Exp/Cntr=0.3,0.1

Type RM Length L Ch R = 1,7749,155,155,155
BEGIN DESCRIPTION:
Mapping XS 08d25d92
END DESCRIPTION:
XS GIS Cut Line= 4
      1988834.38     13464649.89      1988672.95     13464498.87
      1988691.18     13464386.89      1988145.63     13463470.27
#Sta/Elev= 30
  4426.2  491.29  4464.8  490.58  4485.8  488.06  4563.5  486.59  4570.8  487.74
  4613.3  487.07  4634.3  486.16  4701.8  485.04  4732.2  483.55  4855.5  482.49
  4861.3  482.90  4913.9  481.66  4919.7  482.47  4935.3  481.58  4941.1  482.24
  4972.3  481.62  4978.1  482.49  4988.4  481.17  4989.2  480.37  4998.3  480.37
  4999.1  481.17  4999.6  481.60  5007.3  481.28  5095.0  482.84  5116.4  482.57
  5169.0  483.76  5196.2  483.46  5344.3  484.65  5503.9  483.58  5827.4  486.37
#Mann=3,-1,0
  4426.2     0.1       0  4988.4    0.07       0  4999.1     0.1       0
Bank Sta=4988.4,4999.1
Exp/Cntr=0.3,0.1

Type RM Length L Ch R = 1,7594,49,49,49
BEGIN DESCRIPTION:
Mapping XS 24b8e1c0
END DESCRIPTION:
XS GIS Cut Line= 6
      1988933.80     13464718.05      1988720.26     13464507.99
      1988735.88     13464282.29      1988734.15     13464185.07
      1988590.05     13463938.54      1988305.94     13463118.43
#Sta/Elev= 30
  4348.5  494.50  4470.1  490.90  4491.2  488.81  4569.1  487.70  4618.5  485.61
  4639.8  486.77  4652.0  486.53  4671.1  484.70  4691.1  484.25  4781.4  483.87
  4811.4  482.64  4994.7  481.31  4995.5  480.51  5004.6  480.51  5005.4  481.31
  5133.1  483.36  5287.5  483.00  5419.6  484.40  5493.6  484.04  5500.3  484.76
  5505.6  484.08  5531.4  483.37  5599.5  483.16  5768.8  484.19  5925.8  487.81
  6001.6  491.45  6024.5  491.37  6044.0  492.99  6075.7  493.47  6125.0  496.52
#Mann=3,-1,0
  4348.5     0.1       0  4994.7    0.07       0  5005.4     0.1       0
Bank Sta=4994.7,5005.4
Exp/Cntr=0.3,0.1

Type RM Length L Ch R = 1,7545,158,158,158
BEGIN DESCRIPTION:
Mapping XS 8f60dcf7
END DESCRIPTION:
XS GIS Cut Line= 6
      1988958.32     13464705.47      1988782.98     13464488.45
      1988777.77     13464177.69      1988645.82     13463913.80
      1988509.42     13463501.07      1988500.74     13463171.22
#Sta/Elev= 30
  4391.7  493.90  4480.2  491.60  4501.0  490.24  4508.0  488.93  4544.1  487.47
  4593.7  487.31  4655.9  485.60  4674.9  486.56  4694.2  484.72  4744.2  484.54
  4794.2  482.91  4914.2  482.75  4989.2  481.44  4990.0  480.64  4999.1  480.64
  4999.9  481.44  5067.2  482.14  5074.0  483.14  5089.5  482.43  5118.7  483.57
  5195.7  483.66  5240.5  481.82  5306.9  483.35  5515.2  483.72  5601.8  482.95
  5679.2  484.31  5757.3  483.74  5927.4  486.20  6007.4  488.65  6041.2  488.66
#Mann=3,-1,0
  4391.7     0.1       0  4989.2    0.07       0  4999.9     0.1       0
Bank Sta=4989.2,4999.9
Exp/Cntr=0.3,0.1

Type RM Length L Ch R = 1,7387,390,390,390
BEGIN DESCRIPTION:
UNT 024 in RCW 2.0
END DESCRIPTION:
XS GIS Cut Line= 3
      1989025.00     13464924.99      1988925.00     13464225.00
      1988652.82     13463009.19
#Sta/Elev= 30
  4271.0  502.90  4291.2  502.77  4483.1  494.46  4533.6  492.82  4574.0  489.76
  4614.4  489.74  4685.2  486.74  4786.2  484.03  4806.4  484.41  4826.6  483.18
  4846.8  483.50  4856.9  484.85  4897.3  479.51  4912.1  479.21  4912.9  478.41
  4922.0  478.41  4922.8  479.21  4947.8  480.02  4997.2  479.81  5121.6  483.22
  5137.6  484.46  5152.3  484.06  5193.3  484.75  5470.0  482.37  5726.2  481.75
  5818.4  481.68  5824.2  482.39  5900.4  482.04  5951.6  482.52  6224.0  488.72
#Mann=3,-1,0
  4271.0     0.1       0  4912.1    0.07       0  4922.8     0.1       0
Bank Sta=4912.1,4922.8
Exp/Cntr=0.3,0.1

Type RM Length L Ch R = 1,6997,85,85,85
BEGIN DESCRIPTION:
Mapping XS 4b569310
END DESCRIPTION:
XS GIS Cut Line= 2
      1989392.68     13464601.37      1988902.22     13462650.37
#Sta/Elev= 30
  4477.4  486.91  4529.9  486.67  4607.0  483.88  4612.1  484.84  4648.1  482.92
  4700.5  481.83  4824.2  480.27  4936.0  480.26  4948.0  480.98  5004.5  479.55
  5005.3  478.75  5014.4  478.75  5015.2  479.55  5112.9  481.38  5229.1  482.15
  5412.0  481.52  5429.6  482.32  5484.1  481.68  5511.9  482.26  5566.6  481.38
  5599.3  481.96  5669.7  480.44  5717.5  480.73  5722.7  481.52  5731.6  480.44
  5969.5  481.14  6293.3  485.16  6298.7  485.93  6334.5  486.07  6489.1  491.55
#Mann=3,-1,0
  4477.4     0.1       0  5004.5    0.07       0  5015.2     0.1       0
Bank Sta=5004.5,5015.2
Exp/Cntr=0.3,0.1

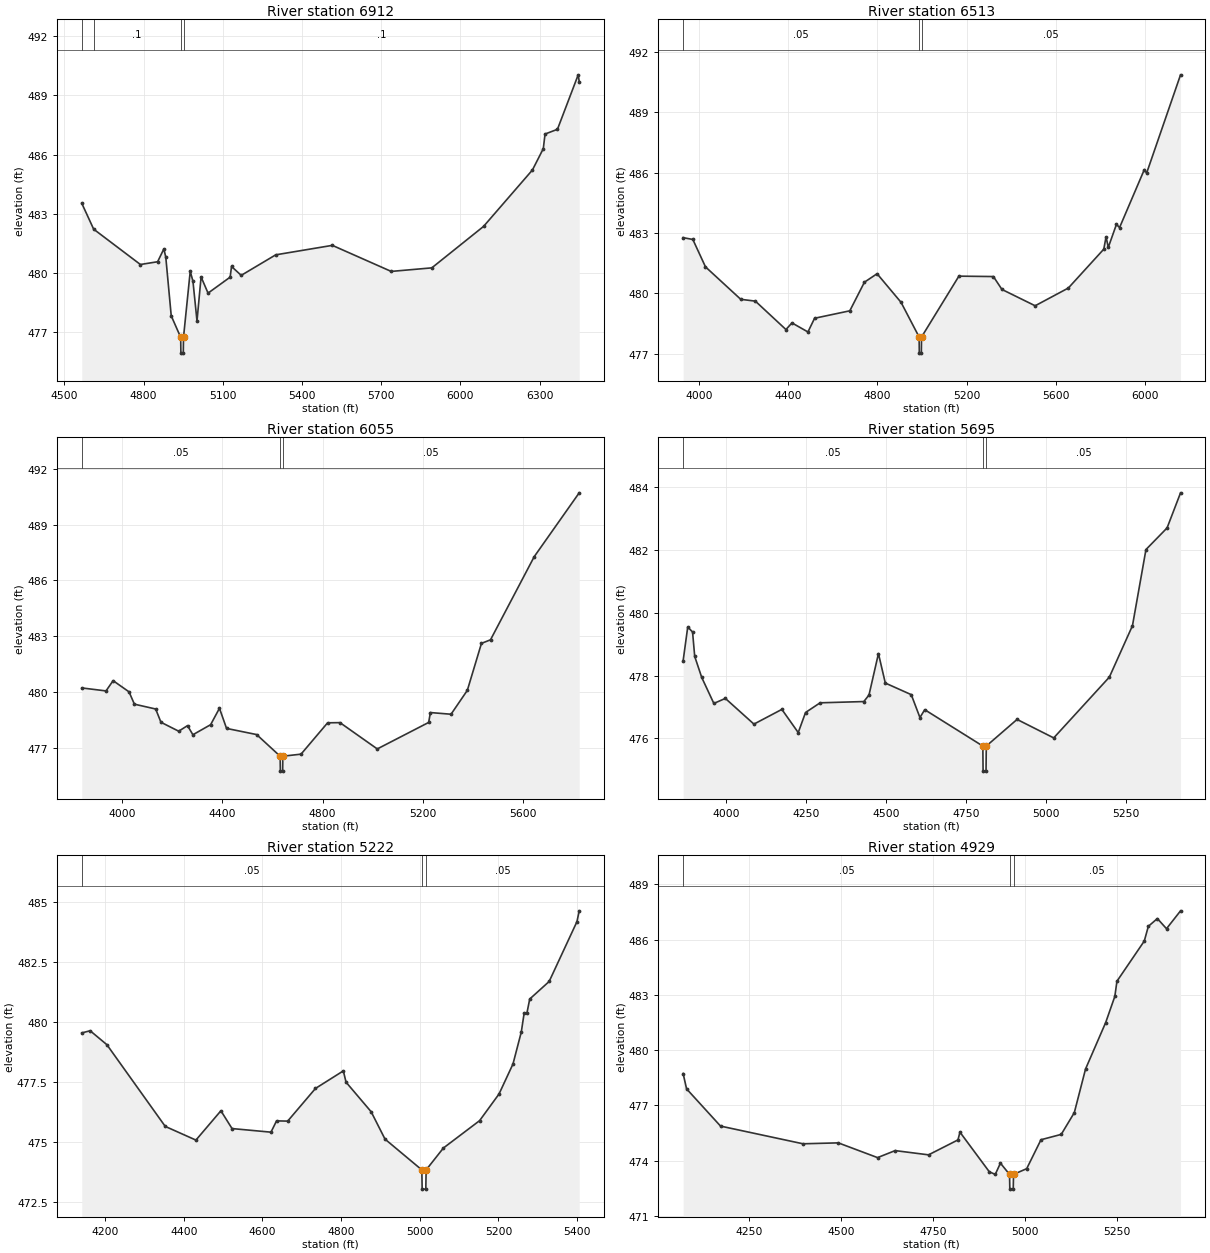
Type RM Length L Ch R = 1,6912,399,399,399
BEGIN DESCRIPTION:
Mapping XS 06d47ea6
END DESCRIPTION:
XS GIS Cut Line= 2
      1989442.49     13464484.31      1988999.94     13462652.82
#Sta/Elev= 30
  4565.7  483.53  4610.7  482.22  4787.7  480.43  4853.0  480.57  4876.6  481.22
  4883.9  480.80  4904.5  477.83  4940.3  476.74  4941.1  475.94  4950.2  475.94
  4951.0  476.74  4976.5  480.09  4986.8  479.58  5002.1  477.57  5017.6  479.80
  5044.0  478.98  5127.7  479.79  5132.9  480.33  5169.6  479.88  5300.3  480.92
  5514.8  481.40  5737.8  480.08  5891.6  480.26  6087.6  482.36  6272.8  485.22
  6313.9  486.30  6320.5  487.04  6367.5  487.28  6446.1  490.04  6449.9  489.70
#Mann=4,-1,0
  4565.7    0.05       0  4610.7     0.1       0  4940.3    0.07       0
  4951.0     0.1       0
Bank Sta=4940.3,4951
Exp/Cntr=0.3,0.1

Type RM Length L Ch R = 1,6513,458,458,458
BEGIN DESCRIPTION:
Mapping XS ad033643
END DESCRIPTION:
XS GIS Cut Line= 3
      1990353.16     13464306.62      1989324.40     13463590.65
      1989190.84     13462624.32
#Sta/Elev= 30
  3929.8  482.77  3973.3  482.68  4030.0  481.32  4188.0  479.71  4253.5  479.62
  4390.5  478.21  4417.5  478.54  4489.1  478.09  4518.8  478.77  4676.7  479.14
  4742.2  480.56  4798.9  480.98  4906.3  479.56  4987.3  477.84  4988.1  477.04
  4997.2  477.04  4998.1  477.84  5165.5  480.86  5320.1  480.84  5358.4  480.20
  5507.2  479.39  5655.9  480.27  5814.8  482.20  5824.9  482.81  5835.0  482.29
  5871.5  483.43  5885.4  483.27  5996.5  486.15  6006.6  485.97  6158.7  490.85
#Mann=3,-1,0
  3929.8    0.05       0  4987.3    0.03       0  4998.1    0.05       0
Bank Sta=4987.3,4998.1
Exp/Cntr=0.3,0.1

Type RM Length L Ch R = 1,6055,360,360,360
BEGIN DESCRIPTION:
Mapping XS 0e4a8328
END DESCRIPTION:
XS GIS Cut Line= 3
      1990547.62     13464198.99      1989531.37     13463132.23
      1989360.13     13462650.40
#Sta/Elev= 30
  3839.1  480.24  3935.8  480.08  3964.1  480.63  4027.6  480.03  4049.0  479.37
  4133.9  479.11  4155.0  478.40  4225.8  477.92  4261.0  478.22  4282.4  477.73
  4353.2  478.27  4388.4  479.15  4416.7  478.07  4536.8  477.74  4630.5  476.58
  4631.4  475.78  4640.5  475.78  4641.3  476.58  4713.9  476.69  4819.9  478.37
  4869.3  478.38  5018.1  476.97  5223.1  478.39  5230.1  478.92  5312.4  478.83
  5377.4  480.11  5433.8  482.63  5469.9  482.82  5644.4  487.28  5823.8  490.70
#Mann=3,-1,0
  3839.1    0.05       0  4630.5    0.03       0  4641.3    0.05       0
Bank Sta=4630.5,4641.3
Exp/Cntr=0.3,0.1

Type RM Length L Ch R = 1,5695,473,473,473
BEGIN DESCRIPTION:
Mapping XS 3d3b3045
END DESCRIPTION:
XS GIS Cut Line= 3
      1990860.87     13463907.86      1990310.54     13463607.52
      1989796.66     13462834.97
#Sta/Elev= 30
  3866.2  478.47  3880.6  479.55  3895.7  479.39  3902.4  478.61  3924.3  477.94
  3962.2  477.11  3998.2  477.27  4087.5  476.45  4174.8  476.92  4226.0  476.18
  4248.8  476.82  4294.4  477.13  4431.1  477.17  4447.2  477.38  4476.7  478.70
  4498.2  477.76  4579.3  477.39  4606.4  476.66  4621.4  476.91  4803.0  475.75
  4803.8  474.95  4813.0  474.95  4813.8  475.75  4910.0  476.60  5024.6  476.01
  5198.5  477.95  5270.7  479.59  5312.9  482.02  5378.9  482.71  5421.0  483.83
#Mann=3,-1,0
  3866.2    0.05       0  4803.0    0.03       0  4813.8    0.05       0
Bank Sta=4803,4813.8
Exp/Cntr=0.3,0.1

Type RM Length L Ch R = 1,5222,293,293,293
BEGIN DESCRIPTION:
Mapping XS 4b7780db
END DESCRIPTION:
XS GIS Cut Line= 2
      1991032.75     13463647.45      1990156.00     13462735.98
#Sta/Elev= 30
  4140.8  479.54  4162.1  479.63  4204.6  479.05  4353.0  475.65  4431.0  475.08
  4494.5  476.30  4522.8  475.56  4621.8  475.41  4636.0  475.88  4664.3  475.87
  4735.0  477.23  4805.8  477.96  4812.7  477.49  4876.5  476.26  4911.8  475.12
  5005.4  473.84  5006.2  473.04  5015.5  473.04  5016.3  473.84  5060.2  474.75
  5152.3  475.89  5201.7  477.00  5237.2  478.25  5258.3  479.58  5265.5  480.36
  5272.5  480.36  5279.7  480.95  5329.1  481.68  5399.8  484.17  5405.5  484.62
#Mann=3,-1,0
  4140.8    0.05       0  5005.4   0.035       0  5016.3    0.05       0
Bank Sta=5005.4,5016.3
Exp/Cntr=0.3,0.1

Type RM Length L Ch R = 1,4929,336,336,336
BEGIN DESCRIPTION:
Mapping XS 86ed7194
END DESCRIPTION:
XS GIS Cut Line= 2
      1991430.35     13463112.74      1990162.98     13462637.04
#Sta/Elev= 30
  4069.8  478.73  4079.2  477.90  4171.6  475.88  4396.0  474.92  4492.1  474.97
  4598.9  474.17  4646.8  474.55  4737.7  474.32  4817.7  475.13  4823.2  475.55
  4903.1  473.40  4919.3  473.26  4933.3  473.87  4958.1  473.26  4958.9  472.46
  4968.2  472.46  4969.0  473.26  5004.8  473.57  5043.7  475.14  5098.8  475.43
  5134.4  476.61  5165.0  478.98  5219.8  481.50  5244.7  482.92  5250.4  483.74
  5324.8  485.92  5335.9  486.72  5360.4  487.14  5385.3  486.59  5423.5  487.56
#Mann=3,-1,0
  4069.8    0.05       0  4958.1   0.035       0  4969.0    0.05       0
Bank Sta=4958.1,4969
Exp/Cntr=0.3,0.1

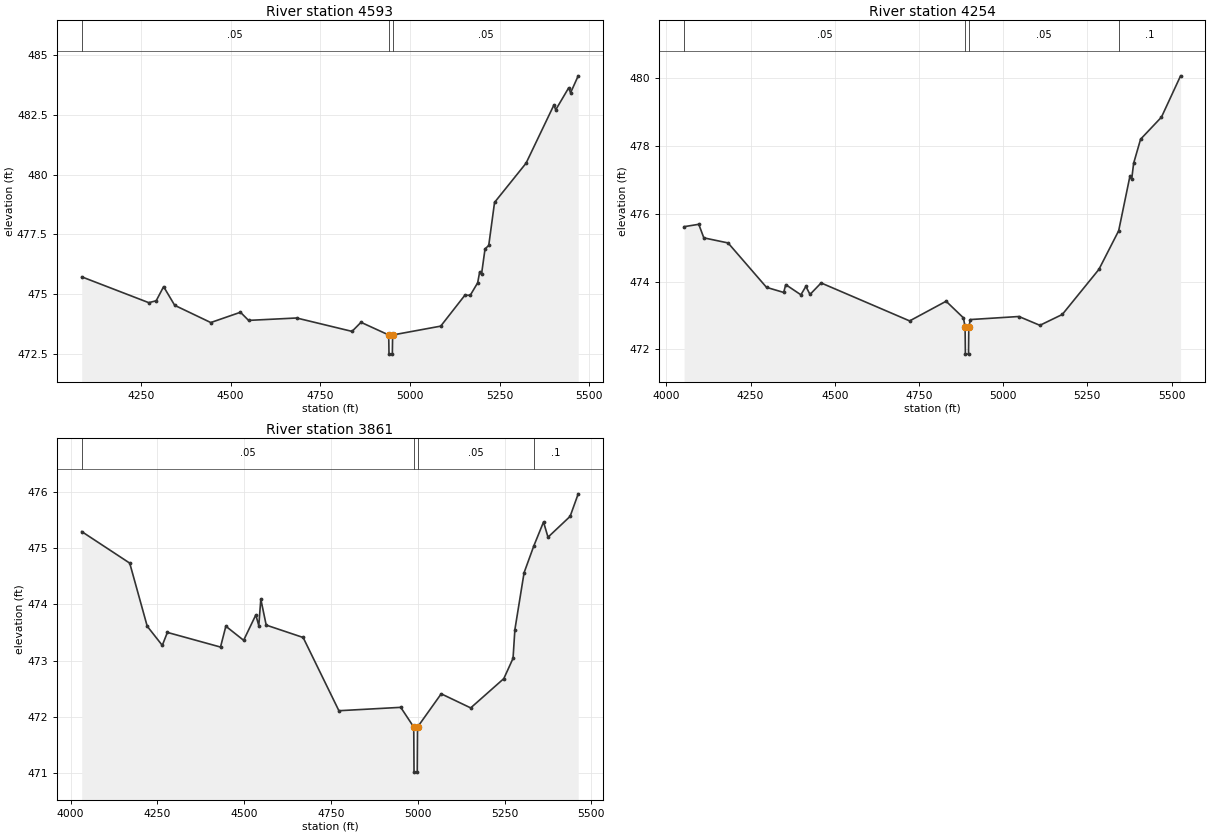
Type RM Length L Ch R = 1,4593,339,339,339
BEGIN DESCRIPTION:
Mapping XS b2df97b1
END DESCRIPTION:
XS GIS Cut Line= 2
      1991586.54     13462727.30      1990242.86     13462393.99
#Sta/Elev= 30
  4084.9  475.73  4271.9  474.65  4292.5  474.73  4313.2  475.32  4344.1  474.54
  4444.7  473.82  4527.5  474.25  4550.1  473.91  4684.1  474.01  4838.6  473.45
  4863.6  473.83  4940.9  473.30  4941.7  472.50  4951.0  472.50  4951.8  473.30
  5085.9  473.67  5153.2  474.96  5168.3  474.96  5188.9  475.48  5194.6  475.94
  5199.7  475.84  5209.5  476.90  5219.8  477.04  5236.0  478.84  5323.9  480.48
  5401.5  482.91  5406.6  482.71  5442.8  483.63  5448.0  483.42  5469.3  484.13
#Mann=3,-1,0
  4084.9    0.05       0  4940.9   0.035       0  4951.8    0.05       0
Bank Sta=4940.9,4951.8
Exp/Cntr=0.3,0.1

Type RM Length L Ch R = 1,4254,393,393,393
BEGIN DESCRIPTION:
Mapping XS 2ff8426c
END DESCRIPTION:
XS GIS Cut Line= 3
      1991695.36     13462574.69      1991371.91     13462358.10
      1990319.79     13462094.54
#Sta/Elev= 30
  4052.9  475.62  4096.4  475.69  4111.4  475.29  4183.4  475.14  4297.5  473.83
  4348.5  473.68  4354.6  473.91  4399.6  473.61  4414.4  473.86  4426.6  473.62
  4459.6  473.96  4722.4  472.84  4830.7  473.42  4882.1  472.93  4887.1  472.66
  4887.9  471.86  4897.2  471.86  4898.0  472.66  4902.9  472.88  5046.8  472.97
  5109.1  472.71  5175.6  473.03  5284.3  474.36  5343.0  475.50  5376.4  477.11
  5381.6  477.02  5387.4  477.49  5408.0  478.20  5469.9  478.85  5526.8  480.07
#Mann=4,-1,0
  4052.9    0.05       0  4887.1   0.035       0  4898.0    0.05       0
  5343.0     0.1       0
Bank Sta=4887.1,4898
Exp/Cntr=0.3,0.1

Type RM Length L Ch R = 1,3861,449,449,449
BEGIN DESCRIPTION:
Mapping XS 2868b7a7
END DESCRIPTION:
XS GIS Cut Line= 3
      1991697.08     13462532.99      1991403.65     13462052.27
      1990580.06     13461782.00
#Sta/Elev= 30
  4032.2  475.29  4170.4  474.73  4220.8  473.61  4264.2  473.27  4278.9  473.50
  4431.9  473.24  4447.3  473.61  4498.5  473.36  4533.6  473.81  4542.2  473.62
  4548.0  474.09  4563.5  473.63  4669.9  473.41  4772.9  472.11  4951.0  472.17
  4988.5  471.82  4989.3  471.02  4998.6  471.02  4999.4  471.82  5067.6  472.41
  5152.5  472.16  5247.9  472.68  5274.5  473.04  5279.8  473.55  5306.3  474.56
  5334.6  475.04  5362.3  475.46  5375.2  475.19  5438.9  475.56  5462.2  475.96
#Mann=4,-1,0
  4032.2    0.05       0  4988.5   0.035       0  4999.4    0.05       0
  5334.6     0.1       0
Bank Sta=4988.5,4999.4
Exp/Cntr=0.3,0.1