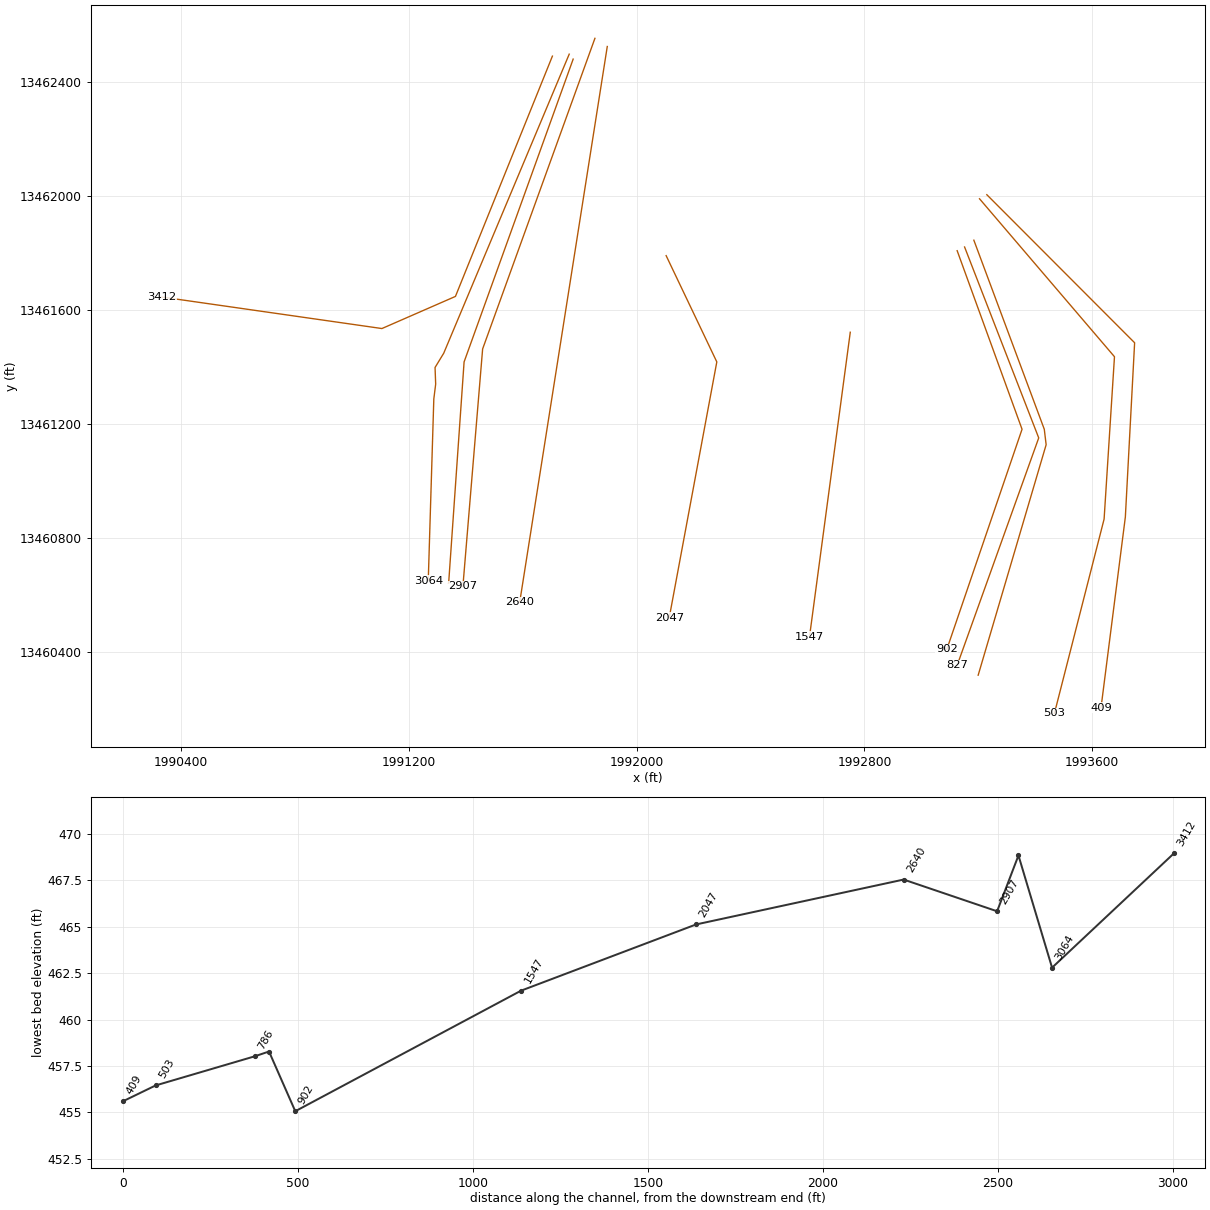
HEC-RAS study UNT 024 in RCW.prj: UNT 024 in RCW Base Level Engineering

--- UNT 024 in RCW.g01 (geometry) --- (continued)

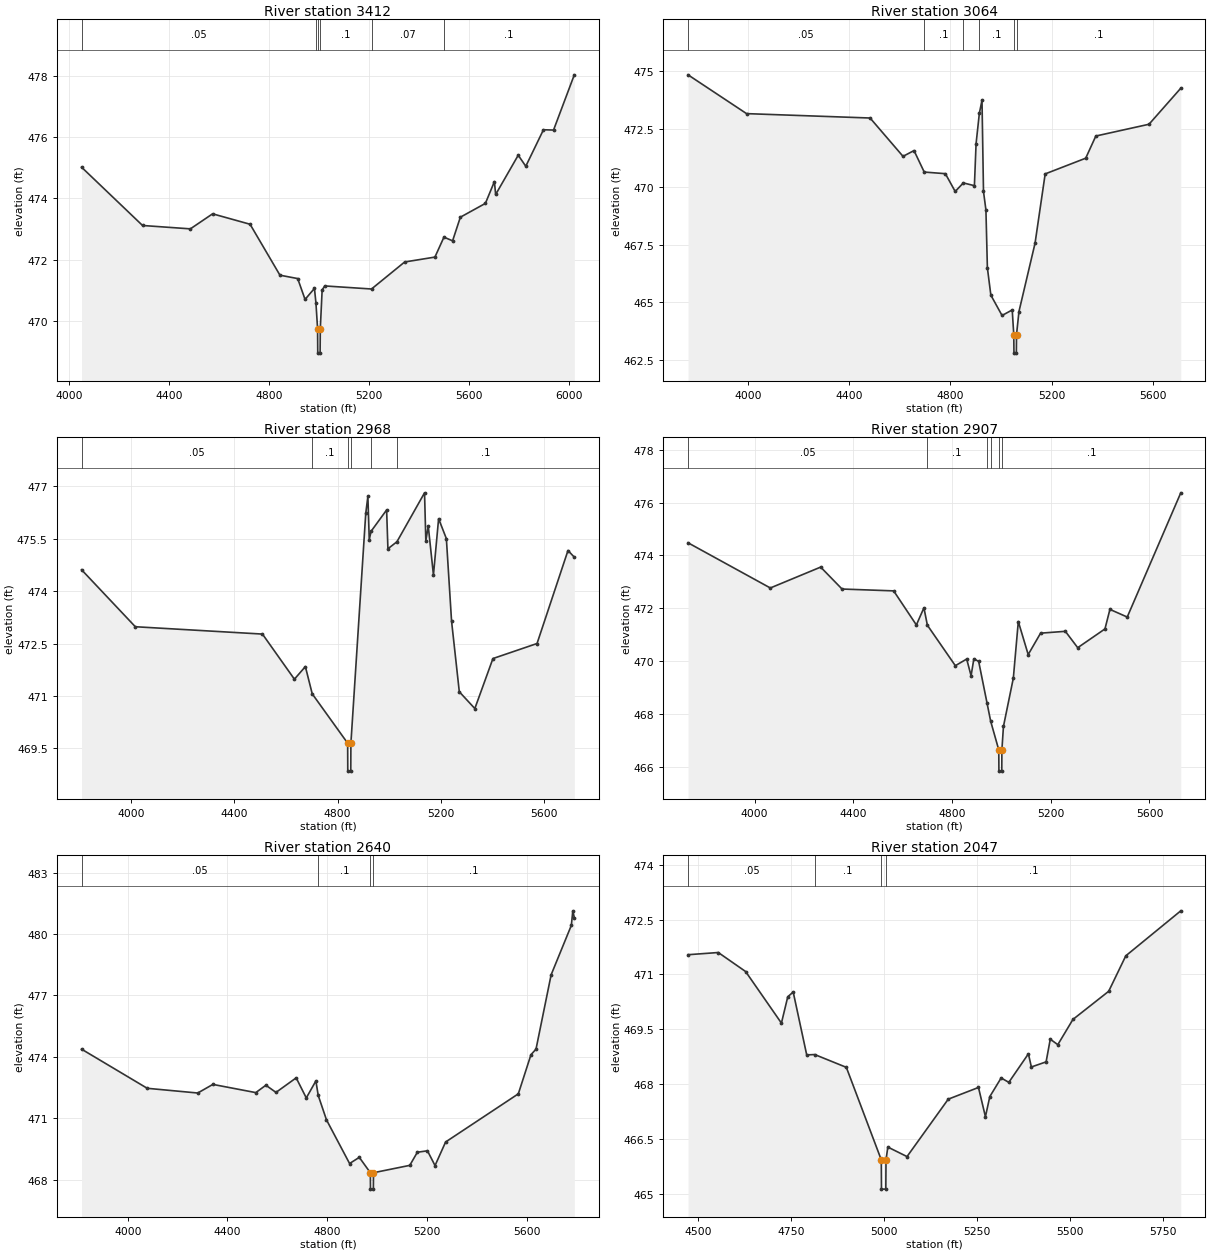
Type RM Length L Ch R = 1,3412,348,348,348
BEGIN DESCRIPTION:
Mapping XS 95f8a67a
END DESCRIPTION:
XS GIS Cut Line= 4
      1991704.06     13462491.39      1991363.49     13461647.45
      1991105.24     13461534.61      1990332.72     13461645.28
#Sta/Elev= 30
  4048.7  475.02  4292.8  473.12  4484.3  473.01  4573.2  473.50  4723.2  473.16
  4842.8  471.50  4913.8  471.39  4943.3  470.71  4980.9  471.07  4986.8  470.60
  4993.4  469.76  4994.1  468.96  5003.5  468.96  5004.3  469.76  5011.7  471.02
  5022.2  471.15  5209.3  471.05  5341.9  471.93  5463.1  472.09  5499.2  472.74
  5533.8  472.62  5564.9  473.39  5665.1  473.84  5701.1  474.55  5706.2  474.13
  5796.5  475.41  5826.8  475.05  5897.5  476.24  5937.9  476.23  6021.0  478.03
#Mann=6,-1,0
  4048.7    0.05       0  4986.8     0.1       0  4993.4    0.07       0
  5004.3     0.1       0  5209.3    0.07       0  5499.2     0.1       0
Bank Sta=4993.4,5004.3
Exp/Cntr=0.3,0.1

Type RM Length L Ch R = 1,3064,96,96,96
BEGIN DESCRIPTION:
Mapping XS 0978c342
END DESCRIPTION:
XS GIS Cut Line= 6
      1991763.07     13462498.28      1991322.26     13461447.80
      1991291.87     13461397.89      1991294.04     13461339.29
      1991287.53     13461287.21      1991268.01     13460649.58
#Sta/Elev= 30
  3763.4  474.85  3994.7  473.17  4482.7  472.98  4612.8  471.32  4656.2  471.57
  4696.6  470.64  4780.1  470.57  4818.9  469.80  4851.1  470.17  4894.8  470.05
  4901.4  471.87  4914.3  473.18  4924.8  473.75  4930.7  469.80  4940.3  469.00
  4946.1  466.49  4959.8  465.31  5004.0  464.43  5044.2  464.67  5050.3  463.60
  5051.1  462.80  5060.5  462.80  5061.2  463.60  5070.8  464.60  5134.4  467.56
  5174.4  470.56  5334.5  471.24  5374.5  472.20  5584.6  472.71  5710.1  474.27
#Mann=6,-1,0
  3763.4    0.05       0  4696.6     0.1       0  4851.1    0.07       0
  4914.3     0.1       0  5050.3    0.07       0  5061.2     0.1       0
Bank Sta=5050.3,5061.2
Exp/Cntr=0.3,0.1

Type RM Length L Ch R = 1,2968,61,61,61
BEGIN DESCRIPTION:
Mapping XS ccdf1839
END DESCRIPTION:
XS GIS Cut Line= 3
      1991776.96     13462480.93      1991393.87     13461417.42
      1991339.62     13460640.51
#Sta/Elev= 30
  3807.8  474.61  4016.1  472.98  4508.7  472.77  4632.5  471.48  4675.0  471.84
  4701.6  471.06  4838.8  469.65  4839.3  468.85  4850.9  468.85  4851.4  469.65
  4908.9  476.22  4917.2  476.71  4922.5  475.47  4929.6  475.71  4989.8  476.32
  4994.8  475.21  5029.7  475.41  5136.7  476.81  5141.7  475.44  5151.1  475.86
  5171.2  474.46  5191.2  476.07  5221.3  475.50  5241.4  473.14  5271.4  471.12
  5331.6  470.64  5401.7  472.07  5572.6  472.50  5692.5  475.16  5717.0  474.97
#Mann=6,-1,0
  3807.8    0.05       0  4701.6     0.1       0  4838.8    0.07       0
  4851.4     0.1       0  4929.6    0.07       0  5029.7     0.1       0
Bank Sta=4838.8,4851.4
Exp/Cntr=0.3,0.1

Type RM Length L Ch R = 1,2907,267,267,267
BEGIN DESCRIPTION:
Mapping XS 4fb273e8
END DESCRIPTION:
XS GIS Cut Line= 3
      1991853.36     13462553.88      1991458.98     13461462.99
      1991389.64     13460628.76
#Sta/Elev= 30
  3729.9  474.48  4063.5  472.77  4267.5  473.56  4354.1  472.73  4563.4  472.66
  4655.4  471.37  4686.0  472.02  4700.0  471.36  4813.3  469.83  4859.3  470.08
  4877.1  469.45  4888.4  470.09  4907.9  469.99  4941.9  468.41  4956.5  467.73
  4989.4  466.64  4989.9  465.84  5001.5  465.84  5002.0  466.64  5008.3  467.53
  5048.4  469.36  5068.5  471.50  5108.6  470.25  5158.8  471.06  5259.2  471.13
  5309.3  470.51  5419.7  471.22  5439.8  471.96  5510.0  471.67  5727.0  476.37
#Mann=6,-1,0
  3729.9    0.05       0  4700.0     0.1       0  4941.9    0.07       0
  4956.5     0.1       0  4989.4    0.07       0  5002.0     0.1       0
Bank Sta=4989.4,5002
Exp/Cntr=0.3,0.1

Type RM Length L Ch R = 1,2640,593,593,593
BEGIN DESCRIPTION:
Mapping XS 555b8c58
END DESCRIPTION:
XS GIS Cut Line= 2
      1991896.75     13462525.19      1991589.19     13460573.28
#Sta/Elev= 30
  3814.9  474.38  4078.3  472.47  4280.8  472.24  4341.5  472.66  4513.6  472.26
  4554.1  472.62  4594.6  472.27  4675.6  472.98  4716.1  472.00  4754.6  472.83
  4764.0  472.12  4797.1  470.93  4889.7  468.80  4928.7  469.10  4973.0  468.35
  4973.5  467.55  4985.1  467.55  4985.6  468.35  5131.1  468.71  5161.5  469.35
  5202.0  469.42  5232.4  468.70  5274.8  469.85  5566.4  472.20  5617.1  474.11
  5637.3  474.38  5698.0  478.01  5779.0  480.42  5784.9  481.13  5790.9  480.80
#Mann=4,-1,0
  3814.9    0.05       0  4764.0     0.1       0  4973.0    0.07       0
  4985.6     0.1       0
Bank Sta=4973,4985.6
Exp/Cntr=0.3,0.1

Type RM Length L Ch R = 1,2047,500,500,500
BEGIN DESCRIPTION:
Mapping XS b5b076dc
END DESCRIPTION:
XS GIS Cut Line= 3
      1992103.52     13461790.64      1992281.46     13461417.42
      1992114.45     13460519.49
#Sta/Elev= 30
  4472.0  471.54  4553.5  471.60  4627.1  471.08  4723.5  469.67  4740.6  470.39
  4755.2  470.52  4791.6  468.80  4813.2  468.81  4898.3  468.46  4992.4  465.93
  4992.9  465.13  5004.6  465.13  5005.1  465.93  5010.0  466.28  5061.7  466.02
  5172.7  467.59  5254.1  467.91  5272.8  467.11  5284.6  467.66  5315.1  468.17
  5335.8  468.05  5388.5  468.83  5396.5  468.47  5436.2  468.61  5447.4  469.23
  5467.7  469.08  5508.4  469.77  5604.7  470.54  5650.8  471.51  5798.8  472.74
#Mann=4,-1,0
  4472.0    0.05       0  4813.2     0.1       0  4992.4    0.07       0
  5005.1     0.1       0
Bank Sta=4992.4,5005.1
Exp/Cntr=0.3,0.1

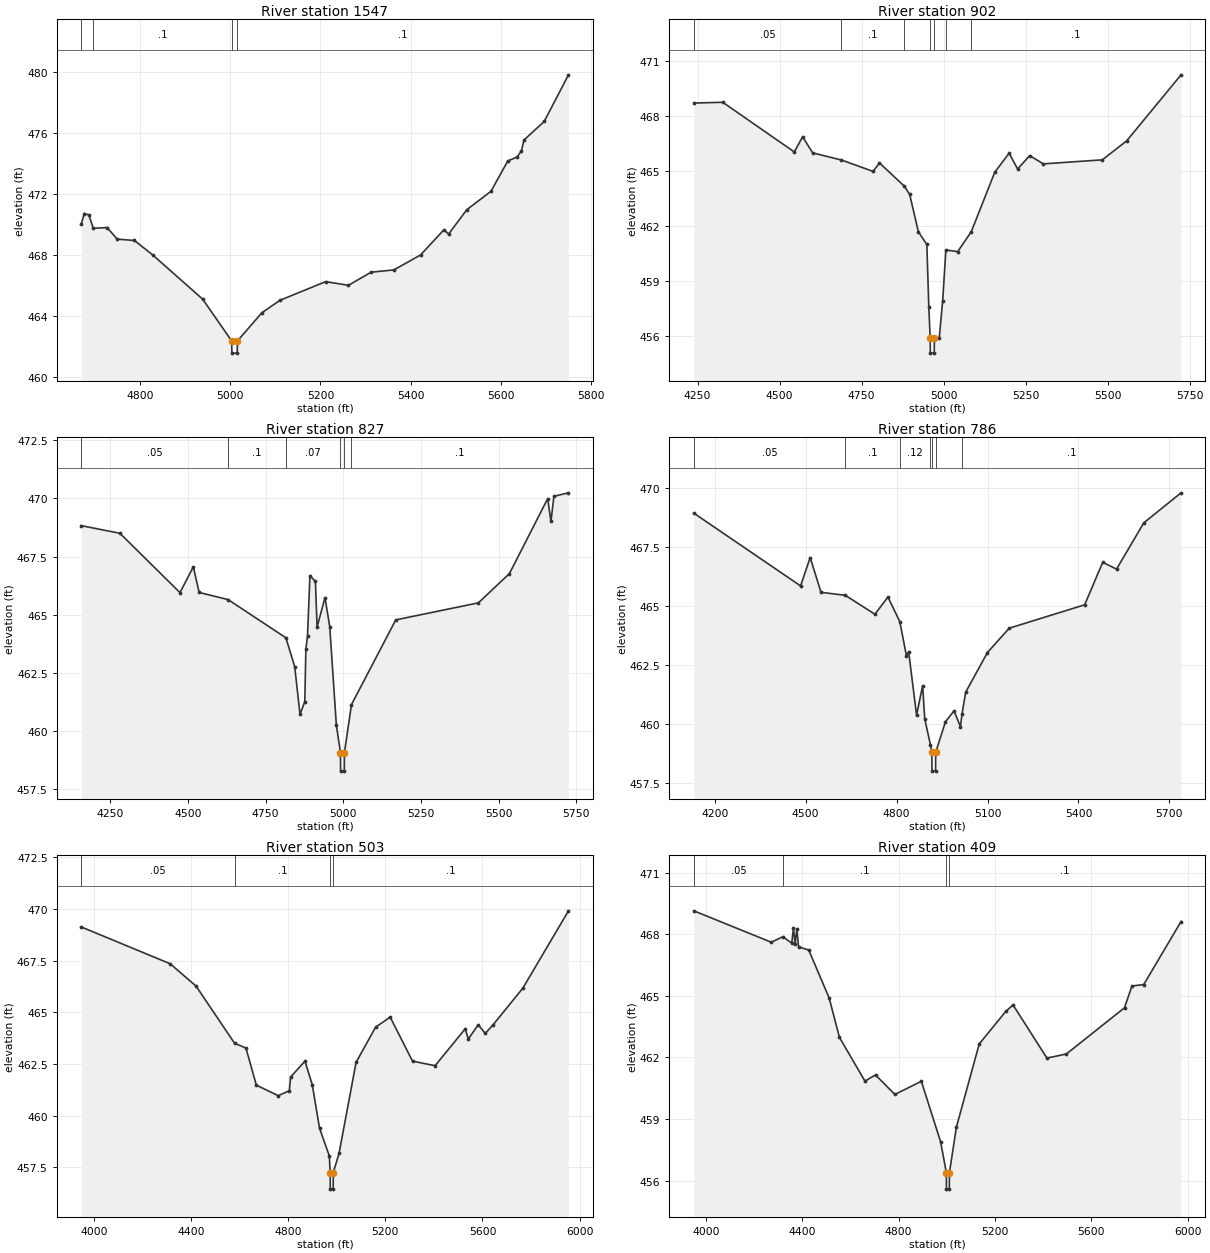
Type RM Length L Ch R = 1,1547,645,645,645
BEGIN DESCRIPTION:
Mapping XS 1f24b9e4
END DESCRIPTION:
XS GIS Cut Line= 2
      1992750.21     13461521.62      1992606.97     13460451.67
#Sta/Elev= 30
  4670.0  470.03  4676.7  470.72  4686.8  470.63  4696.6  469.75  4727.1  469.80
  4749.7  469.04  4787.7  468.95  4828.0  468.01  4939.0  465.10  5003.2  462.36
  5003.7  461.56  5015.5  461.56  5016.0  462.36  5070.2  464.21  5110.5  465.03
  5211.4  466.25  5261.9  466.01  5312.3  466.87  5362.7  467.02  5421.7  468.00
  5473.7  469.66  5483.8  469.37  5524.2  470.97  5577.8  472.18  5615.0  474.17
  5635.2  474.42  5645.2  474.82  5650.8  475.54  5695.7  476.76  5749.5  479.82
#Mann=4,-1,0
  4670.0    0.05       0  4696.6     0.1       0  5003.2    0.07       0
  5016.0     0.1       0
Bank Sta=5003.2,5016
Exp/Cntr=0.3,0.1

Type RM Length L Ch R = 1,902,75,75,75
BEGIN DESCRIPTION:
Mapping XS b827935a
END DESCRIPTION:
XS GIS Cut Line= 3
      1993125.65     13461808.01      1993353.51     13461180.87
      1993089.39     13460408.00
#Sta/Elev= 30
  4238.8  468.71  4327.1  468.75  4544.8  466.04  4570.1  466.87  4600.7  465.99
  4688.5  465.60  4784.6  464.98  4804.3  465.44  4879.5  464.18  4896.1  463.73
  4922.8  461.68  4948.5  460.99  4954.5  457.58  4958.7  455.86  4959.2  455.06
  4971.0  455.06  4971.5  455.86  4986.2  455.87  4996.8  457.93  5006.5  460.69
  5042.5  460.60  5083.9  461.69  5155.3  464.93  5199.0  465.97  5225.1  465.11
  5261.7  465.84  5303.3  465.39  5482.9  465.61  5556.9  466.64  5722.8  470.25
#Mann=7,-1,0
  4238.8    0.05       0  4688.5     0.1       0  4879.5    0.07       0
  4958.7    0.07       0  4971.5    0.07       0  5006.5    0.16       0
  5083.9     0.1       0
Bank Sta=4958.7,4971.5
Exp/Cntr=0.3,0.1

Type RM Length L Ch R = 1,827,41,41,41
BEGIN DESCRIPTION:
Mapping XS dfbffef2
END DESCRIPTION:
XS GIS Cut Line= 3
      1993151.70     13461821.03      1993412.10     13461150.49
      1993125.63     13460351.85
#Sta/Elev= 30
  4156.8  468.83  4281.3  468.50  4474.4  465.95  4517.3  467.06  4536.1  465.96
  4629.4  465.65  4815.2  464.01  4843.6  462.77  4860.6  460.72  4876.1  461.27
  4879.5  463.52  4884.8  464.08  4892.6  466.68  4910.2  466.43  4915.6  464.47
  4941.0  465.74  4956.3  464.49  4977.6  460.26  4990.8  459.08  4991.3  458.28
  5003.1  458.28  5003.6  459.08  5026.3  461.14  5168.8  464.78  5434.4  465.51
  5534.6  466.77  5657.6  469.99  5668.1  469.01  5677.7  470.09  5724.6  470.24
#Mann=6,-1,0
  4156.8    0.05       0  4629.4     0.1       0  4815.2    0.07       0
  4990.8    0.07       0  5003.6    0.07       0  5026.3     0.1       0
Bank Sta=4990.8,5003.6
Exp/Cntr=0.3,0.1

Type RM Length L Ch R = 1,786,283,283,283
BEGIN DESCRIPTION:
Mapping XS a79b6cfb
END DESCRIPTION:
XS GIS Cut Line= 4
      1993184.25     13461844.91      1993431.63     13461180.87
      1993438.14     13461126.62      1993199.42     13460317.15
#Sta/Elev= 30
  4131.2  468.94  4483.3  465.86  4515.0  467.06  4550.7  465.59  4631.0  465.46
  4728.7  464.66  4771.4  465.39  4810.6  464.35  4832.6  462.90  4839.8  463.08
  4865.9  460.39  4886.0  461.64  4892.8  460.24  4911.8  459.13  4916.3  458.82
  4916.8  458.02  4928.6  458.02  4929.1  458.82  4961.3  460.11  4989.4  460.57
  5010.8  459.90  5015.6  460.42  5027.9  461.36  5099.7  463.04  5171.6  464.07
  5420.4  465.06  5480.0  466.86  5525.6  466.57  5615.5  468.53  5738.4  469.80
#Mann=7,-1,0
  4131.2    0.05       0  4631.0     0.1       0  4810.6    0.12       0
  4911.8    0.07       0  4916.3    0.07       0  4929.1    0.07       0
  5015.6     0.1       0
Bank Sta=4916.3,4929.1
Exp/Cntr=0.3,0.1

Type RM Length L Ch R = 1,503,94,94,94
BEGIN DESCRIPTION:
Mapping XS 0df2bbec
END DESCRIPTION:
XS GIS Cut Line= 4
      1993204.18     13461990.36      1993678.16     13461435.65
      1993641.70     13460865.34      1993467.21     13460183.00
#Sta/Elev= 30
  3948.6  469.13  4314.5  467.35  4421.0  466.27  4579.3  463.51  4626.5  463.27
  4669.1  461.48  4759.0  460.97  4805.1  461.21  4810.1  461.87  4869.3  462.64
  4899.3  461.50  4929.4  459.39  4969.5  458.06  4973.1  457.25  4973.6  456.45
  4985.4  456.45  4985.9  457.25  5009.6  458.18  5079.7  462.58  5159.9  464.28
  5220.0  464.77  5312.0  462.64  5404.9  462.42  5528.7  464.20  5541.7  463.71
  5582.5  464.40  5611.3  463.98  5642.3  464.38  5766.1  466.17  5954.0  469.91
#Mann=4,-1,0
  3948.6    0.05       0  4579.3     0.1       0  4973.1    0.07       0
  4985.9     0.1       0
Bank Sta=4973.1,4985.9
Exp/Cntr=0.3,0.1

Type RM Length L Ch R = 1,409,0,0,0
BEGIN DESCRIPTION:
UNT 024 in RCW 1.0
END DESCRIPTION:
XS GIS Cut Line= 4
      1993229.80     13462004.66      1993748.91     13461484.69
      1993716.35     13460872.71      1993630.86     13460202.62
#Sta/Elev= 30
  3949.7  469.14  4271.3  467.61  4319.4  467.88  4356.2  467.57  4363.3  468.29
  4370.3  467.53  4377.4  468.27  4384.5  467.39  4426.9  467.23  4511.8  464.89
  4554.2  462.98  4660.2  460.85  4704.2  461.15  4784.3  460.20  4894.4  460.84
  4974.5  457.89  4998.2  456.39  4998.7  455.59  5010.5  455.59  5011.0  456.39
  5040.0  458.61  5134.8  462.66  5244.9  464.24  5275.0  464.56  5415.9  461.97
  5496.6  462.17  5738.0  464.42  5768.8  465.48  5817.8  465.55  5972.8  468.62
#Mann=4,-1,0
  3949.7    0.05       0  4319.4     0.1       0  4998.2    0.07       0
  5011.0     0.1       0
Bank Sta=4998.2,5011
Exp/Cntr=0.3,0.1

Chan Stop Cuts=-1