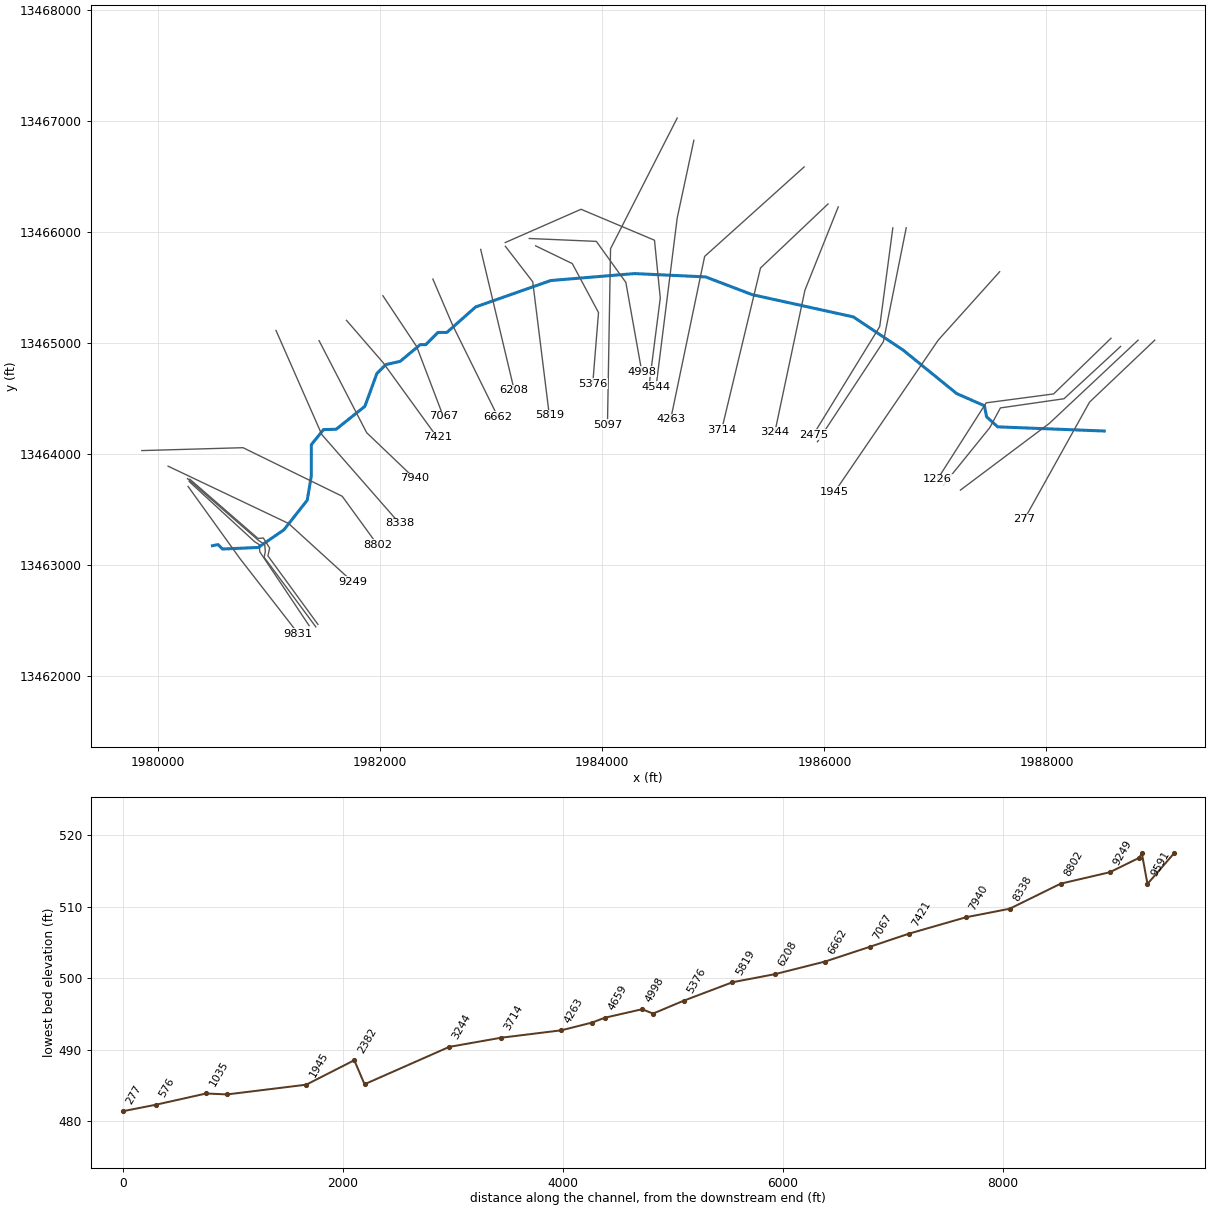
--- UNT 026 in RCW.prj (project) ---

Proj Title=UNT 026 in RCW Base Level Engineering
Current Plan=p01
Default Exp/Contr=0.3,0.1
English Units
Geom File=g01
Flow File=f01
Plan File=p01
BEGIN DESCRIPTION:
UNT 026 in RCW
END DESCRIPTION:

--- UNT 026 in RCW.p01 (plan) ---

Plan Title=Multiple Run
Short Identifier=Multiple
Geom File=g01
Flow File=f01
Subcritical Flow
K Sum by GR= 0
Std Step Tol= 0.01
Critical Tol= 0.01
Num of Std Step Trials= 20
Max Error Tol= 0.3
Flow Tol Ratio= 0.001
Split Flow NTrial= 30
Split Flow Tol= 0.02
Split Flow Ratio= 0.02
Log Output Level= 0
Friction Slope Method= 1
Unsteady Friction Slope Method= 2
Unsteady Bridges Friction Slope Method= 1
Parabolic Critical Depth
Global Vel Dist=  1 , 1 , 1
Global Log Level= 0
CheckData=True
Encroach Param= -1, 0, 0, 0
BEGIN DESCRIPTION:
Multiple Run
END DESCRIPTION:

--- UNT 026 in RCW.f01 (steady flow) ---

Flow Title=Multiple
Number of Profiles=7
Profile Names=10-year,25-year,50-year,1pct_min,100-year,1pct_plu,500-year
River Rch & RM= UNT 026 in RCW,Reach-1,9831
     172     235     286     174     348     693     520
River Rch & RM= UNT 026 in RCW,Reach-1,8802
     225     312     383     235     468     934     711
River Rch & RM= UNT 026 in RCW,Reach-1,5097
     265     368     453     278     555    1108     846
River Rch & RM= UNT 026 in RCW,Reach-1,277
     519     741     930     580    1158    2310    1823
Boundary for River Rch & Prof#=UNT 026 in RCW,Reach-1,1
Up Type=0
Dn Type=3
Dn Slope=0.005
Boundary for River Rch & Prof#=UNT 026 in RCW,Reach-1,2
Up Type=0
Dn Type=3
Dn Slope=0.005
Boundary for River Rch & Prof#=UNT 026 in RCW,Reach-1,3
Up Type=0
Dn Type=3
Dn Slope=0.005
Boundary for River Rch & Prof#=UNT 026 in RCW,Reach-1,4
Up Type=0
Dn Type=3
Dn Slope=0.005
Boundary for River Rch & Prof#=UNT 026 in RCW,Reach-1,5
Up Type=0
Dn Type=3
Dn Slope=0.005
Boundary for River Rch & Prof#=UNT 026 in RCW,Reach-1,6
Up Type=0
Dn Type=3
Dn Slope=0.005
Boundary for River Rch & Prof#=UNT 026 in RCW,Reach-1,7
Up Type=0
Dn Type=3
Dn Slope=0.005

--- UNT 026 in RCW.g01 (geometry) ---

Geom Title=Existing Conditions

River Reach=UNT 026 in RCW,Reach-1
Reach XY= 30
      1980490.80     13463174.54      1980540.80     13463184.54
      1980580.80     13463144.54      1980902.56     13463158.38
      1981133.48     13463317.22      1981343.53     13463583.73
      1981380.80     13463804.54      1981380.80     13464084.54
      1981490.80     13464220.02      1981603.95     13464222.62
      1981862.63     13464429.22      1981970.80     13464724.54
      1982050.80     13464804.54      1982180.80     13464834.54
      1982360.80     13464984.54      1982410.80     13464984.54
      1982520.80     13465094.54      1982600.80     13465094.54
      1982860.80     13465324.54      1983536.24     13465561.87
      1984290.80     13465624.54      1984930.80     13465594.54
      1985350.80     13465434.54      1986260.80     13465234.54
      1986710.80     13464934.54      1987190.80     13464544.54
      1987440.80     13464434.54      1987460.80     13464334.54
      1987560.80     13464244.54      1988520.09     13464206.84

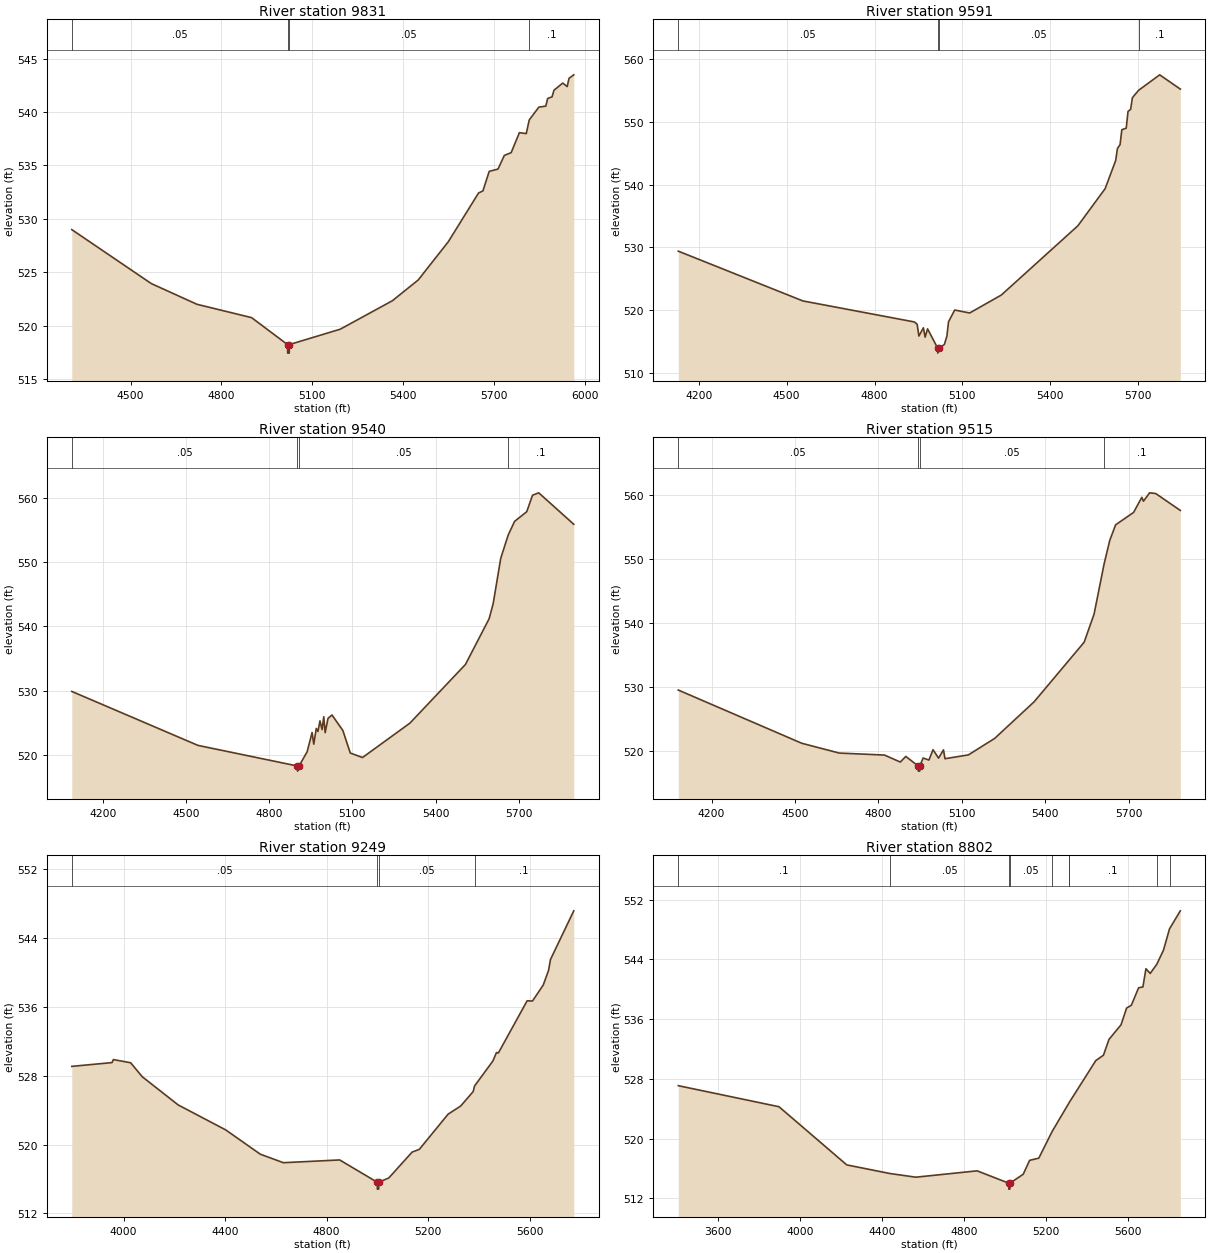
Type RM Length L Ch R = 1,9831,240,240,240
BEGIN DESCRIPTION:
UNT 026 in RCW 9.0
END DESCRIPTION:
XS GIS Cut Line= 3
      1980270.91     13463707.88      1980737.08     13463059.42
      1981263.09     13462382.37
#Sta/Elev= 30
  4306.2  529.00  4568.4  523.95  4719.1  522.01  4899.5  520.76  5018.0  518.24
  5018.5  517.44  5023.5  517.44  5024.0  518.24  5191.9  519.68  5363.7  522.34
  5448.9  524.28  5548.5  527.87  5648.0  532.42  5662.5  532.62  5683.3  534.45
  5712.3  534.66  5733.1  535.94  5755.7  536.20  5782.9  538.07  5805.5  537.98
  5815.3  539.26  5847.1  540.46  5869.8  540.55  5876.1  541.27  5890.6  541.42
  5896.9  542.04  5925.9  542.71  5940.4  542.38  5946.7  543.16  5962.2  543.48
#Mann=4,-1,0
  4306.2    0.05       0  5018.0   0.035       0  5024.0    0.05       0
  5815.3     0.1       0
Bank Sta=5018,5024
Exp/Cntr=0.3,0.1

Type RM Length L Ch R = 1,9591,51,51,51
BEGIN DESCRIPTION:
Mapping XS d923d479
END DESCRIPTION:
XS GIS Cut Line= 6
      1980281.33     13463752.14      1980869.89     13463210.46
      1980911.56     13463184.42      1980914.16     13463150.56
      1980916.77     13463119.31      1981361.05     13462454.19
#Sta/Elev= 30
  4130.0  529.41  4555.4  521.49  4936.3  518.14  4945.7  517.77  4951.6  515.90
  4966.9  517.21  4972.8  515.72  4981.2  517.04  5015.6  513.98  5016.1  513.18
  5021.6  513.98  5038.6  514.57  5047.2  515.89  5052.8  518.18  5073.9  520.04
  5124.9  519.57  5233.1  522.43  5494.4  533.45  5587.5  539.36  5623.5  543.84
  5629.5  545.76  5638.5  546.38  5644.5  548.74  5659.5  548.99  5665.6  551.65
  5674.6  551.99  5680.6  553.84  5701.6  555.01  5773.7  557.48  5844.2  555.21
#Mann=4,-1,0
  4130.0    0.05       0  5015.6   0.035       0  5021.6    0.05       0
  5701.6     0.1       0
Bank Sta=5015.6,5021.6
Exp/Cntr=0.3,0.1

Type RM Length L Ch R = 1,9540,25,25,25
BEGIN DESCRIPTION:
Mapping XS f07cec4d
END DESCRIPTION:
XS GIS Cut Line= 6
      1980265.76     13463778.14      1980906.35     13463220.88
      1980961.04     13463184.42      1980966.25     13463121.92
      1980955.83     13463069.83      1981420.99     13462443.55
#Sta/Elev= 30
  4087.5  529.87  4542.8  521.46  4901.5  518.25  4902.0  517.45  4907.5  518.25
  4936.6  520.46  4954.6  523.47  4960.6  521.65  4969.6  524.10  4975.6  523.62
  4983.0  525.28  4990.6  523.92  4996.6  525.92  5001.7  523.45  5011.9  525.66
  5026.3  526.20  5065.4  523.79  5092.4  520.27  5136.5  519.57  5307.5  524.93
  5507.8  534.07  5593.3  541.20  5607.9  543.56  5635.2  550.62  5662.0  554.23
  5685.1  556.36  5728.9  557.87  5749.8  560.44  5772.2  560.81  5898.6  555.91
#Mann=4,-1,0
  4087.5    0.05       0  4901.5   0.035       0  4907.5    0.05       0
  5662.0     0.1       0
Bank Sta=4901.5,4907.5
Exp/Cntr=0.3,0.1

Type RM Length L Ch R = 1,9515,266,266,266
BEGIN DESCRIPTION:
Mapping XS 15e942b8
END DESCRIPTION:
XS GIS Cut Line= 6
      1980286.55     13463772.97      1980901.14     13463239.11
      1980948.02     13463244.31      1981005.31     13463153.17
      1980989.68     13463082.86      1981440.11     13462465.80
#Sta/Elev= 30
  4080.3  529.50  4524.5  521.18  4659.4  519.65  4821.7  519.34  4878.7  518.25
  4898.4  519.13  4942.9  517.63  4943.4  516.83  4948.4  516.83  4948.9  517.63
  4960.7  518.88  4981.6  518.56  4996.4  520.18  5016.2  518.86  5033.9  520.15
  5039.4  518.77  5123.7  519.37  5217.9  521.94  5360.0  527.67  5539.9  536.98
  5575.5  541.37  5611.1  549.12  5631.9  552.89  5652.8  555.31  5717.6  557.26
  5747.0  559.61  5753.2  559.02  5775.2  560.32  5797.2  560.21  5885.6  557.57
#Mann=4,-1,0
  4080.3    0.05       0  4942.9   0.035       0  4948.9    0.05       0
  5611.1     0.1       0
Bank Sta=4942.9,4948.9
Exp/Cntr=0.3,0.1

Type RM Length L Ch R = 1,9249,447,447,447
BEGIN DESCRIPTION:
UNT 026 in RCW 8.0
END DESCRIPTION:
XS GIS Cut Line= 3
      1980091.21     13463890.16      1981175.00     13463375.00
      1981750.53     13462850.46
#Sta/Elev= 30
  3795.7  529.08  3954.3  529.52  3959.8  529.87  4027.9  529.50  4073.4  527.88
  4215.2  524.60  4402.5  521.70  4538.8  518.88  4629.7  517.89  4851.8  518.21
  4999.8  515.62  5000.3  514.82  5005.3  514.82  5005.8  515.62  5045.4  516.12
  5137.2  519.12  5165.6  519.44  5279.1  523.53  5328.5  524.47  5377.8  526.15
  5383.3  526.80  5455.7  529.71  5469.7  530.69  5477.1  530.63  5590.6  536.70
  5611.6  536.67  5654.1  538.53  5675.1  540.24  5682.5  541.49  5774.4  547.15
#Mann=4,-1,0
  3795.7    0.05       0  4999.8   0.035       0  5005.8    0.05       0
  5383.3     0.1       0
Bank Sta=4999.8,5005.8
Exp/Cntr=0.3,0.1

Type RM Length L Ch R = 1,8802,464,464,464
BEGIN DESCRIPTION:
UNT 026 in RCW 7.0
END DESCRIPTION:
XS GIS Cut Line= 4
      1979854.29     13464030.77      1980765.72     13464056.81
      1981658.95     13463619.31      1981976.65     13463181.83
#Sta/Elev= 30
  3407.9  527.08  3898.8  524.26  4228.9  516.47  4439.6  515.31  4566.0  514.82
  4864.5  515.67  5018.6  514.02  5019.1  513.22  5024.1  513.22  5024.6  514.02
  5089.1  515.21  5120.6  517.08  5165.2  517.37  5230.3  520.95  5313.9  524.84
  5314.4  524.87  5443.2  530.45  5480.2  531.16  5507.3  533.28  5566.0  535.24
  5593.1  537.48  5616.3  537.86  5651.8  540.20  5672.7  540.31  5687.4  542.75
  5708.2  542.12  5740.4  543.35  5773.2  545.26  5802.3  548.09  5855.0  550.51
#Mann=9,-1,0
  3407.9     0.1       0  4439.6    0.05       0  5018.6   0.035       0
  5024.6    0.05       0  5230.3     0.1       0  5313.9    0.05       0
  5314.4     0.1       0  5740.4    0.05       0  5802.3     0.1       0
Bank Sta=5018.6,5024.6
Exp/Cntr=0.3,0.1

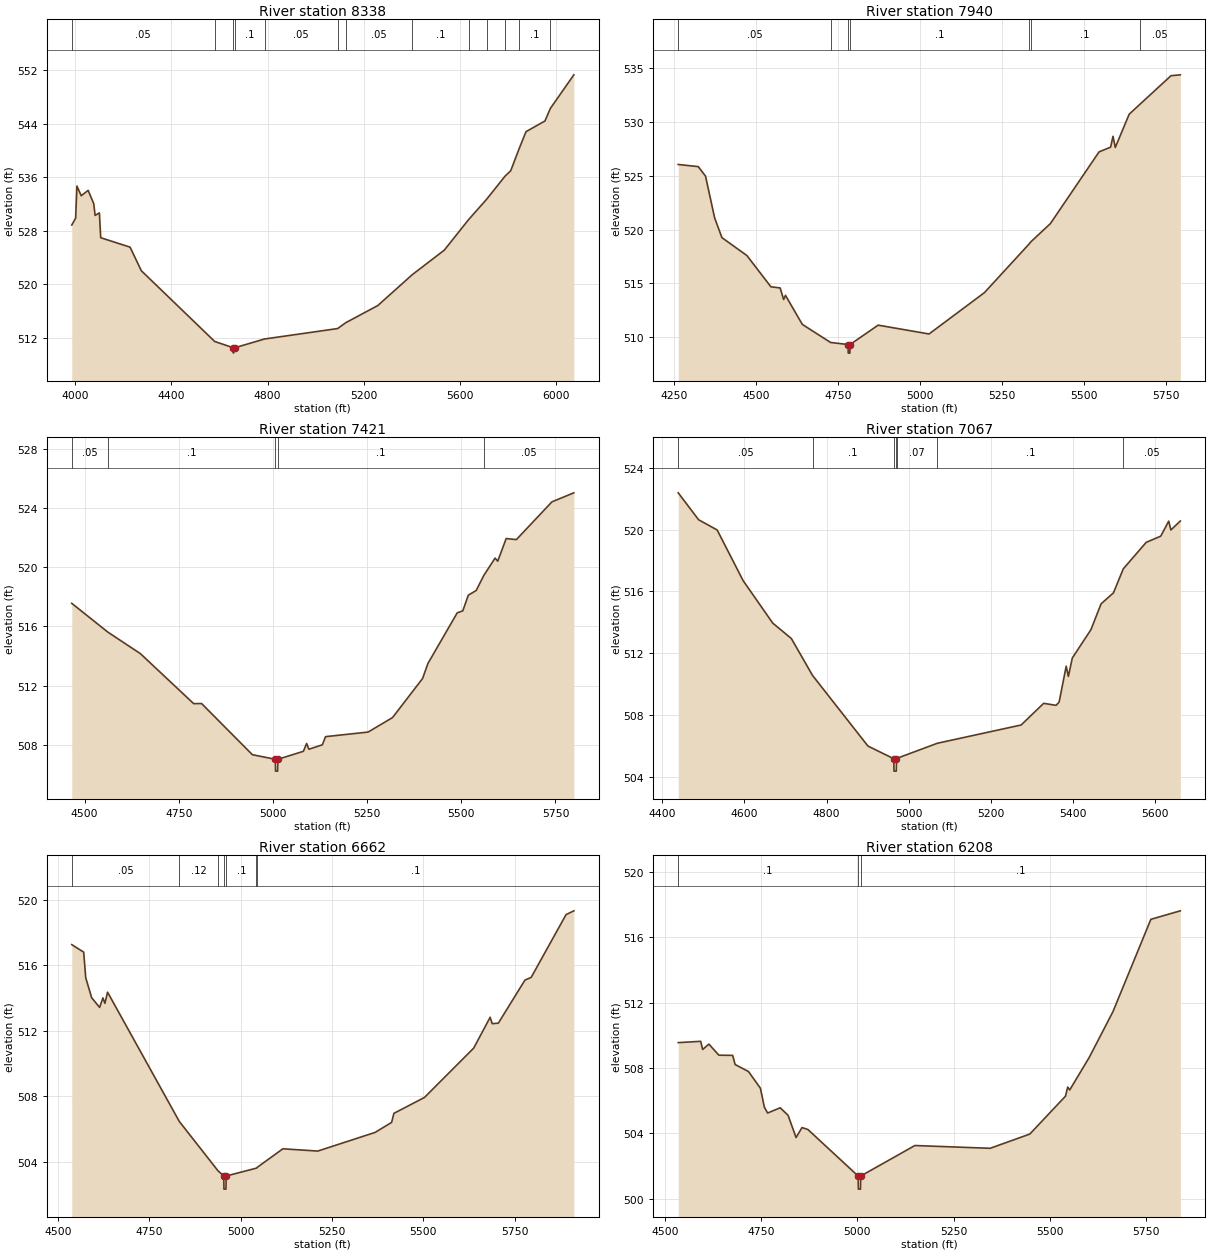
Type RM Length L Ch R = 1,8338,398,398,398
BEGIN DESCRIPTION:
UNT 026 in RCW 6.0
END DESCRIPTION:
XS GIS Cut Line= 3
      1981062.58     13465112.41      1981475.00     13464175.00
      1982174.97     13463375.03
#Sta/Elev= 30
  3986.3  528.84  4002.3  529.87  4007.8  534.66  4025.6  533.22  4054.4  534.02
  4077.8  532.02  4083.2  530.28  4101.1  530.66  4106.6  526.95  4228.7  525.54
  4275.4  522.02  4580.5  511.45  4657.8  510.51  4658.3  509.71  4663.8  510.51
  4787.5  511.82  5091.5  513.38  5125.5  514.26  5258.6  516.82  5401.1  521.41
  5534.8  525.09  5635.6  529.64  5710.8  532.69  5788.0  536.17  5811.0  536.95
  5846.9  540.33  5874.6  542.79  5953.4  544.39  5975.6  546.25  6073.4  551.28
#Mann=13,-1,0
  3986.3    0.05       0  4580.5     0.1       0  4657.8   0.035       0
  4663.8     0.1       0  4787.5    0.05       0  5091.5     0.1       0
  5125.5    0.05       0  5401.1     0.1       0  5635.6    0.05       0
  5710.8     0.1       0  5788.0    0.05       0  5846.9     0.1       0
  5975.6    0.05       0
Bank Sta=4657.8,4663.8
Exp/Cntr=0.3,0.1

Type RM Length L Ch R = 1,7940,519,519,519
BEGIN DESCRIPTION:
UNT 026 in RCW 5.0
END DESCRIPTION:
XS GIS Cut Line= 3
      1981450.21     13465020.75      1981878.57     13464192.23
      1982310.11     13463780.14
#Sta/Elev= 30
  4263.0  526.05  4324.0  525.85  4346.1  524.97  4373.9  521.09  4396.1  519.25
  4472.1  517.59  4545.4  514.68  4573.4  514.58  4584.1  513.50  4589.7  513.89
  4641.0  511.19  4727.1  509.51  4780.4  509.32  4780.9  508.52  4785.9  508.52
  4786.4  509.32  4872.0  511.12  5027.0  510.30  5195.7  514.14  5331.8  518.66
  5337.4  518.87  5396.5  520.55  5544.9  527.22  5580.1  527.66  5587.4  528.67
  5594.3  527.63  5636.7  530.72  5668.2  531.61  5764.1  534.30  5792.4  534.38
#Mann=7,-1,0
  4263.0    0.05       0  4727.1     0.1       0  4780.4    0.07       0
  4786.4     0.1       0  5331.8    0.05       0  5337.4     0.1       0
  5668.2    0.05       0
Bank Sta=4780.4,4786.4
Exp/Cntr=0.3,0.1

Type RM Length L Ch R = 1,7421,354,354,354
BEGIN DESCRIPTION:
UNT 026 in RCW 4.0
END DESCRIPTION:
XS GIS Cut Line= 3
      1981697.14     13465203.53      1982025.00     13464825.00
      1982513.11     13464151.44
#Sta/Elev= 30
  4466.1  517.56  4562.2  515.61  4648.3  514.16  4789.7  510.78  4810.6  510.79
  4945.5  507.33  5006.5  507.02  5007.0  506.22  5012.5  506.22  5013.0  507.02
  5080.9  507.56  5089.4  508.09  5095.6  507.70  5131.2  508.00  5139.7  508.55
  5252.6  508.86  5317.5  509.84  5397.2  512.48  5411.5  513.50  5489.2  516.92
  5503.9  517.05  5518.6  518.11  5539.5  518.43  5559.8  519.45  5589.7  520.62
  5596.7  520.41  5619.1  521.94  5646.2  521.87  5740.5  524.42  5798.7  525.03
#Mann=5,-1,0
  4466.1    0.05       0  4562.2     0.1       0  5006.5    0.07       0
  5013.0     0.1       0  5559.8    0.05       0
Bank Sta=5006.5,5013
Exp/Cntr=0.3,0.1

Type RM Length L Ch R = 1,7067,405,405,405
BEGIN DESCRIPTION:
UNT 026 in RCW 3.0
END DESCRIPTION:
XS GIS Cut Line= 3
      1982025.01     13465424.99      1982329.09     13464967.40
      1982568.46     13464339.49
#Sta/Elev= 30
  4439.3  522.37  4488.9  520.63  4534.0  519.97  4597.1  516.70  4669.3  513.95
  4714.4  512.96  4766.1  510.57  4900.8  506.01  4963.7  505.19  4964.2  504.39
  4969.7  504.39  4970.2  505.19  4971.6  505.22  5069.7  506.19  5273.4  507.37
  5328.3  508.77  5358.4  508.64  5365.9  508.85  5383.1  511.17  5388.4  510.51
  5398.0  511.70  5443.3  513.53  5468.0  515.20  5498.1  515.91  5522.0  517.46
  5577.7  519.17  5613.1  519.57  5632.5  520.54  5637.8  519.97  5660.7  520.55
#Mann=7,-1,0
  4439.3    0.05       0  4766.1     0.1       0  4963.7    0.07       0
  4970.2     0.1       0  4971.6    0.07       0  5069.7     0.1       0
  5522.0    0.05       0
Bank Sta=4963.7,4970.2
Exp/Cntr=0.3,0.1

Type RM Length L Ch R = 1,6662,454,454,454
BEGIN DESCRIPTION:
UNT 026 in RCW 2.0
END DESCRIPTION:
XS GIS Cut Line= 3
      1982475.00     13465575.01      1982652.01     13465161.85
      1983060.86     13464333.76
#Sta/Elev= 30
  4538.5  517.25  4571.1  516.79  4576.6  515.24  4592.9  514.01  4614.7  513.42
  4623.7  514.00  4629.2  513.67  4636.4  514.35  4832.5  506.47  4938.3  503.46
  4954.2  503.14  4954.7  502.34  4960.2  502.34  4960.7  503.14  5043.6  503.62
  5045.2  503.66  5115.8  504.80  5211.2  504.66  5368.3  505.80  5413.2  506.41
  5419.4  506.96  5503.0  507.93  5637.7  510.94  5682.6  512.82  5688.2  512.43
  5705.0  512.46  5777.9  515.09  5794.8  515.25  5890.2  519.08  5911.5  519.31
#Mann=7,-1,0
  4538.5    0.05       0  4832.5    0.12       0  4938.3     0.1       0
  4954.2    0.07       0  4960.7     0.1       0  5043.6    0.07       0
  5045.2     0.1       0
Bank Sta=4954.2,4960.7
Exp/Cntr=0.3,0.1

Type RM Length L Ch R = 1,6208,389,389,389
BEGIN DESCRIPTION:
Mapping XS 0388672d
END DESCRIPTION:
XS GIS Cut Line= 2
      1982905.49     13465842.37      1983207.56     13464575.07
#Sta/Elev= 30
  4535.1  509.55  4593.3  509.63  4598.5  509.13  4614.6  509.46  4640.6  508.78
  4676.3  508.77  4682.7  508.21  4717.4  507.78  4748.3  506.76  4758.6  505.60
  4767.0  505.24  4799.7  505.56  4820.2  505.10  4840.8  503.74  4856.3  504.35
  4871.6  504.23  5002.0  501.38  5002.5  500.58  5008.0  500.58  5008.5  501.38
  5149.2  503.25  5344.5  503.08  5447.3  503.95  5539.9  506.27  5545.8  506.83
  5550.9  506.65  5601.5  508.64  5663.2  511.45  5761.5  517.10  5837.9  517.62
#Mann=3,-1,0
  4535.1     0.1       0  5002.0    0.07       0  5008.5     0.1       0
Bank Sta=5002,5008.5
Exp/Cntr=0.3,0.1

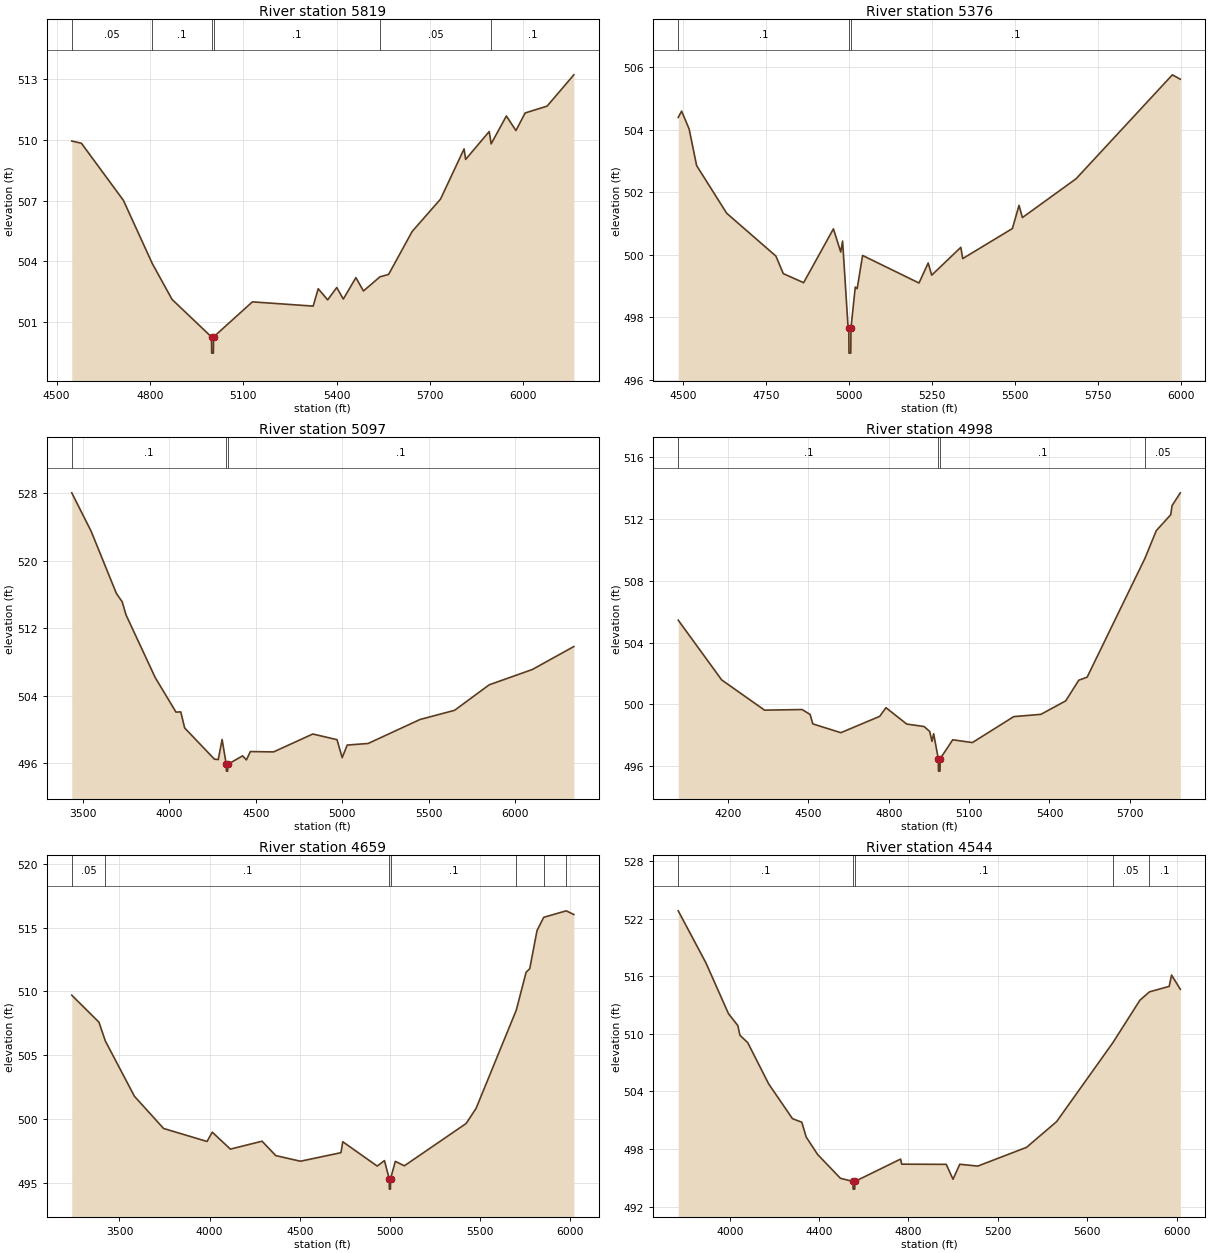
Type RM Length L Ch R = 1,5819,443,443,443
BEGIN DESCRIPTION:
Mapping XS 2b619476
END DESCRIPTION:
XS GIS Cut Line= 3
      1983127.69     13465870.20      1983374.23     13465550.74
      1983523.49     13464349.71
#Sta/Elev= 30
  4548.5  509.95  4579.5  509.84  4714.5  507.01  4807.3  503.88  4870.9  502.10
  4997.7  500.24  4998.2  499.44  5003.7  499.44  5004.2  500.24  5129.1  501.98
  5324.4  501.77  5340.7  502.63  5371.0  502.08  5400.2  502.69  5421.4  502.12
  5461.7  503.18  5486.1  502.52  5538.9  503.22  5566.9  503.34  5642.7  505.47
  5733.7  507.07  5809.5  509.56  5814.5  509.04  5890.3  510.42  5896.5  509.81
  5945.4  511.19  5976.2  510.47  6005.8  511.34  6076.4  511.68  6162.3  513.23
#Mann=6,-1,0
  4548.5    0.05       0  4807.3     0.1       0  4997.7    0.07       0
  5004.2     0.1       0  5538.9    0.05       0  5896.5     0.1       0
Bank Sta=4997.7,5004.2
Exp/Cntr=0.3,0.1

Type RM Length L Ch R = 1,5376,279,279,279
BEGIN DESCRIPTION:
Mapping XS 53dbbaac
END DESCRIPTION:
XS GIS Cut Line= 4
      1983400.40     13465874.28      1983730.31     13465714.53
      1983966.42     13465273.56      1983914.33     13464631.22
#Sta/Elev= 30
  4486.0  504.39  4496.2  504.59  4518.8  504.02  4541.4  502.85  4631.7  501.33
  4780.0  499.96  4802.2  499.40  4863.4  499.11  4953.1  500.83  4975.1  500.09
  4980.7  500.44  4997.0  497.72  4999.4  497.66  4999.9  496.86  5005.4  496.86
  5005.9  497.66  5018.9  498.97  5024.6  498.92  5040.9  499.98  5210.7  499.10
  5238.3  499.74  5248.9  499.35  5336.6  500.24  5342.3  499.88  5491.8  500.84
  5511.8  501.58  5521.9  501.19  5683.5  502.43  5973.3  505.75  5997.2  505.61
#Mann=3,-1,0
  4486.0     0.1       0  4999.4    0.07       0  5005.9     0.1       0
Bank Sta=4999.4,5005.9
Exp/Cntr=0.3,0.1

Type RM Length L Ch R = 1,5097,99,99,99
BEGIN DESCRIPTION:
UNT 024 in RCW 14.0
END DESCRIPTION:
XS GIS Cut Line= 3
      1984674.98     13467024.96      1984074.86     13465848.70
      1984047.08     13464265.34
#Sta/Elev= 30
  3435.3  528.05  3547.5  523.49  3693.7  516.11  3726.9  515.14  3749.1  513.58
  3918.0  506.15  4038.1  502.06  4066.0  502.08  4088.2  500.18  4260.4  496.48
  4282.6  496.43  4304.9  498.81  4329.0  495.86  4329.8  495.06  4336.9  495.06
  4337.7  495.86  4423.2  496.87  4445.6  496.39  4468.1  497.38  4602.8  497.34
  4829.5  499.46  4969.5  498.79  4999.5  496.66  5028.7  498.15  5149.6  498.34
  5449.6  501.18  5649.6  502.27  5849.7  505.29  6099.7  507.11  6339.4  509.83
#Mann=3,-1,0
  3435.3     0.1       0  4329.0    0.07       0  4337.7     0.1       0
Bank Sta=4329,4337.7
Exp/Cntr=0.3,0.1

Type RM Length L Ch R = 1,4998,339,339,339
BEGIN DESCRIPTION:
Mapping XS 7671be95
END DESCRIPTION:
XS GIS Cut Line= 4
      1983342.92     13465940.51      1983947.06     13465914.47
      1984212.68     13465544.67      1984355.92     13464742.57
#Sta/Elev= 30
  4013.7  505.45  4175.9  501.58  4336.1  499.62  4476.2  499.66  4506.2  499.34
  4516.3  498.73  4620.9  498.16  4766.1  499.22  4789.4  499.78  4866.8  498.72
  4931.8  498.56  4952.7  498.24  4961.3  497.60  4967.5  498.09  4984.9  496.47
  4985.4  495.67  4991.2  495.67  4991.7  496.47  5038.7  497.70  5112.1  497.52
  5266.4  499.20  5368.0  499.35  5460.6  500.22  5509.3  501.56  5540.7  501.76
  5756.8  509.47  5798.8  511.25  5852.7  512.28  5857.7  512.87  5888.5  513.70
#Mann=4,-1,0
  4013.7     0.1       0  4984.9    0.07       0  4991.7     0.1       0
  5756.8    0.05       0
Bank Sta=4984.9,4991.7
Exp/Cntr=0.3,0.1

Type RM Length L Ch R = 1,4659,115,115,115
BEGIN DESCRIPTION:
UNT 026 in RCW 1.0
END DESCRIPTION:
XS GIS Cut Line= 5
      1983126.87     13465904.05      1983809.04     13466203.53
      1984470.49     13465924.88      1984522.58     13465404.05
      1984421.02     13464612.43
#Sta/Elev= 30
  3235.4  509.70  3386.2  507.58  3421.4  506.11  3582.8  501.77  3744.5  499.24
  3985.5  498.22  4014.6  498.95  4115.0  497.62  4290.7  498.24  4366.7  497.11
  4503.5  496.67  4728.2  497.34  4738.2  498.20  4929.2  496.29  4969.4  496.72
  4996.2  495.28  4996.7  494.48  5002.5  494.48  5003.0  495.28  5029.7  496.66
  5079.9  496.31  5422.3  499.63  5477.7  500.82  5700.6  508.53  5755.0  511.50
  5775.1  511.78  5815.5  514.77  5852.6  515.81  5977.5  516.32  6019.7  516.03
#Mann=7,-1,0
  3235.4    0.05       0  3421.4     0.1       0  4996.2    0.07       0
  5003.0     0.1       0  5700.6    0.05       0  5852.6     0.1       0
  5977.5    0.05       0
Bank Sta=4996.2,5003
Exp/Cntr=0.3,0.1

Type RM Length L Ch R = 1,4544,281,281,281
BEGIN DESCRIPTION:
UNT 024 in RCW 13.0
END DESCRIPTION:
XS GIS Cut Line= 3
      1984824.99     13466824.95      1984675.00     13466125.00
      1984484.58     13464605.63
#Sta/Elev= 30
  3769.7  522.80  3893.2  517.40  3994.6  512.09  4036.4  510.85  4045.8  509.84
  4080.7  509.07  4174.5  504.77  4281.0  501.15  4322.8  500.78  4342.4  499.24
  4393.5  497.42  4495.6  494.94  4551.7  494.61  4552.5  493.81  4559.7  493.81
  4560.4  494.61  4764.8  496.94  4769.9  496.41  4969.3  496.39  4999.5  494.84
  5029.8  496.40  5110.4  496.21  5328.5  498.16  5463.1  500.84  5714.5  509.05
  5836.0  513.49  5878.7  514.36  5967.0  514.93  5977.7  516.11  6016.8  514.63
#Mann=5,-1,0
  3769.7     0.1       0  4551.7    0.07       0  4560.4     0.1       0
  5714.5    0.05       0  5878.7     0.1       0
Bank Sta=4551.7,4560.4
Exp/Cntr=0.3,0.1

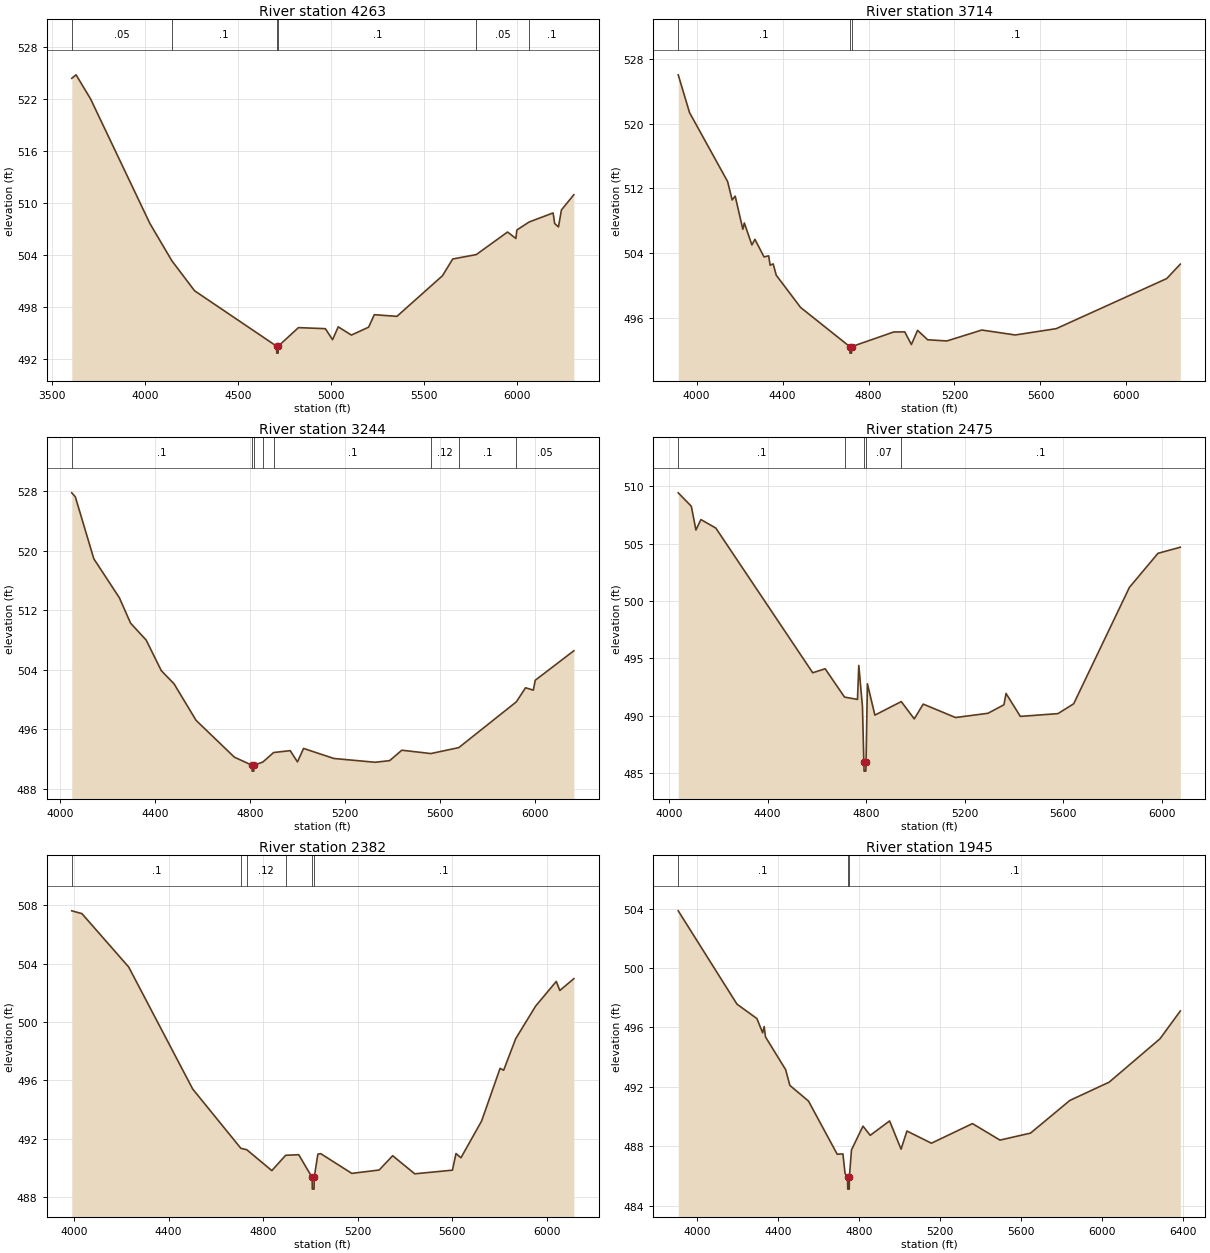
Type RM Length L Ch R = 1,4263,549,549,549
BEGIN DESCRIPTION:
UNT 024 in RCW 12.0
END DESCRIPTION:
XS GIS Cut Line= 3
      1985817.88     13466584.78      1984922.08     13465779.25
      1984616.53     13464313.98
#Sta/Elev= 30
  3606.6  524.40  3629.7  524.80  3707.4  522.04  4026.6  507.68  4145.1  503.37
  4267.3  499.91  4708.8  493.52  4709.6  492.72  4716.8  492.72  4717.6  493.52
  4826.2  495.66  4971.2  495.54  5009.7  494.27  5040.4  495.75  5111.1  494.80
  5203.8  495.71  5234.5  497.15  5356.2  496.96  5601.2  501.64  5656.3  503.57
  5783.3  504.08  5951.4  506.68  5996.3  505.94  6001.4  506.91  6067.0  507.83
  6196.5  508.88  6204.9  507.66  6225.3  507.27  6241.4  509.23  6308.1  510.98
#Mann=6,-1,0
  3606.6    0.05       0  4145.1     0.1       0  4708.8    0.07       0
  4717.6     0.1       0  5783.3    0.05       0  6067.0     0.1       0
Bank Sta=4708.8,4717.6
Exp/Cntr=0.3,0.1

Type RM Length L Ch R = 1,3714,470,470,470
BEGIN DESCRIPTION:
UNT 024 in RCW 11.0
END DESCRIPTION:
XS GIS Cut Line= 3
      1986033.21     13466251.49      1985425.00     13465675.00
      1985075.26     13464218.40
#Sta/Elev= 30
  3914.7  526.02  3967.3  521.36  4144.5  512.85  4165.6  510.58  4179.7  511.05
  4215.3  506.96  4222.2  507.74  4257.4  505.03  4271.5  505.72  4314.0  503.55
  4335.4  503.69  4342.3  502.53  4356.5  502.69  4370.6  501.30  4483.9  497.32
  4712.9  492.48  4713.7  491.68  4720.9  491.68  4721.7  492.48  4917.3  494.29
  4968.7  494.30  4999.5  492.74  5028.2  494.49  5075.3  493.33  5164.4  493.18
  5327.2  494.53  5482.9  493.92  5673.4  494.70  6187.5  500.88  6250.7  502.66
#Mann=3,-1,0
  3914.7     0.1       0  4712.9    0.07       0  4721.7     0.1       0
Bank Sta=4712.9,4721.7
Exp/Cntr=0.3,0.1

Type RM Length L Ch R = 1,3244,769,769,769
BEGIN DESCRIPTION:
UNT 024 in RCW 10.0
END DESCRIPTION:
XS GIS Cut Line= 3
      1986125.02     13466225.04      1985825.00     13465475.00
      1985554.02     13464195.91
#Sta/Elev= 30
  4048.6  527.79  4063.5  527.26  4141.5  518.93  4249.2  513.69  4296.4  510.28
  4362.3  508.00  4425.6  503.91  4479.5  502.13  4572.4  497.22  4733.9  492.27
  4807.6  491.20  4808.4  490.40  4815.6  490.40  4816.4  491.20  4853.6  491.62
  4899.1  492.90  4968.9  493.15  4999.5  491.64  5025.2  493.45  5152.9  492.10
  5326.6  491.59  5388.0  491.81  5439.1  493.21  5561.5  492.76  5679.2  493.56
  5921.7  499.71  5960.4  501.60  5993.2  501.28  6001.3  502.61  6163.9  506.57
#Mann=8,-1,0
  4048.6     0.1       0  4807.6    0.07       0  4816.4     0.1       0
  4853.6    0.12       0  4899.1     0.1       0  5561.5    0.12       0
  5679.2     0.1       0  5921.7    0.05       0
Bank Sta=4807.6,4816.4
Exp/Cntr=0.3,0.1

Type RM Length L Ch R = 1,2475,93,93,93
BEGIN DESCRIPTION:
UNT 024 in RCW 9.0
END DESCRIPTION:
XS GIS Cut Line= 3
      1986616.52     13466036.15      1986498.47     13465147.31
      1985901.22     13464175.04
#Sta/Elev= 30
  4037.6  509.43  4090.7  508.26  4109.4  506.19  4129.6  507.10  4190.1  506.36
  4583.5  493.75  4633.9  494.10  4712.5  491.63  4765.1  491.43  4770.4  494.39
  4785.3  490.81  4790.9  485.98  4791.7  485.18  4799.0  485.18  4799.8  485.98
  4805.4  492.79  4835.7  490.06  4942.8  491.24  4995.6  489.73  5031.8  491.02
  5163.2  489.85  5294.6  490.22  5359.5  490.96  5368.0  491.95  5426.0  489.95
  5578.7  490.19  5642.6  491.05  5868.7  501.19  5984.7  504.16  6075.3  504.69
#Mann=5,-1,0
  4037.6     0.1       0  4712.5    0.07       0  4790.9    0.07       0
  4799.8    0.07       0  4942.8     0.1       0
Bank Sta=4790.9,4799.8
Exp/Cntr=0.3,0.1

Type RM Length L Ch R = 1,2382,437,437,437
BEGIN DESCRIPTION:
UNT 024 in RCW 8.0
END DESCRIPTION:
XS GIS Cut Line= 3
      1986737.20     13466037.11      1986531.46     13465011.02
      1985937.70     13464109.97
#Sta/Elev= 30
  3989.9  507.62  4032.8  507.43  4230.8  503.77  4502.0  495.40  4705.7  491.34
  4731.0  491.24  4836.9  489.81  4895.4  490.86  4950.8  490.90  5007.5  489.34
  5008.3  488.54  5015.6  488.54  5016.4  489.34  5031.8  490.94  5044.3  490.97
  5175.4  489.62  5291.3  489.85  5348.5  490.83  5441.9  489.59  5601.5  489.84
  5616.6  490.98  5637.6  490.69  5725.0  493.21  5803.2  496.82  5818.3  496.69
  5869.5  498.86  5953.8  501.09  6041.1  502.78  6056.2  502.16  6115.5  502.97
#Mann=6,-1,0
  3989.9     0.1       0  4705.7    0.07       0  4731.0    0.12       0
  4895.4     0.1       0  5007.5    0.07       0  5016.4     0.1       0
Bank Sta=5007.5,5016.4
Exp/Cntr=0.3,0.1

Type RM Length L Ch R = 1,1945,719,719,719
BEGIN DESCRIPTION:
UNT 024 in RCW 7.0
END DESCRIPTION:
XS GIS Cut Line= 3
      1987578.33     13465641.23      1987025.00     13465025.00
      1986092.45     13463658.47
#Sta/Elev= 30
  3904.9  503.85  4195.3  497.57  4293.9  496.60  4322.3  495.64  4329.8  496.06
  4336.5  495.36  4436.0  493.16  4456.9  492.10  4548.8  491.05  4690.9  487.47
  4719.3  487.49  4729.7  486.18  4742.2  485.92  4743.0  485.12  4750.3  485.12
  4751.1  485.92  4761.5  487.76  4818.4  489.36  4854.3  488.74  4949.9  489.71
  5006.8  487.81  5035.8  489.03  5156.8  488.21  5359.7  489.53  5495.8  488.42
  5646.9  488.89  5841.4  491.09  6035.8  492.32  6287.1  495.24  6387.5  497.11
#Mann=3,-1,0
  3904.9     0.1       0  4742.2    0.07       0  4751.1     0.1       0
Bank Sta=4742.2,4751.1
Exp/Cntr=0.3,0.1

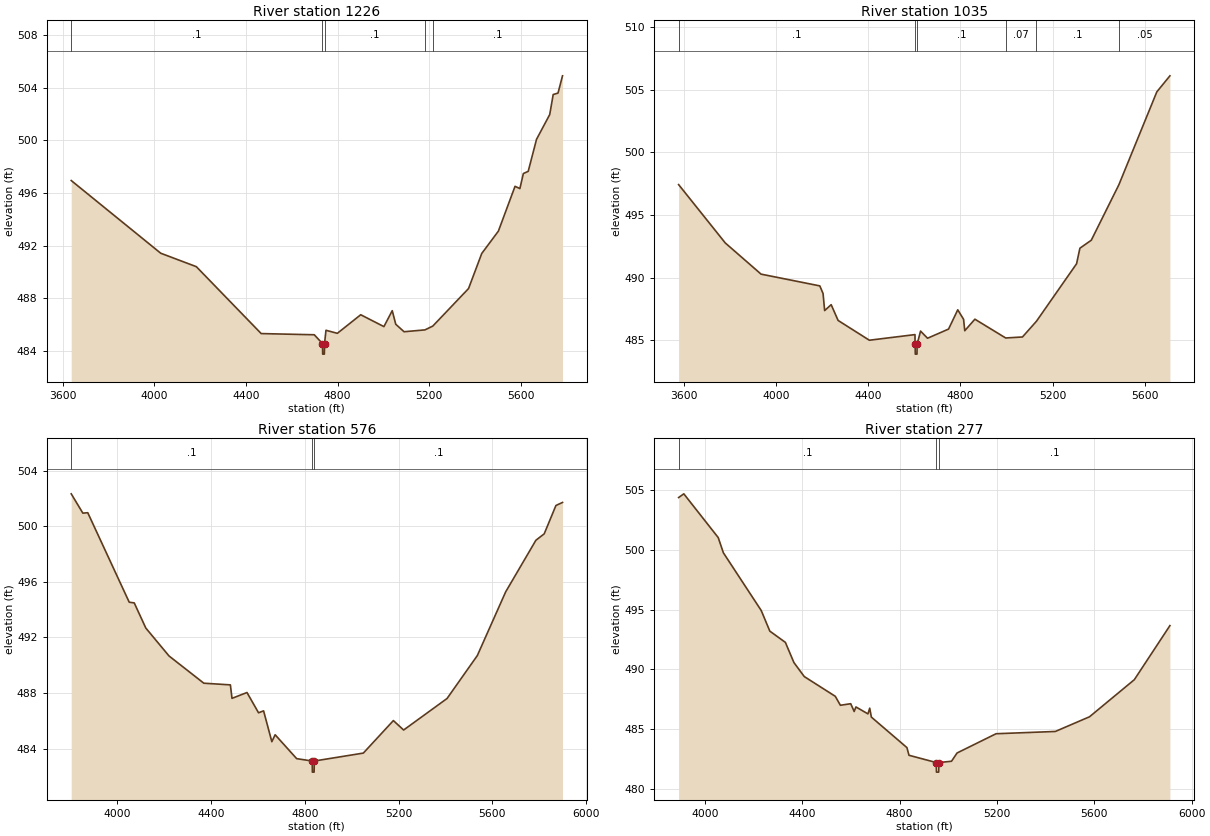
Type RM Length L Ch R = 1,1226,191,191,191
BEGIN DESCRIPTION:
UNT 024 in RCW 6.0
END DESCRIPTION:
XS GIS Cut Line= 4
      1988580.95     13465042.28      1988064.44     13464540.97
      1987456.81     13464460.68      1987019.21     13463773.96
#Sta/Elev= 30
  3636.3  496.94  4027.5  491.42  4183.1  490.40  4466.5  485.32  4698.5  485.23
  4734.3  484.56  4735.2  483.76  4742.5  483.76  4743.3  484.56  4749.6  485.57
  4799.3  485.34  4901.5  486.75  5002.8  485.85  5039.2  487.06  5054.5  486.03
  5090.9  485.46  5182.1  485.60  5216.5  485.89  5372.7  488.74  5430.3  491.40
  5503.1  493.10  5575.8  496.50  5597.0  496.33  5612.2  497.47  5633.4  497.64
  5669.8  500.07  5727.4  501.95  5742.6  503.47  5763.7  503.58  5783.3  504.89
#Mann=5,-1,0
  3636.3     0.1       0  4734.3    0.07       0  4743.3     0.1       0
  5182.1    0.07       0  5216.5     0.1       0
Bank Sta=4734.3,4743.3
Exp/Cntr=0.3,0.1

Type RM Length L Ch R = 1,1035,459,459,459
BEGIN DESCRIPTION:
UNT 024 in RCW 5.0
END DESCRIPTION:
XS GIS Cut Line= 5
      1988667.75     13464968.50      1988157.76     13464497.57
      1987585.09     13464414.97      1987489.36     13464237.15
      1987075.00     13463724.99
#Sta/Elev= 30
  3576.1  497.43  3778.7  492.77  3934.1  490.28  4189.3  489.34  4203.4  488.73
  4210.2  487.37  4238.6  487.84  4268.7  486.58  4404.4  485.00  4602.5  485.45
  4603.0  484.69  4603.9  483.89  4611.2  483.89  4612.0  484.69  4626.7  485.73
  4657.0  485.16  4748.3  485.89  4788.3  487.43  4813.6  486.67  4818.7  485.76
  4862.7  486.68  4996.4  485.18  5069.3  485.26  5129.8  486.51  5304.3  491.11
  5318.7  492.35  5368.2  492.99  5488.0  497.42  5652.8  504.84  5709.6  506.12
#Mann=6,-1,0
  3576.1     0.1       0  4603.0    0.07       0  4612.0     0.1       0
  4996.4    0.07       0  5129.8     0.1       0  5488.0    0.05       0
Bank Sta=4603,4612
Exp/Cntr=0.3,0.1

Type RM Length L Ch R = 1,576,299,299,299
BEGIN DESCRIPTION:
UNT 024 in RCW 4.0
END DESCRIPTION:
XS GIS Cut Line= 3
      1988825.03     13465025.03      1988025.00     13464275.00
      1987225.02     13463675.02
#Sta/Elev= 30
  3802.6  502.34  3852.2  500.95  3873.2  500.98  4050.1  494.54  4071.5  494.49
  4120.9  492.68  4220.0  490.67  4368.5  488.71  4481.8  488.59  4488.7  487.62
  4552.7  488.04  4602.0  486.58  4623.5  486.72  4658.7  484.50  4672.8  485.00
  4764.7  483.28  4831.0  483.11  4831.8  482.31  4839.1  482.31  4840.0  483.11
  5049.2  483.68  5177.4  486.02  5221.1  485.34  5406.5  487.61  5535.7  490.70
  5656.5  495.28  5785.7  499.00  5821.1  499.46  5871.1  501.50  5899.2  501.72
#Mann=3,-1,0
  3802.6     0.1       0  4831.0    0.07       0  4840.0     0.1       0
Bank Sta=4831,4840
Exp/Cntr=0.3,0.1

Type RM Length L Ch R = 1,277,0,0,0
BEGIN DESCRIPTION:
UNT 024 in RCW 3.0
END DESCRIPTION:
XS GIS Cut Line= 3
      1988975.03     13465025.03      1988387.79     13464467.19
      1987799.85     13463410.62
#Sta/Elev= 30
  3891.5  504.37  3912.8  504.68  4054.3  501.02  4075.4  499.75  4231.1  494.92
  4266.3  493.20  4330.2  492.26  4365.4  490.57  4407.9  489.40  4535.3  487.75
  4556.3  487.00  4598.8  487.13  4613.0  486.48  4620.2  486.86  4669.6  486.28
  4676.8  486.76  4683.7  486.01  4829.8  483.46  4838.2  482.82  4950.4  482.21
  4951.2  481.41  4960.3  481.41  4961.1  482.21  5013.0  482.32  5035.8  483.01
  5196.1  484.62  5439.7  484.81  5580.3  486.04  5764.4  489.14  5910.6  493.66
#Mann=3,-1,0
  3891.5     0.1       0  4950.4    0.07       0  4961.1     0.1       0
Bank Sta=4950.4,4961.1
Exp/Cntr=0.3,0.1

Chan Stop Cuts=-1