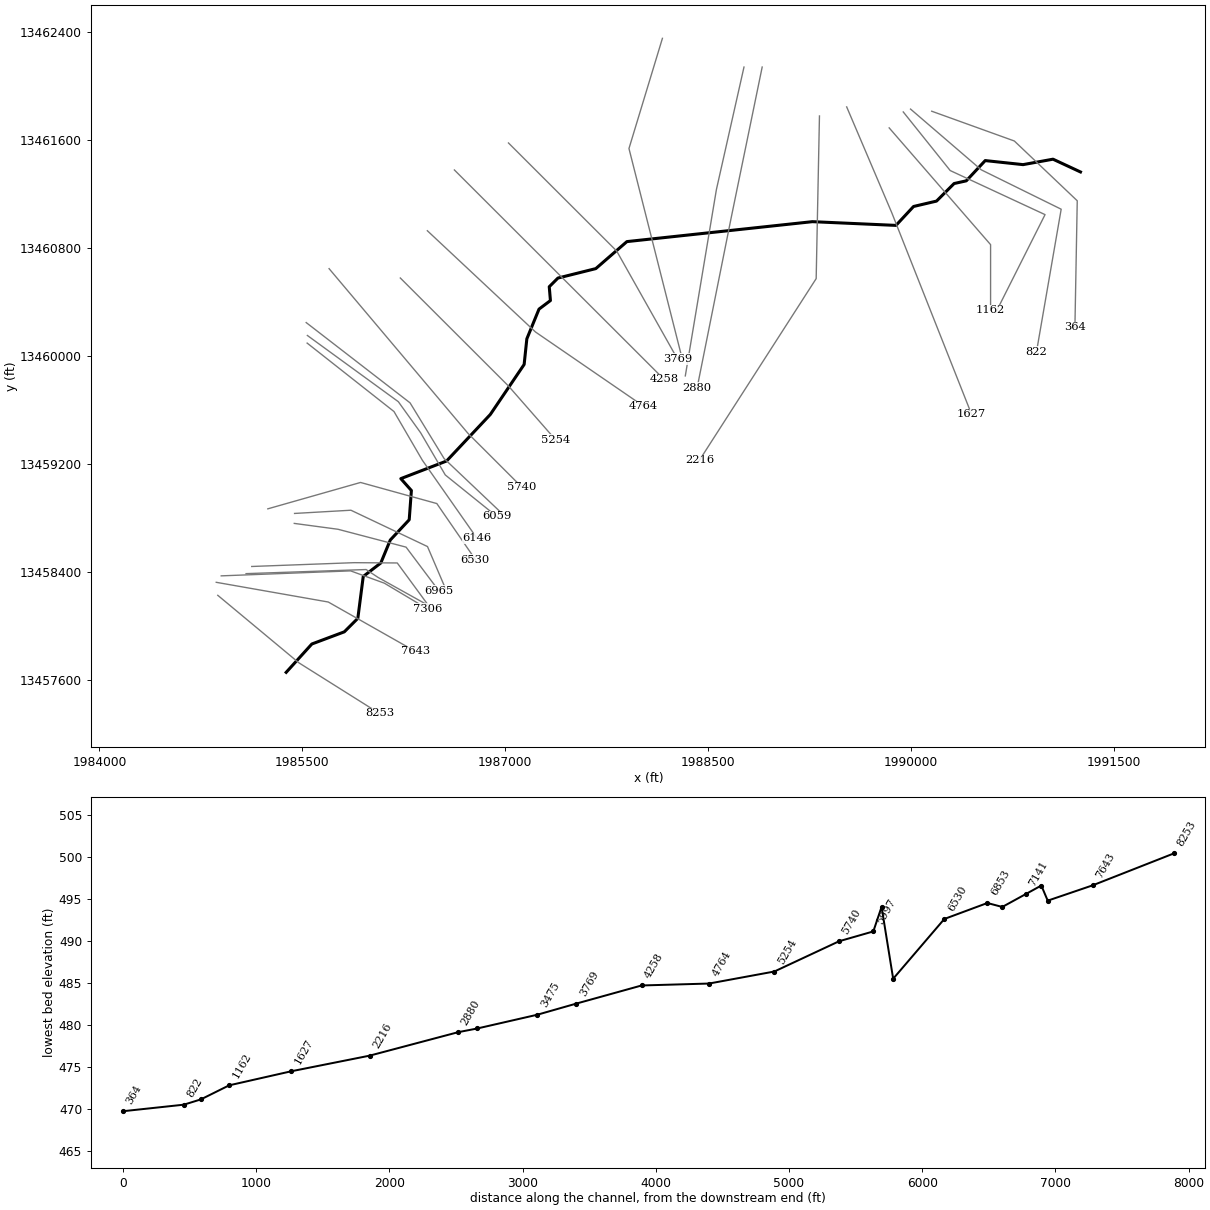
--- UNT 027 in RCW.prj (project) ---

Proj Title=UNT 027 in RCW Base Level Engineering
Current Plan=p01
Default Exp/Contr=0.3,0.1
English Units
Geom File=g01
Flow File=f01
Plan File=p01
BEGIN DESCRIPTION:
UNT 027 in RCW
END DESCRIPTION:

--- UNT 027 in RCW.p01 (plan) ---

Plan Title=Multiple Run
Short Identifier=Multiple
Geom File=g01
Flow File=f01
Subcritical Flow
K Sum by GR= 0
Std Step Tol= 0.01
Critical Tol= 0.01
Num of Std Step Trials= 20
Max Error Tol= 0.3
Flow Tol Ratio= 0.001
Split Flow NTrial= 30
Split Flow Tol= 0.02
Split Flow Ratio= 0.02
Log Output Level= 0
Friction Slope Method= 1
Unsteady Friction Slope Method= 2
Unsteady Bridges Friction Slope Method= 1
Parabolic Critical Depth
Global Vel Dist=  1 , 1 , 1
Global Log Level= 0
CheckData=True
Encroach Param= -1, 0, 0, 0
BEGIN DESCRIPTION:
Multiple Run
END DESCRIPTION:

--- UNT 027 in RCW.f01 (steady flow) ---

Flow Title=Multiple
Number of Profiles=7
Profile Names=10-year,25-year,50-year,1pct_min,100-year,1pct_plu,500-year
River Rch & RM= UNT 027 in RCW,Reach-1,8253
     175     239     292     178     355     708     532
River Rch & RM= UNT 027 in RCW,Reach-1,6146
     294     414     515     319     637    1271     991
River Rch & RM= UNT 027 in RCW,Reach-1,4258
     321     452     562     348     695    1386    1079
Boundary for River Rch & Prof#=UNT 027 in RCW,Reach-1,1
Up Type=0
Dn Type=3
Dn Slope=0.005
Boundary for River Rch & Prof#=UNT 027 in RCW,Reach-1,2
Up Type=0
Dn Type=3
Dn Slope=0.005
Boundary for River Rch & Prof#=UNT 027 in RCW,Reach-1,3
Up Type=0
Dn Type=3
Dn Slope=0.005
Boundary for River Rch & Prof#=UNT 027 in RCW,Reach-1,4
Up Type=0
Dn Type=3
Dn Slope=0.005
Boundary for River Rch & Prof#=UNT 027 in RCW,Reach-1,5
Up Type=0
Dn Type=3
Dn Slope=0.005
Boundary for River Rch & Prof#=UNT 027 in RCW,Reach-1,6
Up Type=0
Dn Type=3
Dn Slope=0.005
Boundary for River Rch & Prof#=UNT 027 in RCW,Reach-1,7
Up Type=0
Dn Type=3
Dn Slope=0.005

--- UNT 027 in RCW.g01 (geometry) ---

Geom Title=Existing Conditions

River Reach=UNT 027 in RCW,Reach-1
Reach XY= 30
      1985380.80     13457654.54      1985570.80     13457864.54
      1985810.80     13457954.54      1985910.80     13458054.54
      1985950.80     13458364.54      1986080.80     13458464.54
      1986150.80     13458634.54      1986290.80     13458784.54
      1986306.90     13459001.26      1986228.78     13459089.15
      1986566.96     13459219.58      1986890.80     13459564.54
      1987140.80     13459934.54      1987160.80     13460124.54
      1987250.80     13460344.54      1987335.19     13460407.94
      1987326.57     13460510.31      1987390.80     13460574.54
      1987670.80     13460644.54      1987900.80     13460844.54
      1989272.69     13460992.15      1989890.80     13460964.54
      1990020.80     13461104.54      1990190.80     13461144.54
      1990320.80     13461274.54      1990410.80     13461294.54
      1990550.80     13461444.54      1990830.80     13461414.54
      1991052.33     13461454.84      1991255.45     13461360.22

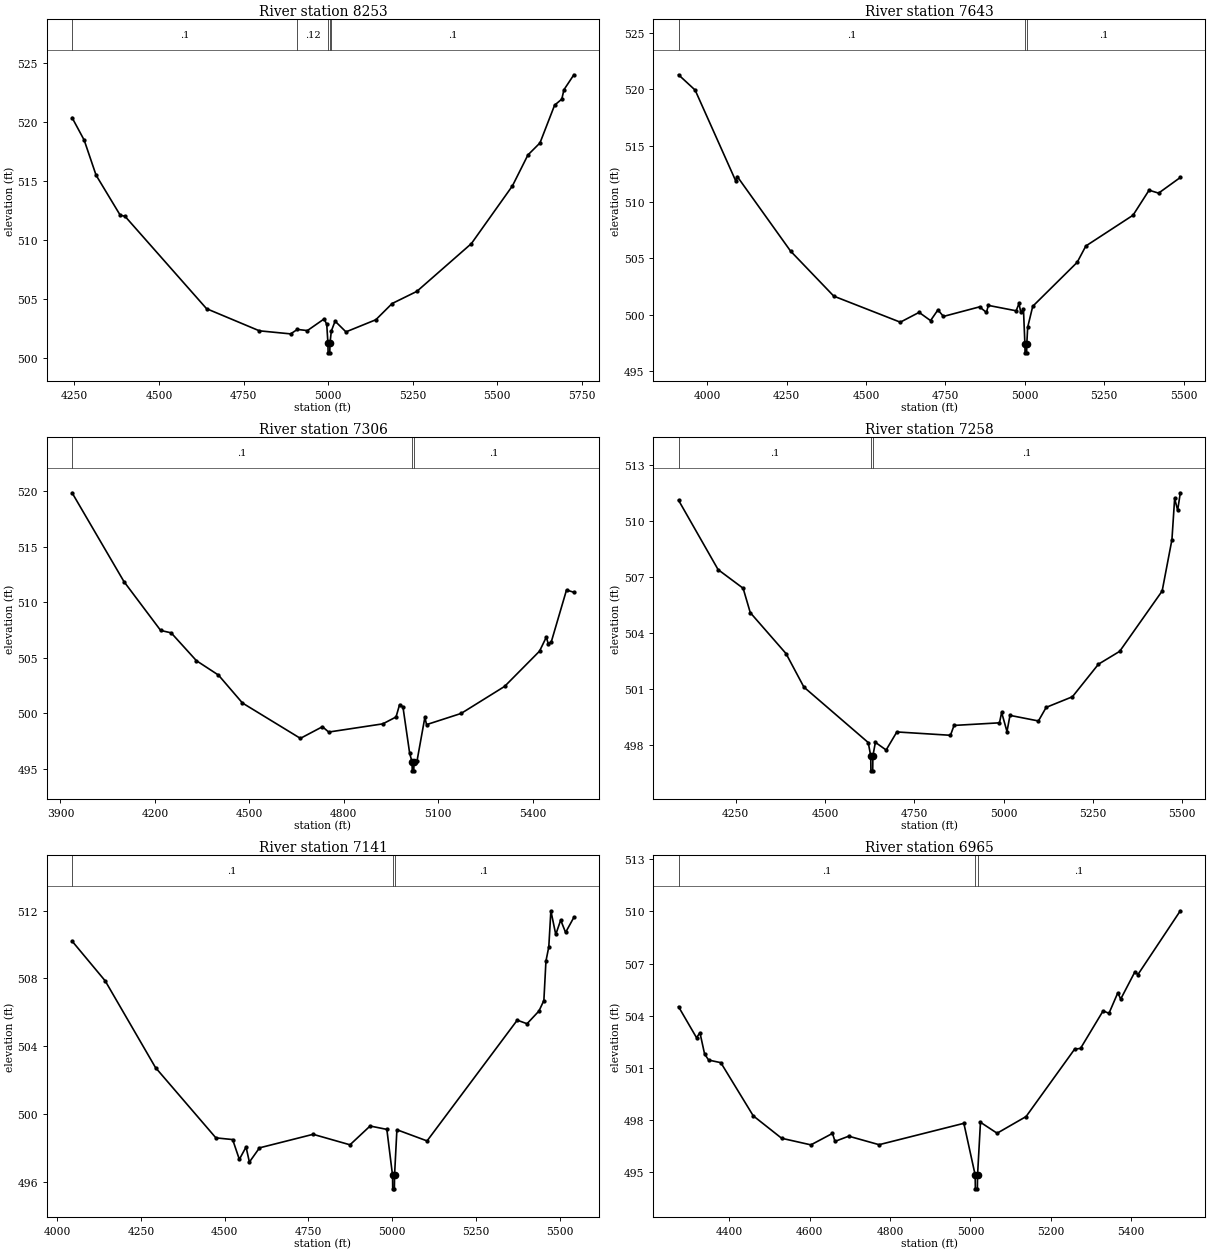
Type RM Length L Ch R = 1,8253,610,610,610
BEGIN DESCRIPTION:
UNT 027 in RCW 17.0
END DESCRIPTION:
XS GIS Cut Line= 3
      1984874.98     13458225.02      1985475.00     13457725.00
      1986069.78     13457350.71
#Sta/Elev= 30
  4242.9  520.39  4278.7  518.48  4313.9  515.50  4385.5  512.09  4399.1  512.02
  4640.6  504.16  4796.8  502.28  4889.2  502.02  4909.1  502.40  4938.7  502.30
  4988.2  503.29  4996.0  502.83  4999.5  501.21  5000.0  500.41  5005.0  500.41
  5005.5  501.21  5009.5  502.26  5020.7  503.10  5052.8  502.19  5141.1  503.22
  5189.4  504.60  5262.4  505.63  5423.7  509.69  5545.0  514.59  5590.9  517.22
  5626.5  518.24  5669.8  521.45  5691.0  521.96  5697.4  522.76  5726.7  524.03
#Mann=5,-1,0
  4242.9     0.1       0  4909.1    0.12       0  4999.5    0.07       0
  5005.5    0.12       0  5009.5     0.1       0
Bank Sta=4999.5,5005.5
Exp/Cntr=0.3,0.1

Type RM Length L Ch R = 1,7643,337,337,337
BEGIN DESCRIPTION:
UNT 027 in RCW 16.0
END DESCRIPTION:
XS GIS Cut Line= 3
      1984863.53     13458321.36      1985692.16     13458175.38
      1986334.52     13457810.79
#Sta/Elev= 30
  3909.6  521.28  3961.9  519.92  4089.6  511.87  4094.6  512.25  4262.3  505.64
  4398.5  501.64  4607.9  499.33  4667.1  500.20  4703.1  499.47  4726.4  500.42
  4743.7  499.84  4857.6  500.69  4879.2  500.19  4885.0  500.82  4972.7  500.34
  4981.6  500.99  4987.3  500.20  4995.7  500.47  5000.2  497.41  5000.7  496.61
  5005.7  496.61  5006.2  497.41  5009.0  498.89  5024.9  500.74  5164.8  504.64
  5192.1  506.09  5340.7  508.82  5391.2  511.04  5421.2  510.78  5489.6  512.17
#Mann=3,-1,0
  3909.6     0.1       0  5000.2    0.07       0  5006.2     0.1       0
Bank Sta=5000.2,5006.2
Exp/Cntr=0.3,0.1

Type RM Length L Ch R = 1,7306,48,48,48
BEGIN DESCRIPTION:
UNT 027 in RCW 15.0
END DESCRIPTION:
XS GIS Cut Line= 4
      1984900.38     13458369.11      1985857.43     13458406.00
      1986107.00     13458314.86      1986424.99     13458125.01
#Sta/Elev= 30
  3937.1  519.88  4101.8  511.87  4218.4  507.46  4251.9  507.24  4332.0  504.73
  4402.1  503.43  4478.3  500.91  4662.3  497.72  4732.3  498.77  4752.3  498.29
  4924.2  499.03  4966.1  499.65  4977.4  500.77  4988.1  500.55  5009.4  496.37
  5017.0  495.59  5017.5  494.79  5022.5  494.79  5023.0  495.59  5032.5  495.64
  5057.7  499.62  5063.0  498.96  5172.9  499.97  5311.0  502.41  5421.9  505.59
  5443.3  506.85  5449.4  506.28  5458.9  506.40  5507.6  511.11  5530.9  510.90
#Mann=3,-1,0
  3937.1     0.1       0  5017.0    0.07       0  5023.0     0.1       0
Bank Sta=5017,5023
Exp/Cntr=0.3,0.1

Type RM Length L Ch R = 1,7258,117,117,117
BEGIN DESCRIPTION:
Mapping XS 7cb79de9
END DESCRIPTION:
XS GIS Cut Line= 4
      1985084.28     13458385.57      1985971.82     13458415.95
      1986060.79     13458357.35      1986418.89     13458157.68
#Sta/Elev= 30
  4090.0  511.13  4200.8  507.40  4270.8  506.40  4290.8  505.09  4390.9  502.89
  4440.9  501.09  4621.0  498.11  4628.0  497.39  4628.5  496.59  4633.5  496.59
  4634.0  497.39  4641.0  498.12  4671.1  497.71  4701.1  498.68  4851.2  498.50
  4861.2  499.03  4988.4  499.17  4994.4  499.73  5009.4  498.70  5017.8  499.57
  5097.4  499.27  5119.1  500.00  5192.5  500.57  5265.4  502.32  5324.8  503.01
  5443.7  506.25  5471.1  509.01  5478.7  511.23  5487.1  510.59  5494.6  511.53
#Mann=3,-1,0
  4090.0     0.1       0  4628.0    0.07       0  4634.0     0.1       0
Bank Sta=4628,4634
Exp/Cntr=0.3,0.1

Type RM Length L Ch R = 1,7141,176,176,176
BEGIN DESCRIPTION:
Mapping XS 30c99afa
END DESCRIPTION:
XS GIS Cut Line= 4
      1985126.13     13458438.56      1985883.47     13458466.77
      1986202.48     13458464.60      1986451.03     13458125.27
#Sta/Elev= 30
  4044.8  510.20  4143.7  507.85  4293.8  502.73  4474.0  498.58  4524.0  498.48
  4544.0  497.31  4564.0  498.04  4574.0  497.15  4604.1  497.99  4764.2  498.79
  4874.2  498.17  4934.2  499.28  4984.2  499.08  5001.2  496.37  5001.7  495.57
  5006.7  495.57  5007.2  496.37  5014.2  499.06  5104.2  498.40  5373.3  505.53
  5402.6  505.32  5438.1  506.07  5452.8  506.69  5459.0  509.02  5467.5  509.86
  5473.7  511.99  5488.3  510.59  5503.0  511.44  5517.6  510.71  5542.3  511.60
#Mann=3,-1,0
  4044.8     0.1       0  5001.2    0.07       0  5007.2     0.1       0
Bank Sta=5001.2,5007.2
Exp/Cntr=0.3,0.1

Type RM Length L Ch R = 1,6965,112,112,112
BEGIN DESCRIPTION:
Mapping XS bb2269cd
END DESCRIPTION:
XS GIS Cut Line= 4
      1985440.74     13458757.57      1985764.11     13458714.16
      1986267.59     13458581.78      1986508.45     13458260.63
#Sta/Elev= 30
  4273.9  504.52  4318.6  502.74  4327.2  503.02  4338.7  501.80  4348.8  501.45
  4379.1  501.30  4459.8  498.24  4530.4  496.95  4603.2  496.57  4656.9  497.23
  4663.1  496.77  4697.3  497.07  4772.8  496.58  4983.7  497.81  5011.8  494.84
  5012.3  494.04  5017.3  494.04  5017.8  494.84  5025.0  497.87  5066.4  497.24
  5138.5  498.20  5259.3  502.08  5273.9  502.12  5330.1  504.28  5344.7  504.14
  5366.7  505.32  5373.9  504.96  5409.3  506.53  5416.7  506.37  5522.2  510.04
#Mann=3,-1,0
  4273.9     0.1       0  5011.8    0.07       0  5017.8     0.1       0
Bank Sta=5011.8,5017.8
Exp/Cntr=0.3,0.1

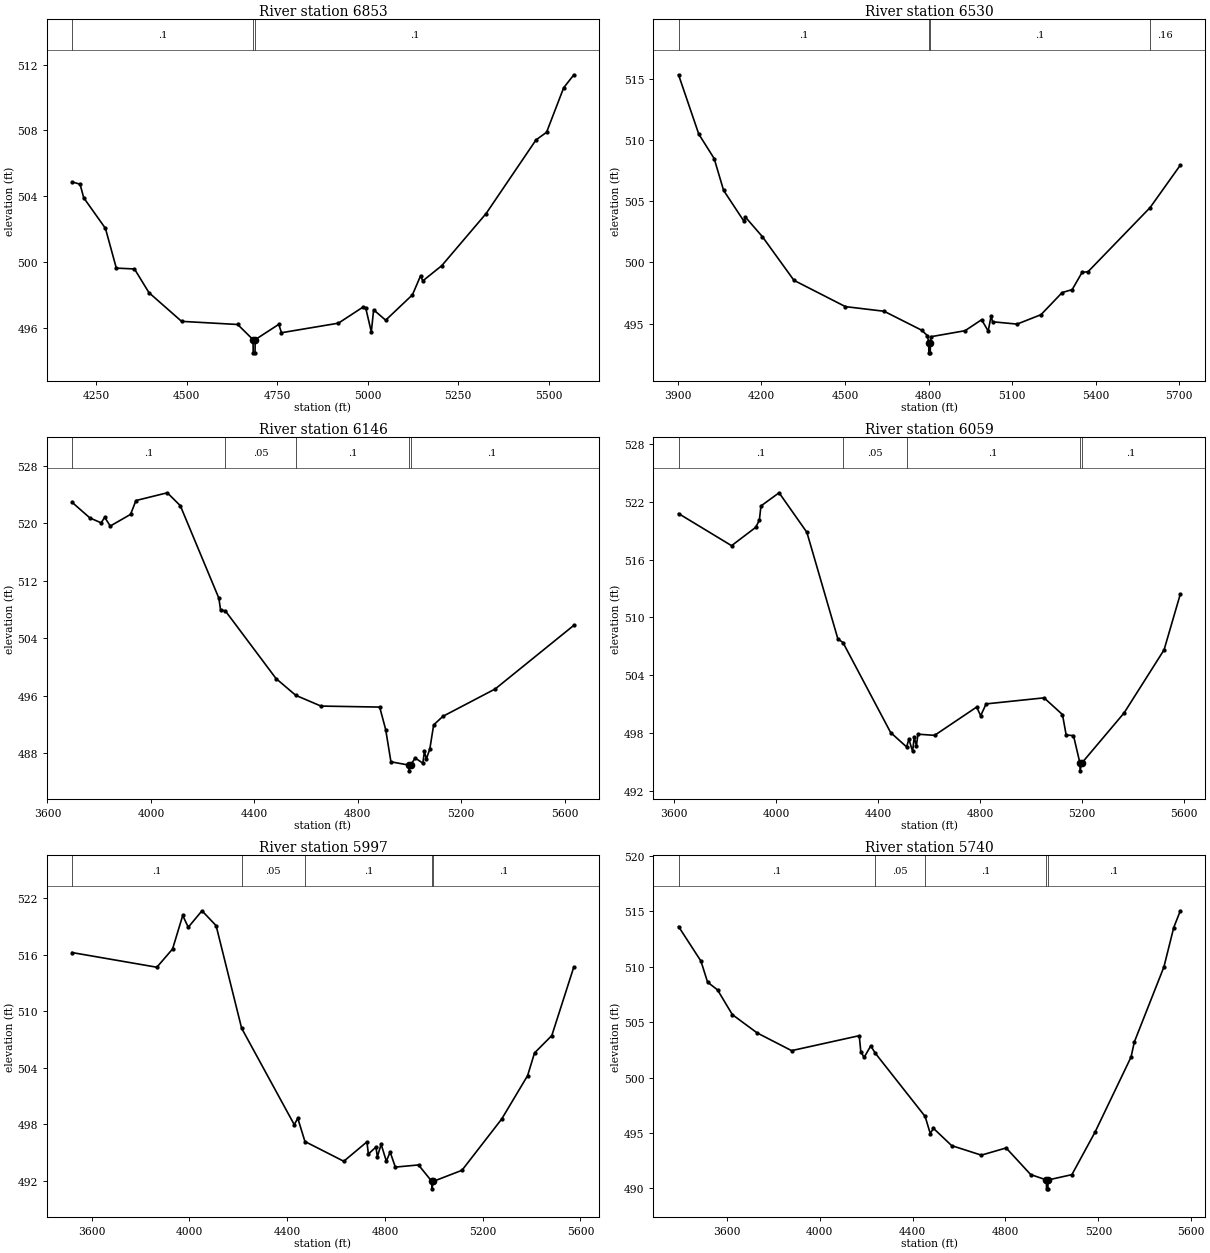
Type RM Length L Ch R = 1,6853,323,323,323
BEGIN DESCRIPTION:
Mapping XS 9a25eb86
END DESCRIPTION:
XS GIS Cut Line= 4
      1985442.98     13458831.35      1985859.60     13458855.22
      1986426.01     13458586.12      1986560.28     13458272.11
#Sta/Elev= 30
  4183.5  504.88  4205.6  504.74  4215.6  503.92  4275.7  502.06  4305.7  499.65
  4355.8  499.60  4395.9  498.16  4486.0  496.42  4640.9  496.23  4683.3  495.31
  4683.8  494.51  4688.8  494.51  4689.3  495.31  4754.5  496.24  4761.8  495.73
  4919.1  496.31  4987.3  497.29  4994.3  497.25  5010.0  495.78  5016.4  497.12
  5049.6  496.49  5123.6  498.03  5146.3  499.20  5151.9  498.87  5204.6  499.80
  5327.0  502.96  5464.9  507.43  5494.0  507.89  5541.2  510.59  5569.4  511.38
#Mann=3,-1,0
  4183.5     0.1       0  4683.3    0.07       0  4689.3     0.1       0
Bank Sta=4683.3,4689.3
Exp/Cntr=0.3,0.1

Type RM Length L Ch R = 1,6530,384,384,384
BEGIN DESCRIPTION:
UNT 027 in RCW 14.0
END DESCRIPTION:
XS GIS Cut Line= 4
      1985245.15     13458865.49      1985930.87     13459060.79
      1986495.11     13458904.54      1986780.04     13458490.10
#Sta/Elev= 30
  3902.5  515.35  3975.1  510.50  4030.4  508.50  4064.2  505.90  4137.1  503.38
  4142.3  503.72  4203.9  502.10  4316.8  498.54  4501.6  496.39  4640.5  496.01
  4775.4  494.46  4796.2  494.01  4800.6  493.41  4801.1  492.61  4806.1  492.61
  4806.6  493.41  4808.8  493.93  4931.1  494.42  4990.6  495.32  5014.1  494.39
  5024.5  495.60  5030.1  495.15  5117.8  494.96  5203.7  495.73  5279.7  497.54
  5315.6  497.78  5351.5  499.20  5372.4  499.24  5595.4  504.49  5703.9  507.96
#Mann=4,-1,0
  3902.5     0.1       0  4800.6    0.07       0  4806.6     0.1       0
  5595.4    0.16       0
Bank Sta=4800.6,4806.6
Exp/Cntr=0.3,0.1

Type RM Length L Ch R = 1,6146,87,87,87
BEGIN DESCRIPTION:
UNT 027 in RCW 13.0
END DESCRIPTION:
XS GIS Cut Line= 4
      1985535.90     13460092.92      1986178.27     13459585.97
      1986388.34     13459224.85      1986792.00     13458647.57
#Sta/Elev= 30
  3695.2  522.94  3764.3  520.76  3807.6  520.08  3821.4  520.85  3842.9  519.63
  3921.4  521.26  3942.3  523.19  4063.5  524.27  4113.8  522.47  4262.9  509.57
  4269.3  507.97  4288.5  507.78  4483.9  498.37  4560.2  496.03  4657.7  494.53
  4884.8  494.39  4908.0  491.25  4928.3  486.76  4997.7  486.30  4998.2  485.50
  5004.6  486.30  5022.0  487.30  5051.7  486.56  5057.8  488.21  5065.3  487.15
  5078.7  488.55  5093.5  491.90  5129.3  493.10  5331.6  496.92  5635.7  505.79
#Mann=5,-1,0
  3695.2     0.1       0  4288.5    0.05       0  4560.2     0.1       0
  4997.7    0.07       0  5004.6     0.1       0
Bank Sta=4997.7,5004.6
Exp/Cntr=0.3,0.1

Type RM Length L Ch R = 1,6059,62,62,62
BEGIN DESCRIPTION:
Mapping XS b2aff1a5
END DESCRIPTION:
XS GIS Cut Line= 5
      1985537.63     13460149.34      1986210.39     13459658.88
      1986375.32     13459428.85      1986557.61     13459116.35
      1986938.43     13458809.10
#Sta/Elev= 30
  3617.8  520.80  3825.7  517.46  3920.0  519.36  3934.7  520.12  3940.8  521.59
  4011.9  522.96  4120.8  518.85  4242.1  507.79  4262.7  507.37  4449.2  498.03
  4511.5  496.54  4520.6  497.33  4535.3  496.07  4541.5  497.55  4550.0  496.64
  4556.2  497.86  4621.3  497.74  4786.2  500.68  4801.9  499.78  4823.4  501.01
  5050.4  501.64  5122.6  499.90  5137.0  497.78  5165.8  497.71  5191.1  494.85
  5191.6  494.05  5198.0  494.85  5364.1  500.07  5520.8  506.63  5584.5  512.43
#Mann=5,-1,0
  3617.8     0.1       0  4262.7    0.05       0  4511.5     0.1       0
  5191.1    0.07       0  5198.0     0.1       0
Bank Sta=5191.1,5198
Exp/Cntr=0.3,0.1

Type RM Length L Ch R = 1,5997,257,257,257
BEGIN DESCRIPTION:
Mapping XS 91a703b5
END DESCRIPTION:
XS GIS Cut Line= 4
      1985528.93     13460244.84      1986297.19     13459650.20
      1986548.93     13459237.88      1986982.98     13458825.52
#Sta/Elev= 30
  3519.8  516.24  3866.7  514.68  3931.0  516.62  3972.6  520.18  3995.3  518.93
  4051.4  520.68  4109.2  519.10  4213.6  508.20  4429.0  497.95  4443.4  498.63
  4472.7  496.16  4631.6  494.06  4726.4  496.12  4732.3  494.83  4763.2  495.57
  4769.0  494.54  4784.5  495.86  4805.8  494.07  4821.3  495.04  4842.6  493.44
  4937.4  493.67  4991.6  491.93  4992.1  491.13  4998.5  491.93  5115.2  493.10
  5277.8  498.55  5383.8  503.16  5412.1  505.57  5482.9  507.42  5573.1  514.72
#Mann=5,-1,0
  3519.8     0.1       0  4213.6    0.05       0  4472.7     0.1       0
  4991.6    0.07       0  4998.5     0.1       0
Bank Sta=4991.6,4998.5
Exp/Cntr=0.3,0.1

Type RM Length L Ch R = 1,5740,486,486,486
BEGIN DESCRIPTION:
UNT 027 in RCW 12.0
END DESCRIPTION:
XS GIS Cut Line= 3
      1985698.23     13460644.13      1986725.00     13459425.00
      1987125.01     13459024.99
#Sta/Elev= 30
  3393.0  513.63  3489.4  510.51  3518.0  508.61  3560.9  507.91  3624.6  505.68
  3731.3  504.03  3879.6  502.43  4170.8  503.78  4177.4  502.34  4191.7  501.82
  4220.3  502.86  4239.4  502.21  4454.3  496.49  4476.4  494.95  4490.1  495.42
  4568.5  493.86  4696.2  493.00  4802.9  493.65  4908.5  491.25  4976.3  490.76
  4976.8  489.96  4982.7  489.96  4983.2  490.76  5085.9  491.24  5184.9  495.05
  5340.5  501.85  5354.6  503.21  5481.9  509.98  5524.3  513.54  5552.6  515.05
#Mann=5,-1,0
  3393.0     0.1       0  4239.4    0.05       0  4454.3     0.1       0
  4976.3    0.07       0  4983.2     0.1       0
Bank Sta=4976.3,4983.2
Exp/Cntr=0.3,0.1

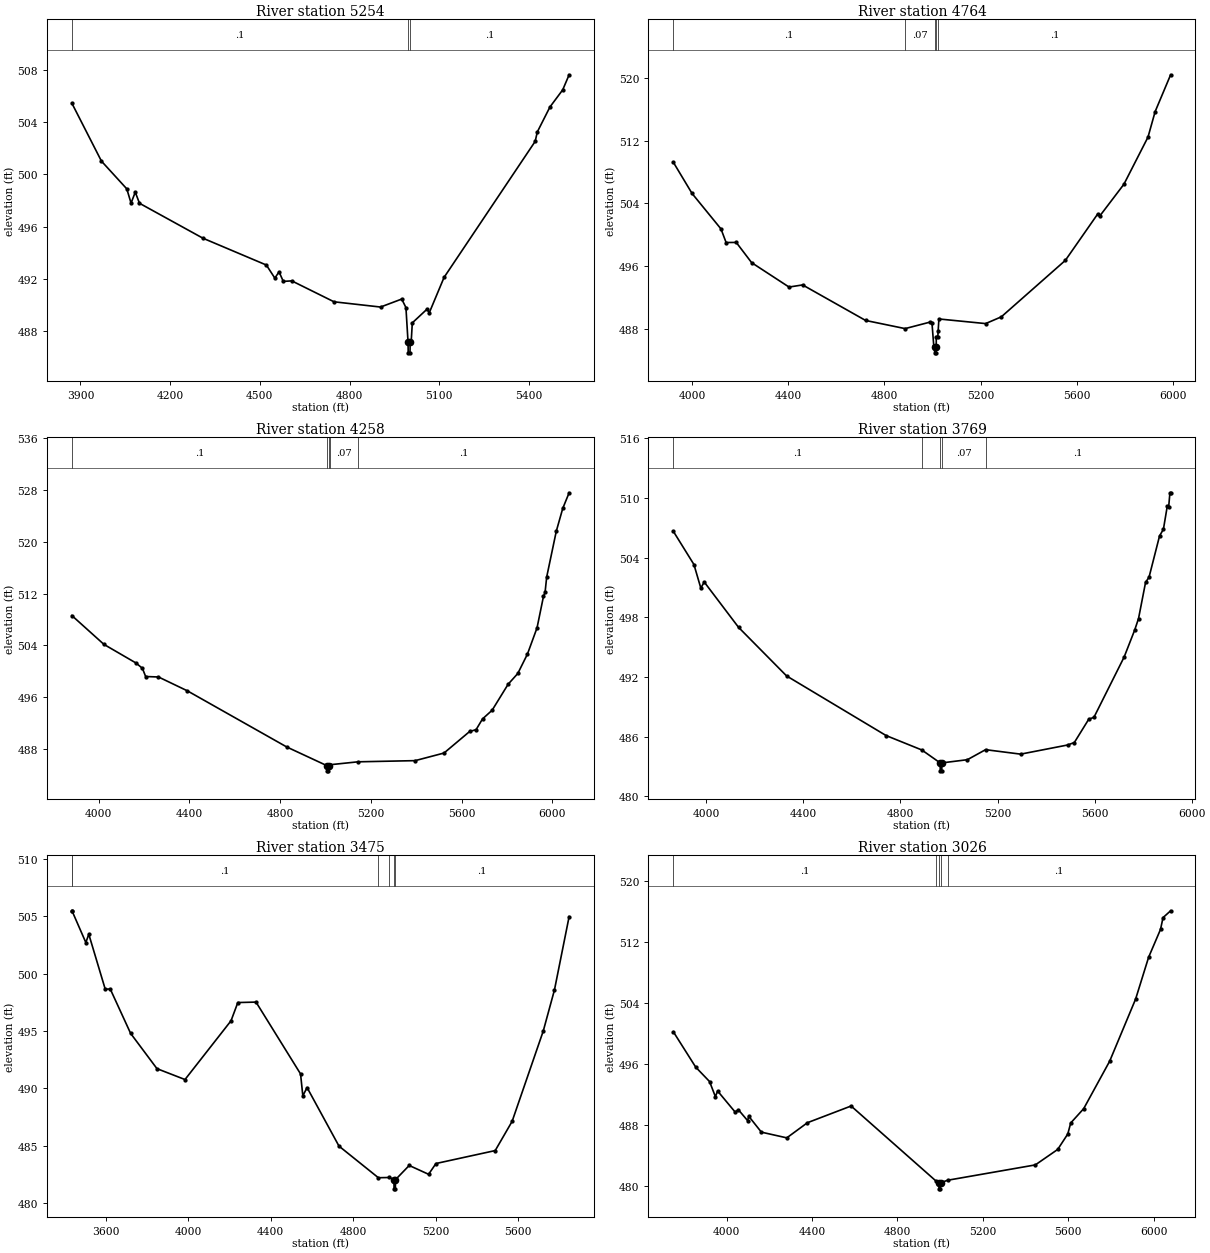
Type RM Length L Ch R = 1,5254,490,490,490
BEGIN DESCRIPTION:
UNT 027 in RCW 11.0
END DESCRIPTION:
XS GIS Cut Line= 3
      1986225.02     13460574.98      1987025.00     13459775.00
      1987375.03     13459374.96
#Sta/Elev= 30
  3871.3  505.44  3970.3  501.01  4055.1  498.89  4069.3  497.80  4083.4  498.64
  4097.5  497.79  4309.7  495.12  4521.8  493.07  4550.1  492.07  4564.2  492.55
  4578.4  491.82  4606.7  491.86  4748.1  490.26  4903.6  489.86  4974.4  490.47
  4988.5  489.82  4995.6  487.16  4996.1  486.36  5002.1  486.36  5002.6  487.16
  5006.0  487.16  5009.8  488.65  5059.1  489.70  5066.7  489.43  5116.1  492.13
  5420.7  502.52  5427.8  503.24  5470.1  505.15  5512.8  506.46  5534.2  507.61
#Mann=3,-1,0
  3871.3     0.1       0  4995.6    0.07       0  5002.6     0.1       0
Bank Sta=4995.6,5002.6
Exp/Cntr=0.3,0.1

Type RM Length L Ch R = 1,4764,506,506,506
BEGIN DESCRIPTION:
UNT 027 in RCW 10.0
END DESCRIPTION:
XS GIS Cut Line= 3
      1986425.01     13460924.99      1987225.00     13460175.00
      1988025.01     13459624.99
#Sta/Elev= 30
  3922.9  509.23  4000.8  505.25  4121.0  500.73  4142.2  499.00  4184.5  499.01
  4248.4  496.43  4403.8  493.32  4460.4  493.59  4722.2  489.06  4886.5  488.02
  4991.4  488.86  4998.2  488.71  5005.5  485.85  5008.9  485.73  5009.4  484.93
  5015.4  484.93  5015.9  485.73  5016.0  487.01  5022.5  487.01  5024.0  487.77
  5026.9  489.25  5221.1  488.66  5286.4  489.52  5552.6  496.72  5687.2  502.64
  5696.0  502.39  5796.1  506.43  5896.2  512.44  5926.0  515.70  5990.3  520.39
#Mann=5,-1,0
  3922.9     0.1       0  4886.5    0.07       0  5008.9    0.07       0
  5015.9    0.07       0  5024.0     0.1       0
Bank Sta=5008.9,5015.9
Exp/Cntr=0.3,0.1

Type RM Length L Ch R = 1,4258,489,489,489
BEGIN DESCRIPTION:
UNT 027 in RCW 9.0
END DESCRIPTION:
XS GIS Cut Line= 3
      1986624.99     13461375.01      1987425.00     13460575.00
      1988174.97     13459825.03
#Sta/Elev= 30
  3882.1  508.61  4023.5  504.17  4165.0  501.30  4193.2  500.48  4207.4  499.22
  4264.0  499.15  4391.2  497.02  4829.6  488.37  5006.3  485.50  5006.9  484.70
  5013.1  484.70  5013.6  485.50  5020.0  485.64  5143.7  486.09  5395.3  486.27
  5522.6  487.44  5635.7  490.76  5664.0  491.04  5692.3  492.69  5734.7  494.03
  5805.4  498.04  5847.9  499.69  5890.3  502.67  5932.7  506.72  5961.0  511.55
  5968.1  512.18  5975.2  514.54  6017.6  521.60  6045.9  525.09  6074.1  527.51
#Mann=5,-1,0
  3882.1     0.1       0  5006.3    0.07       0  5013.6     0.1       0
  5020.0    0.07       0  5143.7     0.1       0
Bank Sta=5006.3,5013.6
Exp/Cntr=0.3,0.1

Type RM Length L Ch R = 1,3769,294,294,294
BEGIN DESCRIPTION:
UNT 027 in RCW 8.0
END DESCRIPTION:
XS GIS Cut Line= 3
      1987024.98     13461575.02      1987825.00     13460775.00
      1988275.01     13459974.98
#Sta/Elev= 30
  3864.0  506.65  3948.9  503.31  3977.2  500.94  3991.3  501.55  4132.7  496.99
  4330.7  492.10  4740.8  486.10  4887.9  484.65  4963.5  483.35  4964.0  482.55
  4970.2  482.55  4970.8  483.35  5075.7  483.67  5150.7  484.68  5295.3  484.23
  5488.8  485.15  5516.5  485.40  5575.8  487.74  5597.4  487.94  5721.7  494.00
  5765.1  496.71  5781.0  497.87  5810.0  501.51  5824.4  502.04  5867.7  506.19
  5883.6  506.86  5899.6  509.20  5905.3  509.12  5910.4  510.53  5913.3  510.53
#Mann=5,-1,0
  3864.0     0.1       0  4887.9    0.07       0  4963.5    0.07       0
  4970.8    0.07       0  5150.7     0.1       0
Bank Sta=4963.5,4970.8
Exp/Cntr=0.3,0.1

Type RM Length L Ch R = 1,3475,449,449,449
BEGIN DESCRIPTION:
Mapping XS 1711c537
END DESCRIPTION:
XS GIS Cut Line= 3
      1988163.51     13462349.86      1987916.11     13461533.88
      1988298.06     13460023.48
#Sta/Elev= 30
  3436.3  505.49  3437.0  505.49  3504.1  502.72  3518.5  503.44  3598.1  498.65
  3622.5  498.66  3721.2  494.79  3848.9  491.71  3984.8  490.76  4208.0  495.89
  4240.9  497.48  4329.1  497.52  4545.0  491.25  4556.0  489.34  4576.6  490.06
  4731.3  484.95  4922.2  482.19  4975.8  482.21  4997.8  482.02  4998.3  481.22
  5004.6  481.22  5005.2  482.02  5071.7  483.26  5165.6  482.49  5201.4  483.43
  5488.6  484.56  5570.6  487.11  5721.6  495.00  5775.8  498.58  5846.9  504.98
#Mann=6,-1,0
  3436.3    0.05       0  3437.0     0.1       0  4922.2    0.12       0
  4975.8     0.1       0  4997.8    0.07       0  5005.2     0.1       0
Bank Sta=4997.8,5005.2
Exp/Cntr=0.3,0.1

Type RM Length L Ch R = 1,3026,146,146,146
BEGIN DESCRIPTION:
UNT 027 in RCW 7.0
END DESCRIPTION:
XS GIS Cut Line= 3
      1988766.82     13462137.23      1988562.82     13461230.06
      1988332.79     13459849.92
#Sta/Elev= 30
  3750.3  500.20  3855.1  495.56  3919.9  493.67  3947.3  491.68  3957.6  492.43
  4039.6  489.67  4054.9  489.97  4098.2  488.54  4103.3  489.12  4162.6  487.03
  4281.6  486.28  4378.4  488.27  4582.8  490.46  4982.3  480.57  4994.2  480.39
  4994.8  479.59  5001.1  479.59  5001.7  480.39  5035.4  480.72  5445.6  482.73
  5550.4  484.76  5597.7  486.79  5611.3  488.23  5672.1  490.11  5793.8  496.34
  5915.4  504.50  5976.2  509.98  6032.0  513.64  6043.7  515.18  6079.3  516.08
#Mann=5,-1,0
  3750.3     0.1       0  4982.3    0.12       0  4994.2    0.07       0
  5001.7    0.12       0  5035.4     0.1       0
Bank Sta=4994.2,5001.7
Exp/Cntr=0.3,0.1

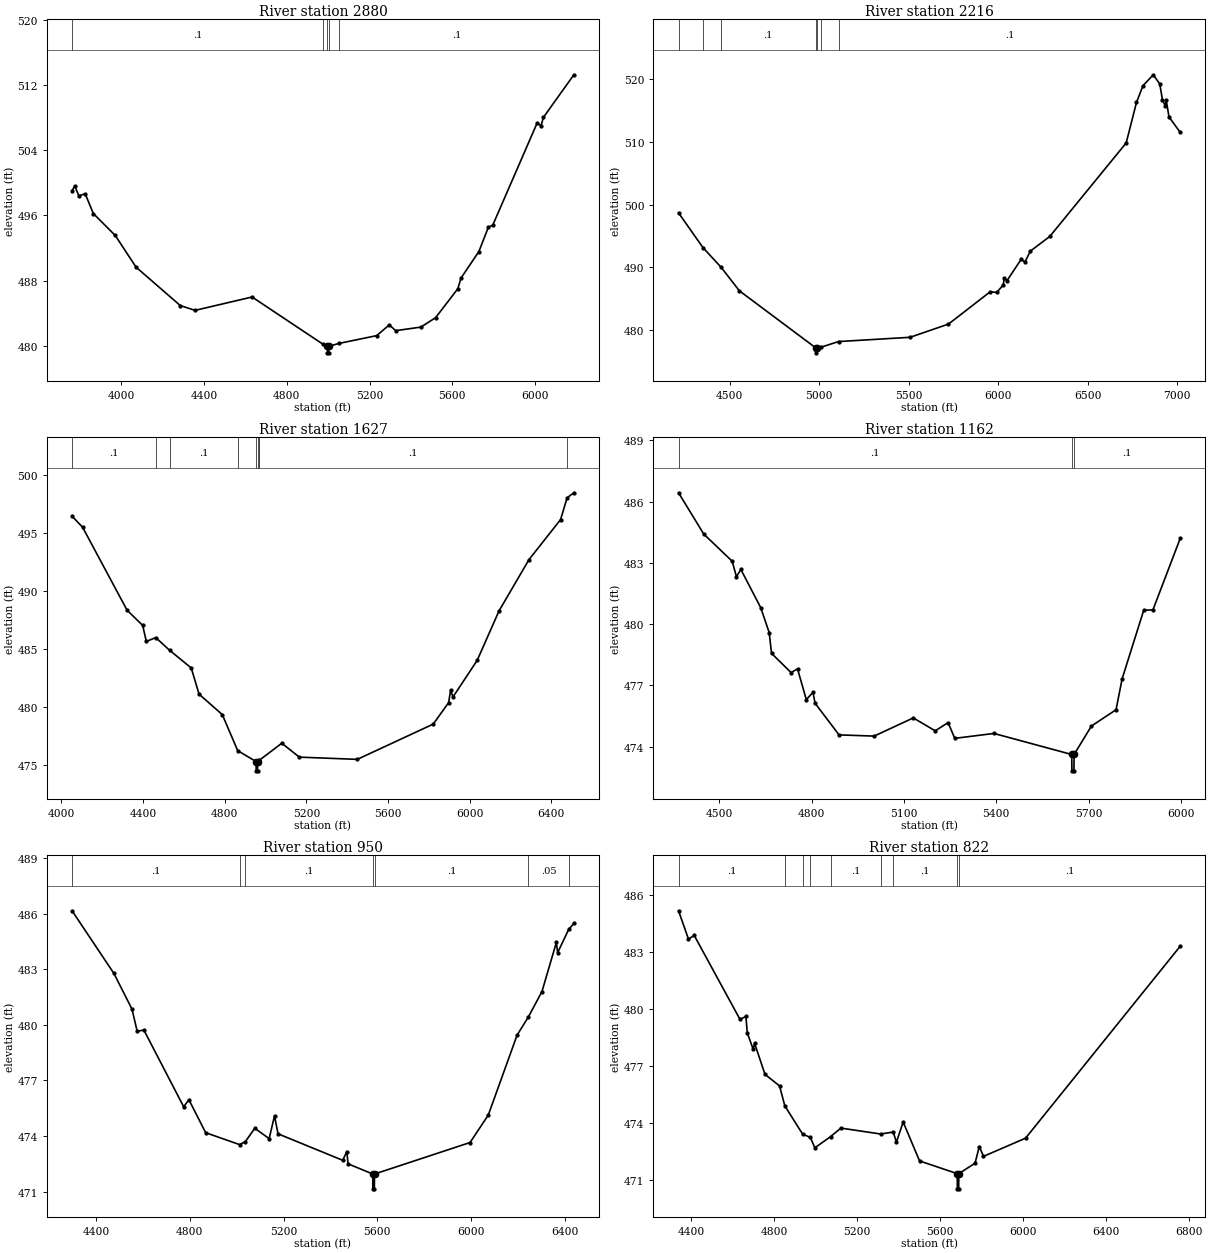
Type RM Length L Ch R = 1,2880,664,664,664
BEGIN DESCRIPTION:
UNT 027 in RCW 6.0
END DESCRIPTION:
XS GIS Cut Line= 3
      1988901.36     13462137.21      1988671.32     13461017.39
      1988419.92     13459760.39
#Sta/Elev= 30
  3762.1  499.02  3774.6  499.61  3795.0  498.41  3825.6  498.65  3864.8  496.23
  3970.7  493.54  4071.4  489.65  4285.0  484.94  4356.5  484.35  4632.1  485.99
  4976.2  480.17  4995.8  479.94  4996.4  479.14  5002.7  479.14  5003.3  479.94
  5052.4  480.30  5234.1  481.25  5295.3  482.57  5325.9  481.86  5448.2  482.30
  5519.2  483.46  5626.3  487.00  5642.0  488.32  5728.3  491.57  5774.2  494.56
  5795.0  494.79  6009.1  507.30  6029.1  507.02  6039.7  508.01  6187.2  513.25
#Mann=5,-1,0
  3762.1     0.1       0  4976.2    0.12       0  4995.8    0.07       0
  5003.3    0.12       0  5052.4     0.1       0
Bank Sta=4995.8,5003.3
Exp/Cntr=0.3,0.1

Type RM Length L Ch R = 1,2216,589,589,589
BEGIN DESCRIPTION:
UNT 027 in RCW 5.0
END DESCRIPTION:
XS GIS Cut Line= 3
      1989325.00     13461774.98      1989300.66     13460570.34
      1988436.97     13459224.89
#Sta/Elev= 30
  4213.9  498.69  4350.8  493.13  4450.8  490.04  4553.9  486.25  4980.2  477.15
  4980.8  476.35  4987.9  477.15  5009.1  477.24  5107.8  478.15  5507.5  478.83
  5722.2  480.94  5955.4  486.10  5991.7  485.99  6028.1  487.18  6034.0  488.30
  6049.2  487.87  6127.8  491.26  6150.0  490.86  6179.3  492.58  6288.4  494.93
  6715.1  509.85  6772.6  516.31  6808.9  518.99  6866.4  520.73  6902.7  519.27
  6917.9  516.70  6933.1  515.80  6939.1  516.63  6954.3  514.00  7017.6  511.52
#Mann=7,-1,0
  4213.9     0.1       0  4350.8    0.05       0  4450.8     0.1       0
  4980.2    0.07       0  4987.9     0.1       0  5009.1    0.12       0
  5107.8     0.1       0
Bank Sta=4980.2,4987.9
Exp/Cntr=0.3,0.1

Type RM Length L Ch R = 1,1627,465,465,465
BEGIN DESCRIPTION:
UNT 027 in RCW 4.0
END DESCRIPTION:
XS GIS Cut Line= 3
      1989526.34     13461842.08      1989860.56     13461056.45
      1990450.41     13459564.48
#Sta/Elev= 30
  4052.1  496.44  4103.3  495.50  4321.5  488.34  4397.8  487.03  4416.0  485.64
  4461.9  485.98  4530.1  484.88  4635.8  483.36  4674.2  481.10  4787.9  479.34
  4863.5  476.23  4953.4  475.29  4954.1  474.49  4960.5  474.49  4961.1  475.29
  4967.6  475.38  4968.5  475.39  5079.5  476.87  5165.5  475.67  5449.4  475.48
  5821.4  478.52  5896.7  480.37  5906.4  481.43  5918.2  480.86  6036.5  484.01
  6144.0  488.29  6290.4  492.70  6445.1  496.15  6477.2  498.03  6510.2  498.46
#Mann=9,-1,0
  4052.1     0.1       0  4461.9    0.05       0  4530.1     0.1       0
  4863.5    0.07       0  4953.4    0.07       0  4961.1    0.07       0
  4967.6    0.12       0  4968.5     0.1       0  6477.2    0.05       0
Bank Sta=4953.4,4961.1
Exp/Cntr=0.3,0.1

Type RM Length L Ch R = 1,1162,212,212,212
BEGIN DESCRIPTION:
UNT 027 in RCW 3.0
END DESCRIPTION:
XS GIS Cut Line= 3
      1989840.57     13461686.69      1990590.59     13460822.08
      1990590.59     13460335.97
#Sta/Elev= 30
  4367.4  486.43  4449.3  484.41  4541.7  483.08  4555.6  482.32  4569.9  482.68
  4634.4  480.81  4662.0  479.59  4669.6  478.57  4733.2  477.63  4754.1  477.81
  4782.6  476.31  4804.5  476.66  4811.1  476.13  4889.0  474.58  5003.0  474.52
  5130.2  475.41  5201.5  474.78  5243.4  475.18  5265.1  474.41  5392.3  474.65
  5645.2  473.62  5645.8  472.82  5652.3  472.82  5652.9  473.62  5709.1  475.01
  5789.1  475.81  5809.1  477.33  5879.1  480.68  5909.1  480.70  5998.1  484.21
#Mann=3,-1,0
  4367.4     0.1       0  5645.2    0.07       0  5652.9     0.1       0
Bank Sta=5645.2,5652.9
Exp/Cntr=0.3,0.1

Type RM Length L Ch R = 1,950,128,128,128
BEGIN DESCRIPTION:
UNT 027 in RCW 2.0
END DESCRIPTION:
XS GIS Cut Line= 4
      1989944.75     13461804.73      1990291.98     13461370.69
      1990993.37     13461044.30      1990628.78     13460318.60
#Sta/Elev= 30
  4297.4  486.16  4475.9  482.78  4553.2  480.85  4575.2  479.66  4604.0  479.72
  4773.7  475.58  4796.1  475.96  4867.6  474.18  5012.1  473.54  5037.0  473.70
  5077.2  474.42  5138.6  473.86  5161.4  475.09  5176.4  474.12  5452.6  472.69
  5469.9  473.16  5475.4  472.50  5580.5  471.95  5581.1  471.15  5587.6  471.15
  5588.2  471.95  5995.9  473.65  6073.7  475.13  6196.8  479.45  6244.5  480.42
  6302.9  481.80  6364.3  484.45  6369.9  483.90  6416.7  485.15  6439.0  485.48
#Mann=7,-1,0
  4297.4     0.1       0  5012.1    0.07       0  5037.0     0.1       0
  5580.5    0.07       0  5588.2     0.1       0  6244.5    0.05       0
  6416.7     0.1       0
Bank Sta=5580.5,5588.2
Exp/Cntr=0.3,0.1

Type RM Length L Ch R = 1,822,458,458,458
BEGIN DESCRIPTION:
Mapping XS 5a53df26
END DESCRIPTION:
XS GIS Cut Line= 4
      1989998.67     13461825.98      1990521.57     13461376.07
      1991112.72     13461084.40      1990930.45     13460029.84
#Sta/Elev= 30
  4338.5  485.17  4386.4  483.68  4414.2  483.87  4634.7  479.45  4663.3  479.60
  4669.9  478.74  4698.4  477.87  4705.0  478.19  4755.4  476.55  4825.7  475.94
  4850.9  474.89  4937.0  473.40  4974.1  473.23  4995.7  472.68  5071.3  473.27
  5121.3  473.72  5312.6  473.41  5373.5  473.51  5389.0  472.98  5421.5  474.04
  5500.5  471.99  5682.1  471.32  5682.7  470.52  5689.2  470.52  5689.8  471.32
  5768.1  471.87  5788.4  472.75  5808.7  472.23  6011.6  473.19  6757.7  483.31
#Mann=9,-1,0
  4338.5     0.1       0  4850.9    0.07       0  4937.0     0.1       0
  4974.1    0.07       0  5071.3     0.1       0  5312.6    0.07       0
  5373.5     0.1       0  5682.1    0.07       0  5689.8     0.1       0
Bank Sta=5682.1,5689.8
Exp/Cntr=0.3,0.1

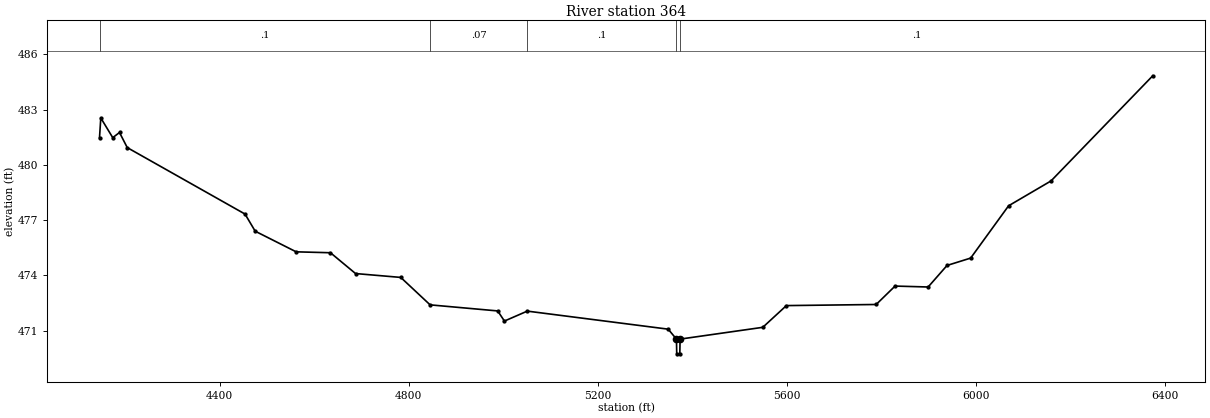
Type RM Length L Ch R = 1,364,0,0,0
BEGIN DESCRIPTION:
UNT 027 in RCW 1.0
END DESCRIPTION:
XS GIS Cut Line= 4
      1990155.24     13461810.10      1990766.28     13461589.60
      1991231.56     13461146.89      1991214.29     13460209.70
#Sta/Elev= 30
  4145.6  481.48  4148.3  482.55  4173.6  481.48  4187.9  481.76  4204.3  480.94
  4453.6  477.33  4475.1  476.40  4561.8  475.28  4634.4  475.23  4687.5  474.10
  4783.2  473.89  4845.3  472.40  4988.4  472.07  5002.6  471.52  5051.0  472.06
  5349.2  471.08  5366.7  470.54  5367.3  469.74  5373.8  469.74  5374.4  470.54
  5549.4  471.18  5599.4  472.36  5789.4  472.42  5829.4  473.42  5899.4  473.37
  5939.4  474.54  5989.4  474.94  6069.7  477.78  6159.5  479.13  6374.8  484.84
#Mann=5,-1,0
  4145.6     0.1       0  4845.3    0.07       0  5051.0     0.1       0
  5366.7    0.07       0  5374.4     0.1       0
Bank Sta=5366.7,5374.4
Exp/Cntr=0.3,0.1

Chan Stop Cuts=-1