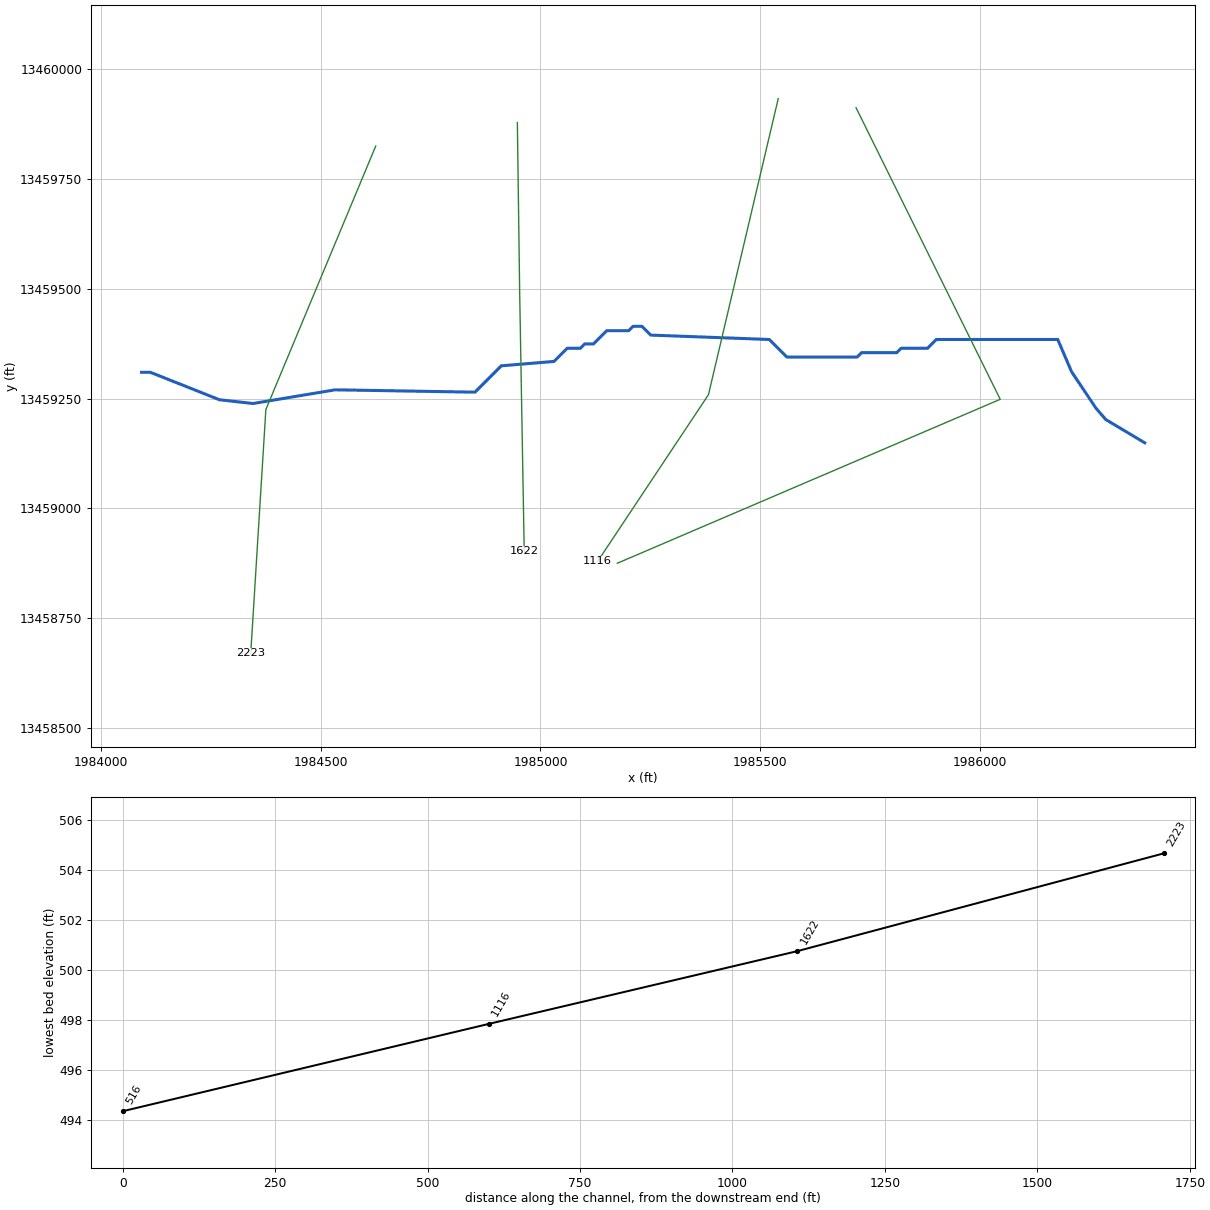
--- UNT 028 in RCW.prj (project) ---

Proj Title=UNT 028 in RCW Base Level Engineering
Current Plan=p01
Default Exp/Contr=0.3,0.1
English Units
Geom File=g01
Flow File=f01
Plan File=p01
BEGIN DESCRIPTION:
UNT 028 in RCW
END DESCRIPTION:

--- UNT 028 in RCW.p01 (plan) ---

Plan Title=Multiple Run
Short Identifier=Multiple
Geom File=g01
Flow File=f01
Subcritical Flow
K Sum by GR= 0
Std Step Tol= 0.01
Critical Tol= 0.01
Num of Std Step Trials= 20
Max Error Tol= 0.3
Flow Tol Ratio= 0.001
Split Flow NTrial= 30
Split Flow Tol= 0.02
Split Flow Ratio= 0.02
Log Output Level= 0
Friction Slope Method= 1
Unsteady Friction Slope Method= 2
Unsteady Bridges Friction Slope Method= 1
Parabolic Critical Depth
Global Vel Dist=  1 , 1 , 1
Global Log Level= 0
CheckData=True
Encroach Param= -1, 0, 0, 0
BEGIN DESCRIPTION:
Multiple Run
END DESCRIPTION:

--- UNT 028 in RCW.f01 (steady flow) ---

Flow Title=Multiple
Number of Profiles=7
Profile Names=10-year,25-year,50-year,1pct_min,100-year,1pct_plu,500-year
River Rch & RM= UNT 028 in RCW,Reach-1,2223
     161     220     267     162     324     646     482
Boundary for River Rch & Prof#=UNT 028 in RCW,Reach-1,1
Up Type=0
Dn Type=3
Dn Slope=0.005
Boundary for River Rch & Prof#=UNT 028 in RCW,Reach-1,2
Up Type=0
Dn Type=3
Dn Slope=0.005
Boundary for River Rch & Prof#=UNT 028 in RCW,Reach-1,3
Up Type=0
Dn Type=3
Dn Slope=0.005
Boundary for River Rch & Prof#=UNT 028 in RCW,Reach-1,4
Up Type=0
Dn Type=3
Dn Slope=0.005
Boundary for River Rch & Prof#=UNT 028 in RCW,Reach-1,5
Up Type=0
Dn Type=3
Dn Slope=0.005
Boundary for River Rch & Prof#=UNT 028 in RCW,Reach-1,6
Up Type=0
Dn Type=3
Dn Slope=0.005
Boundary for River Rch & Prof#=UNT 028 in RCW,Reach-1,7
Up Type=0
Dn Type=3
Dn Slope=0.005

--- UNT 028 in RCW.g01 (geometry) ---

Geom Title=Existing Conditions

River Reach=UNT 028 in RCW,Reach-1
Reach XY= 30
      1984092.13     13459309.85      1984112.10     13459309.85
      1984269.22     13459247.35      1984345.60     13459238.67
      1984533.10     13459269.92      1984850.80     13459264.54
      1984910.80     13459324.54      1985030.80     13459334.54
      1985060.80     13459364.54      1985090.80     13459364.54
      1985100.80     13459374.54      1985120.80     13459374.54
      1985150.80     13459404.54      1985200.80     13459404.54
      1985210.80     13459414.54      1985230.80     13459414.54
      1985250.80     13459394.54      1985520.80     13459384.54
      1985560.80     13459344.54      1985720.80     13459344.54
      1985730.80     13459354.54      1985810.80     13459354.54
      1985820.80     13459364.54      1985880.80     13459364.54
      1985900.80     13459384.54      1986177.20     13459384.54
      1986208.45     13459311.59      1986264.01     13459228.26
      1986286.58     13459202.22      1986375.12     13459149.26

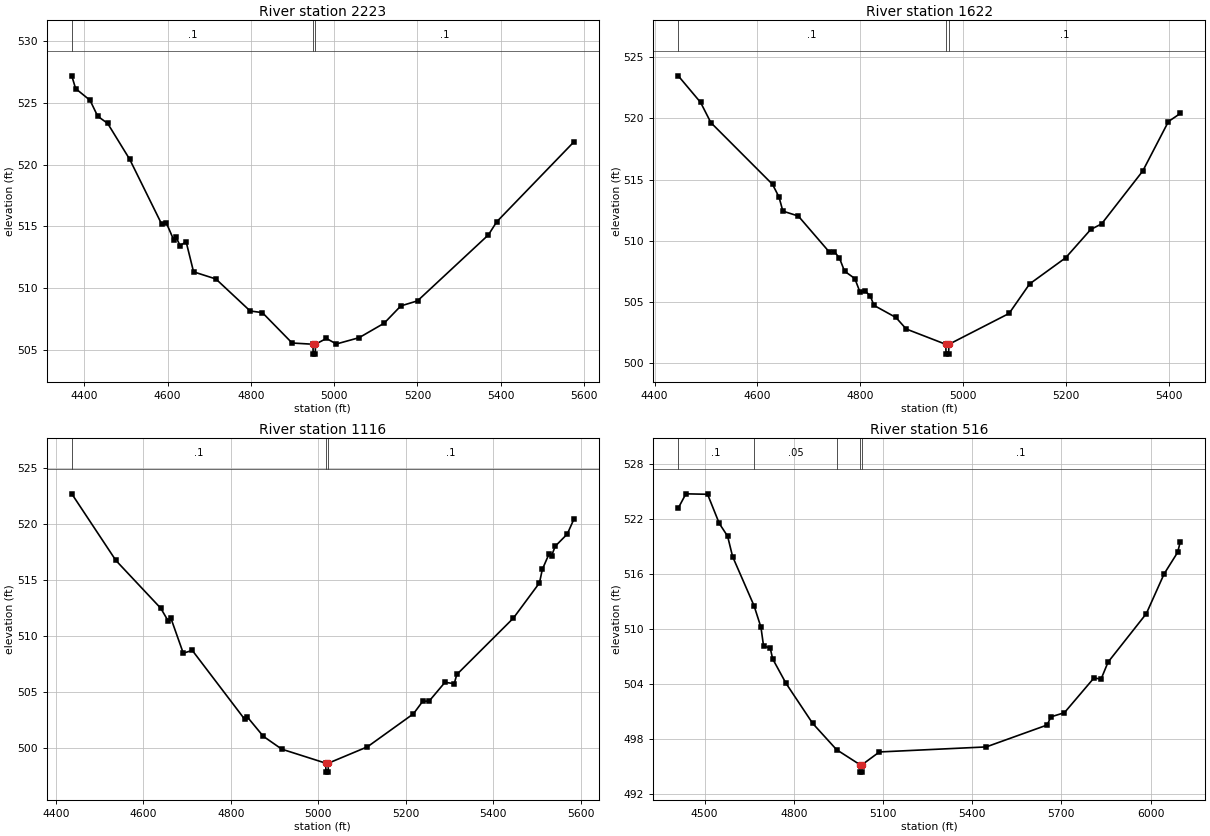
Type RM Length L Ch R = 1,2223,601,601,601
BEGIN DESCRIPTION:
UNT 028 in RCW 4.0
END DESCRIPTION:
XS GIS Cut Line= 3
      1984625.01     13459825.02      1984375.00     13459225.00
      1984340.60     13458670.19
#Sta/Elev= 30
  4369.9  527.19  4379.1  526.16  4413.8  525.21  4432.2  523.92  4456.1  523.34
  4509.1  520.43  4586.1  515.17  4597.4  515.26  4615.3  513.87  4620.7  514.12
  4629.9  513.45  4644.6  513.76  4662.4  511.33  4716.1  510.75  4798.4  508.16
  4827.6  508.03  4899.1  505.57  4949.2  505.47  4949.7  504.67  4954.7  504.67
  4955.2  505.47  4981.5  505.94  5005.3  505.49  5060.0  506.00  5120.1  507.17
  5160.2  508.57  5200.3  508.98  5370.6  514.32  5390.6  515.38  5575.8  521.84
#Mann=3,-1,0
  4369.9     0.1       0  4949.2    0.07       0  4955.2     0.1       0
Bank Sta=4949.2,4955.2
Exp/Cntr=0.3,0.1

Type RM Length L Ch R = 1,1622,506,506,506
BEGIN DESCRIPTION:
UNT 028 in RCW 3.0
END DESCRIPTION:
XS GIS Cut Line= 3
      1984947.37     13459878.48      1984952.57     13459495.69
      1984962.99     13458901.90
#Sta/Elev= 30
  4446.0  523.47  4489.5  521.30  4509.5  519.65  4629.5  514.61  4642.1  513.57
  4649.5  512.43  4679.5  512.03  4739.5  509.11  4749.5  509.13  4759.5  508.61
  4769.5  507.53  4789.5  506.93  4799.5  505.83  4809.5  505.91  4819.5  505.52
  4826.7  504.74  4869.5  503.75  4889.5  502.81  4966.5  501.56  4967.0  500.76
  4972.0  500.76  4972.5  501.56  5089.6  504.08  5129.6  506.49  5199.6  508.62
  5248.4  510.93  5269.6  511.39  5349.6  515.70  5399.6  519.74  5422.7  520.40
#Mann=3,-1,0
  4446.0     0.1       0  4966.5    0.07       0  4972.5     0.1       0
Bank Sta=4966.5,4972.5
Exp/Cntr=0.3,0.1

Type RM Length L Ch R = 1,1116,600,600,600
BEGIN DESCRIPTION:
UNT 028 in RCW 2.0
END DESCRIPTION:
XS GIS Cut Line= 3
      1985541.12     13459933.23      1985382.26     13459258.71
      1985130.34     13458879.54
#Sta/Elev= 30
  4436.3  522.70  4537.2  516.75  4639.9  512.48  4657.3  511.31  4662.5  511.65
  4691.3  508.47  4711.9  508.72  4831.9  502.56  4837.0  502.81  4874.3  501.05
  4916.6  499.90  5017.1  498.65  5017.6  497.85  5022.6  497.85  5023.1  498.65
  5112.5  500.11  5217.7  503.06  5238.8  504.17  5253.8  504.20  5289.8  505.87
  5310.9  505.75  5316.9  506.57  5446.2  511.60  5505.9  514.75  5512.4  515.95
  5527.4  517.30  5533.4  517.15  5541.9  518.02  5569.5  519.11  5584.5  520.43
#Mann=3,-1,0
  4436.3     0.1       0  5017.1    0.07       0  5023.1     0.1       0
Bank Sta=5017.1,5023.1
Exp/Cntr=0.3,0.1

Type RM Length L Ch R = 1,516,0,0,0
BEGIN DESCRIPTION:
UNT 028 in RCW 1.0
END DESCRIPTION:
XS GIS Cut Line= 3
      1985718.21     13459912.32      1986046.32     13459248.29
      1985174.99     13458875.00
#Sta/Elev= 30
  4411.3  523.16  4437.1  524.72  4510.0  524.67  4549.3  521.49  4577.3  520.10
  4594.1  517.88  4666.4  512.50  4689.5  510.16  4698.3  508.11  4720.6  507.91
  4728.8  506.72  4773.7  504.05  4863.4  499.68  4943.8  496.81  5023.1  495.16
  5023.6  494.36  5028.6  494.36  5029.1  495.16  5087.8  496.56  5447.0  497.11
  5652.0  499.50  5664.7  500.39  5710.0  500.84  5809.7  504.64  5833.3  504.50
  5856.9  506.36  5985.6  511.65  6045.5  515.99  6090.8  518.33  6099.9  519.50
#Mann=5,-1,0
  4411.3     0.1       0  4666.4    0.05       0  4943.8     0.1       0
  5023.1    0.07       0  5029.1     0.1       0
Bank Sta=5023.1,5029.1
Exp/Cntr=0.3,0.1

Chan Stop Cuts=-1