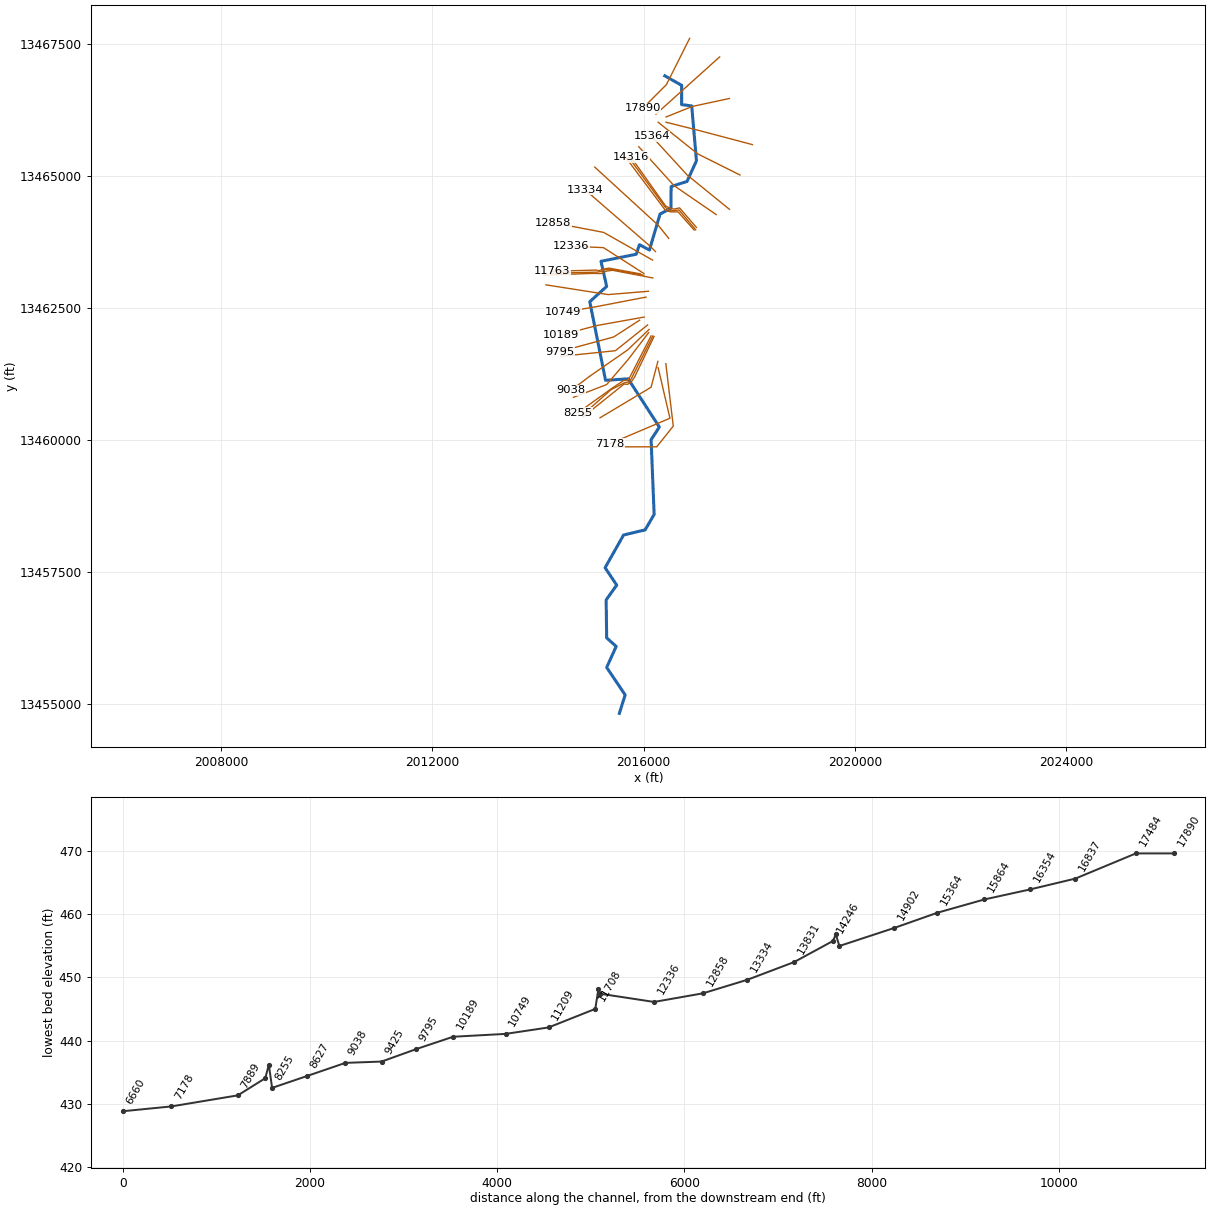
--- UNT 030 in RCW.prj (project) ---

Proj Title=UNT 030 in RCW Base Level Engineering
Current Plan=p01
Default Exp/Contr=0.3,0.1
English Units
Geom File=g01
Flow File=f01
Plan File=p01
Y Axis Title=Elevation
X Axis Title(PF)=Main Channel Distance
X Axis Title(XS)=Station
BEGIN DESCRIPTION:
UNT 030 in RCW
END DESCRIPTION:
DSS Export Rating Curves= 0
DSS Export Rating Curve Sorted= 0
DSS Export Volume Flow Curves= 0
DXF OffsetX= 0
DXF OffsetY= 0
DXF ScaleX= 1
DXF ScaleY= 10

--- UNT 030 in RCW.p01 (plan) ---

Plan Title=Multiple Run
Short Identifier=Multiple
Geom File=g01
Flow File=f01
Subcritical Flow
K Sum by GR= 0
Std Step Tol= 0.01
Critical Tol= 0.01
Num of Std Step Trials= 20
Max Error Tol= 0.3
Flow Tol Ratio= 0.001
Split Flow NTrial= 30
Split Flow Tol= 0.02
Split Flow Ratio= 0.02
Log Output Level= 0
Friction Slope Method= 1
Unsteady Friction Slope Method= 2
Unsteady Bridges Friction Slope Method= 1
Parabolic Critical Depth
Global Vel Dist=  1 , 1 , 1
Global Log Level= 0
CheckData=True
Encroach Param= -1, 0, 0, 0
BEGIN DESCRIPTION:
Multiple Run
END DESCRIPTION:

--- UNT 030 in RCW.f01 (steady flow) ---

Flow Title=Multiple
Program Version=5.05
Number of Profiles= 7
Profile Names=10-year,25-year,50-year,1pct_min,100-year,1pct_plu,500-year
River Rch & RM=UNT 030 in RCW,Reach-1         ,17890
     161     218     266     161     322     643     480
River Rch & RM=UNT 030 in RCW,Reach-1         ,17484
     258     359     444     273     545    1087     835
River Rch & RM=UNT 030 in RCW,Reach-1         ,11763
     310     432     533     328     654    1306    1001
River Rch & RM=UNT 030 in RCW,Reach-1         ,6086
     450     641     803     501     999    1993    1570
River Rch & RM=UNT 030 in RCW,Reach-1         ,3702
     450     641     803     501     999    1993    1570
River Rch & RM=UNT 030 in RCW,Reach-1         ,679
     450     641     803     501     999    1993    1570
Boundary for River Rch & Prof#=UNT 030 in RCW,Reach-1         , 1
Up Type= 0
Dn Type= 3
Dn Slope=0.005
Boundary for River Rch & Prof#=UNT 030 in RCW,Reach-1         , 2
Up Type= 0
Dn Type= 3
Dn Slope=0.005
Boundary for River Rch & Prof#=UNT 030 in RCW,Reach-1         , 3
Up Type= 0
Dn Type= 3
Dn Slope=0.005
Boundary for River Rch & Prof#=UNT 030 in RCW,Reach-1         , 4
Up Type= 0
Dn Type= 3
Dn Slope=0.005
Boundary for River Rch & Prof#=UNT 030 in RCW,Reach-1         , 5
Up Type= 0
Dn Type= 3
Dn Slope=0.005
Boundary for River Rch & Prof#=UNT 030 in RCW,Reach-1         , 6
Up Type= 0
Dn Type= 3
Dn Slope=0.005
Boundary for River Rch & Prof#=UNT 030 in RCW,Reach-1         , 7
Up Type= 0
Dn Type= 3
Dn Slope=0.005
DSS Import GetInterval= 0
DSS Import GetPeak= 0
DSS Import FillOption= 0

--- UNT 030 in RCW.g01 (geometry) ---

Geom Title=Existing Conditions
Program Version=5.05

River Reach=UNT 030 in RCW  ,Reach-1
Reach XY= 30
       2016400.8     13466904.54       2016720.8     13466723.92
      2016720.37      13466358.9       2016910.8     13466334.54
       2017000.8     13465294.54      2016822.45     13464903.61
      2016520.89     13464806.73      2016517.77     13464396.84
       2016310.8     13464284.54       2016110.8     13463604.54
       2015920.8     13463704.54       2015860.8     13463524.54
      2015193.29     13463390.07       2015300.8     13462914.54
       2014980.8     13462624.54      2015279.15     13461135.44
       2015707.4      13461163.2      2016297.68       13460250.
      2016142.12     13460009.03      2016199.43     13458594.49
       2016029.3     13458301.44       2015620.8     13458204.54
       2015270.8     13457584.54       2015490.8     13457254.54
       2015290.8     13456974.54       2015300.8     13456254.54
       2015480.8     13456094.54       2015300.8     13455694.54
       2015650.8     13455174.54       2015540.8     13454824.54

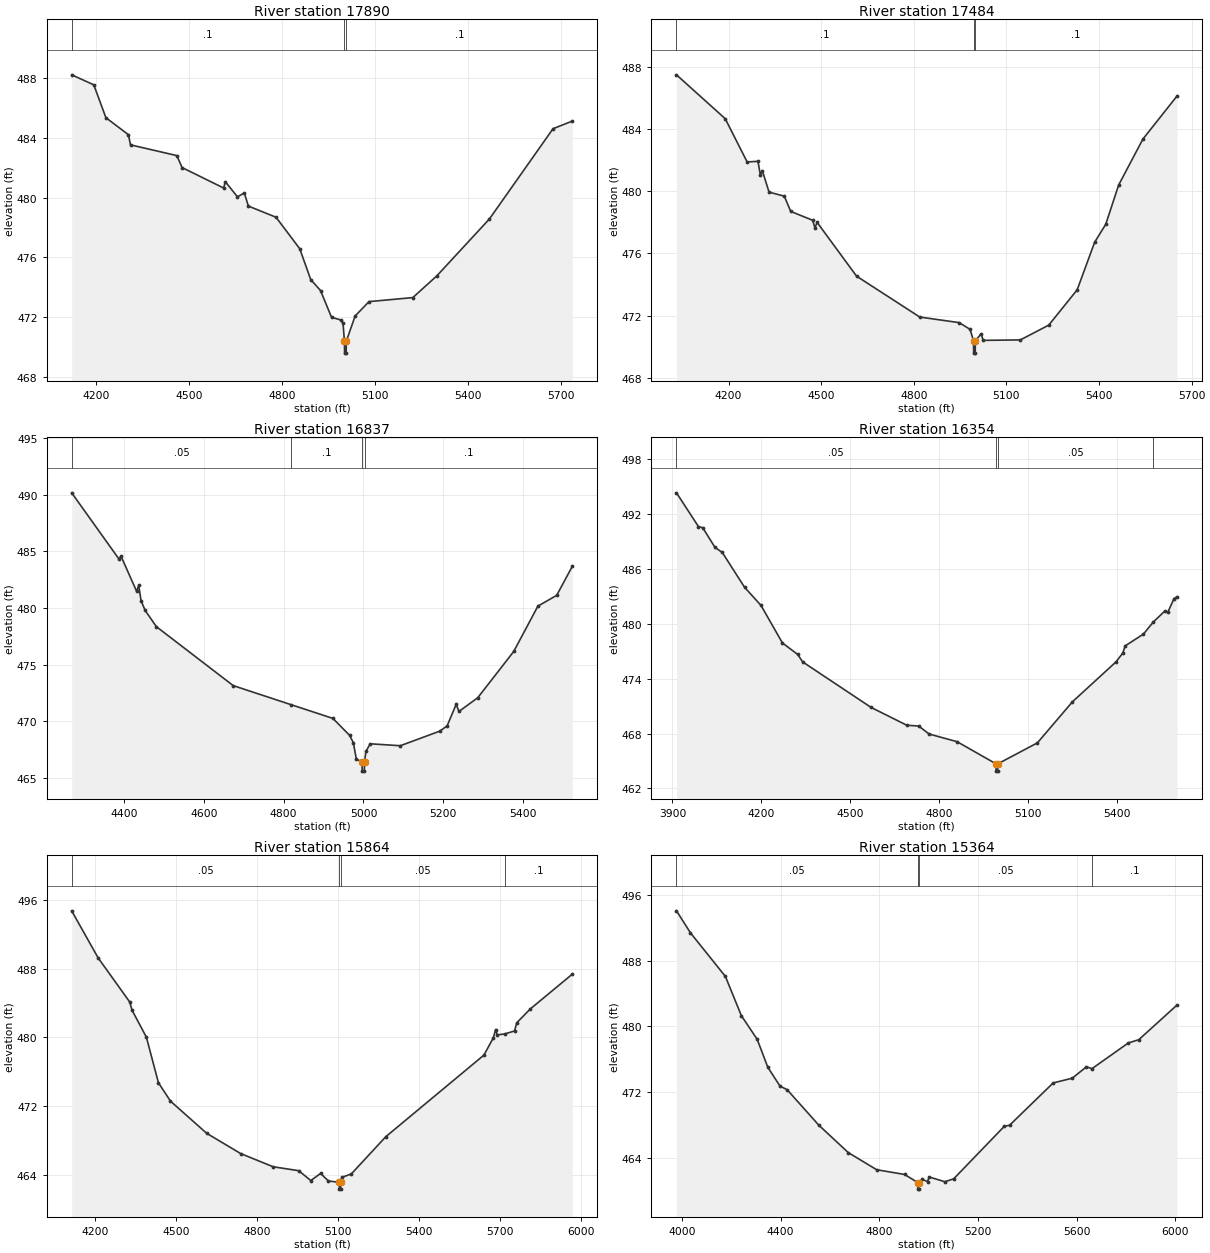
Type RM Length L Ch R = 1 ,17890   ,406,406,406
BEGIN DESCRIPTION:
UNT 030 in RCW 32.0
END DESCRIPTION:
XS GIS Cut Line= 3
      2016871.43     13467614.73      2016432.12     13466737.85
      2015983.23     13466288.96
#Sta/Elev= 30
  4120.1  488.23  4191.4  487.56  4230.5  485.36  4303.1  484.22  4309.9  483.54
  4459.5  482.82  4476.3  482.02  4610.4  480.65    4616  481.07  4655.1  480.06
  4677.4  480.32  4690.2  479.44  4779.7  478.69  4856.2  476.58  4891.5  474.52
  4923.3  473.78  4958.7  471.99  4990.3   471.8  4995.9  471.58  5000.4  470.39
  5000.9  469.59  5005.9  469.59  5006.4  470.39    5035  472.08  5079.7  473.04
  5221.1  473.31  5298.8  474.77  5468.5  478.58  5673.6  484.62  5735.7  485.13
#Mann= 3 ,-1 , 0
  4120.1      .1       0  5000.4     .07       0  5006.4      .1       0
Bank Sta=5000.4,5006.4
XS Rating Curve= 0 ,0
Exp/Cntr=0.3,0.1

Type RM Length L Ch R = 1 ,17484   ,647,647,647
BEGIN DESCRIPTION:
Mapping XS fb3bd62e
END DESCRIPTION:
XS GIS Cut Line= 2
      2017439.96     13467263.12      2016234.43       13466179.
#Sta/Elev= 30
  4031.5  487.48  4189.3  484.66  4260.3  481.88  4295.4  481.92  4302.9  481.07
  4309.6  481.31  4331.3  479.94  4380.6  479.68  4401.5   478.7  4472.6  478.13
    4480  477.63  4486.8     478  4614.6  474.54  4819.4  471.91  4947.2  471.55
  4982.3  471.12  4993.5  470.39    4994  469.59    4999  469.59  4999.5  470.39
  5018.2  470.83  5024.9  470.41  5145.3  470.44  5237.2  471.39  5329.3  473.66
  5385.9  476.72  5421.8  477.87  5463.7   480.4  5542.2  483.35  5652.8  486.12
#Mann= 3 ,-1 , 0
  4031.5      .1       0  4993.5     .07       0  4999.5      .1       0
Bank Sta=4993.5,4999.5
XS Rating Curve= 0 ,0
Exp/Cntr=0.3,0.1

Type RM Length L Ch R = 1 ,16837   ,483,483,483
BEGIN DESCRIPTION:
UNT 030 in RCW 31.0
END DESCRIPTION:
XS GIS Cut Line= 3
      2017625.01       13466475.        2016925.       13466325.
      2016425.02     13466125.01
#Sta/Elev= 30
  4268.8  490.15  4387.3  484.31  4392.4  484.56  4431.6  481.46  4436.7  481.99
  4442.7  480.63  4452.9  479.78    4481  478.35  4673.6  473.15  4818.5  471.47
  4923.3  470.26  4965.1  468.77  4974.5  468.13  4982.1  466.68  4996.4  466.41
  4996.9  465.61  5002.1  465.61  5002.6  466.41  5006.2  467.36    5017  468.02
  5092.4  467.85  5190.7  469.13  5209.5  469.59  5232.4  471.51  5239.2  470.87
  5286.3  472.08  5376.5  476.16  5437.1  480.16  5484.2  481.11  5523.2  483.66
#Mann= 4 ,-1 , 0
  4268.8     .05       0  4818.5      .1       0  4996.4     .07       0
  5002.6      .1       0
Bank Sta=4996.4,5002.6
XS Rating Curve= 0 ,0
Exp/Cntr=0.3,0.1

Type RM Length L Ch R = 1 ,16354   ,490,490,490
BEGIN DESCRIPTION:
UNT 030 in RCW 30.0
END DESCRIPTION:
XS GIS Cut Line= 3
      2018060.68      13465600.8        2017025.       13465875.
      2016425.03     13466024.99
#Sta/Elev= 30
  3913.9  494.34    3988  490.65  4002.5  490.52  4043.9  488.37  4068.4  487.82
  4143.7  484.01  4199.1  482.03  4271.5  477.92  4323.2  476.66  4339.7  475.85
  4570.7  470.87  4691.3  468.92  4731.6  468.83  4766.6  467.96  4861.1  467.12
  4992.4   464.7  4992.9   463.9  4998.2   463.9  4998.7   464.7  5132.2  466.99
  5250.7  471.49  5397.6  475.85  5420.8  476.83  5428.5   477.6  5490.3  478.89
  5523.4  480.21  5562.5  481.41  5572.8  481.29  5593.4  482.77  5603.7  482.97
#Mann= 4 ,-1 , 0
  3913.9     .05       0  4992.4     .03       0  4998.7     .05       0
  5523.4      .1       0
Bank Sta=4992.4,4998.7
XS Rating Curve= 0 ,0
Exp/Cntr=0.3,0.1

Type RM Length L Ch R = 1 ,15864   ,500,500,500
BEGIN DESCRIPTION:
UNT 030 in RCW 29.0
END DESCRIPTION:
XS GIS Cut Line= 3
      2017824.96     13465025.02        2017025.       13465425.
      2016274.96     13466025.03
#Sta/Elev= 30
  4112.1  494.77  4209.9  489.29  4327.3  484.13  4335.7  483.18  4388.8  480.04
  4433.5  474.72  4478.2  472.57  4612.4  468.82  4738.2  466.46  4858.3  464.92
  4953.4  464.46  4998.1  463.31  5034.5  464.14  5063.3  463.26  5103.4  463.11
  5103.9  462.31  5109.2  462.31  5109.7  463.11  5112.9  463.68  5148.2  464.08
  5276.2  468.43  5639.6  477.94  5674.8  479.97  5682.8  480.92  5689.2   480.3
  5716.7  480.41  5753.2  480.76  5761.3  481.71  5810.9  483.31    5967  487.38
#Mann= 4 ,-1 , 0
  4112.1     .05       0  5103.4     .03       0  5109.7     .05       0
  5716.7      .1       0
Bank Sta=5103.4,5109.7
XS Rating Curve= 0 ,0
Exp/Cntr=0.3,0.1

Type RM Length L Ch R = 1 ,15364   ,462,462,462
BEGIN DESCRIPTION:
UNT 030 in RCW 28.0
END DESCRIPTION:
XS GIS Cut Line= 3
      2017624.99     13464375.01        2016825.       13465025.
       2016151.6     13465760.66
#Sta/Elev= 30
  3978.6  494.05  4035.3  491.37  4176.8  486.07  4241.5   481.3  4305.4  478.44
  4348.5  475.04  4398.1  472.74  4426.8  472.31  4554.7  468.01  4674.6  464.66
  4789.6  462.58  4903.1     462  4955.9  461.02  4956.4  460.22  4961.8  460.22
  4962.3  461.02  4973.4  461.42  4995.7  461.14  5002.2   461.7  5065.8  461.12
  5101.6  461.47  5306.9  467.86  5327.9  467.98  5504.9  473.13  5582.6  473.71
  5639.3  475.09  5662.3  474.87  5809.2  477.99  5851.4  478.38  6006.7   482.6
#Mann= 4 ,-1 , 0
  3978.6     .05       0  4955.9     .03       0  4962.3     .05       0
  5662.3      .1       0
Bank Sta=4955.9,4962.3
XS Rating Curve= 0 ,0
Exp/Cntr=0.3,0.1

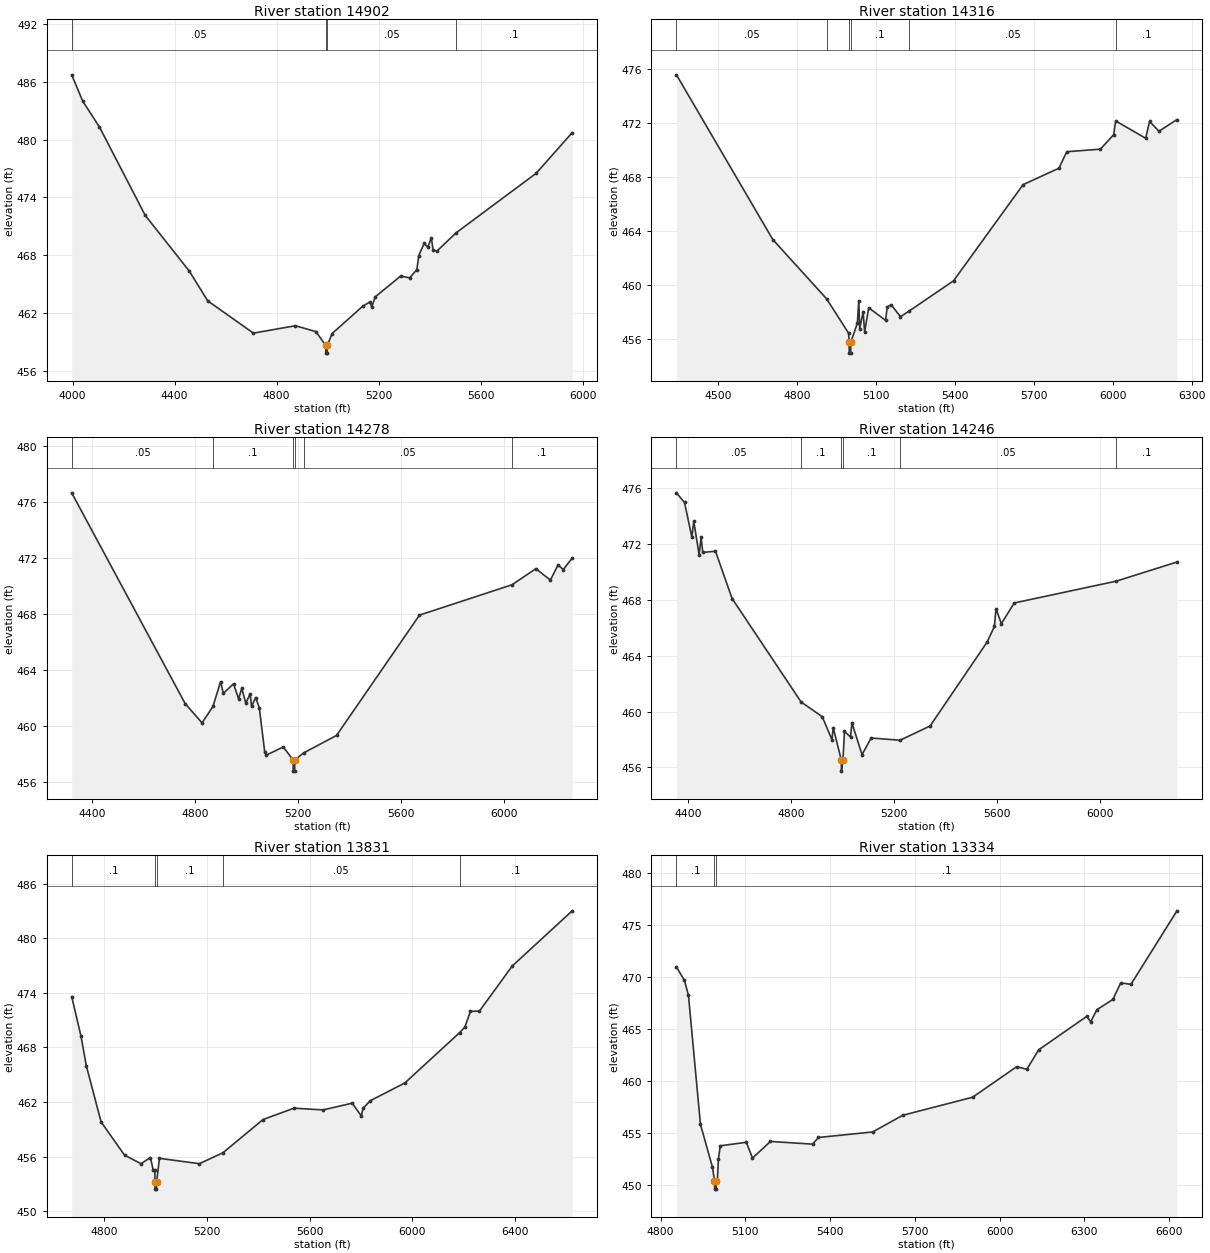
Type RM Length L Ch R = 1 ,14902   ,586,586,586
BEGIN DESCRIPTION:
UNT 030 in RCW 27.0
END DESCRIPTION:
XS GIS Cut Line= 3
      2017374.97     13464275.02        2016575.       13464825.
      2015909.74     13465559.68
#Sta/Elev= 30
  3996.7  486.76    4040  484.02  4105.6  481.33  4284.9  472.14  4457.8  466.34
  4529.8  463.25  4709.1  459.89  4873.4  460.66    4954  460.05  4992.3  458.61
  4992.8  457.81  4998.2  457.81  4998.7  458.61  5017.2  459.84  5137.5  462.69
  5165.9  463.14  5172.6   462.6  5186.8  463.67  5286.2  465.83  5321.3  465.64
  5349.7   466.5  5357.1  467.96  5378.1  469.22  5392.3  468.84  5406.5   469.8
  5413.2  468.57  5427.4   468.4  5503.2  470.32  5817.4  476.52  5958.6  480.75
#Mann= 4 ,-1 , 0
  3996.7     .05       0  4992.3     .03       0  4998.7     .05       0
  5503.2      .1       0
Bank Sta=4992.3,4998.7
XS Rating Curve= 0 ,0
Exp/Cntr=0.3,0.1

Type RM Length L Ch R = 1 ,14316   ,38,38,38
BEGIN DESCRIPTION:
Mapping XS 84f4f388
END DESCRIPTION:
XS GIS Cut Line= 6
        2016999.     13464032.26      2016681.31     13464402.03
      2016584.95     13464381.19      2016535.47      13464383.8
      2016418.29     13464435.88      2015759.74     13465365.14
#Sta/Elev= 30
  4340.3  475.59  4706.8  463.38  4911.3  458.99  4995.1  456.44  4997.1  455.76
  4997.6  454.96    5003  454.96  5003.5  455.76  5028.5  457.18  5033.8  458.84
  5037.4  456.78  5050.4  458.03  5056.2  456.54  5071.6  458.32  5135.9  457.39
  5142.1  458.38  5156.8  458.55  5192.5  457.66  5226.1  458.09  5394.3  460.32
  5658.9  467.45  5795.5  468.67    5825  469.89    5953  470.08  6003.4  471.15
  6011.2  472.17  6125.2  470.89    6140  472.14  6175.7  471.41  6244.3  472.27
#Mann= 6 ,-1 , 0
  4340.3     .05       0  4911.3      .1       0  4997.1     .07       0
  5003.5      .1       0  5226.1     .05       0  6011.2      .1       0
Bank Sta=4997.1,5003.5
XS Rating Curve= 0 ,0
Exp/Cntr=0.3,0.1

Type RM Length L Ch R = 1 ,14278   ,32,32,32
BEGIN DESCRIPTION:
UNT 030 in RCW 26.0
END DESCRIPTION:
XS GIS Cut Line= 6
      2016986.02     13463986.63      2016670.89     13464362.96
      2016522.45     13464344.73      2016459.56      13464376.2
      2016409.17      13464415.7      2015719.56     13465357.73
#Sta/Elev= 30
  4320.9  476.67  4761.1  461.61  4826.6  460.23    4869   461.4  4898.6  463.17
  4909.3  462.34  4948.8  463.02  4968.6  461.95  4980.9   462.7  4996.6  461.63
  5013.4  462.31  5018.9  461.41  5034.8  462.04    5049  461.31  5069.8  458.17
  5076.1  457.92  5141.7  458.51  5180.2  457.58  5180.7  456.78  5186.1  456.78
  5186.6  457.58  5221.7  458.09  5348.6  459.33  5670.5  467.93  6029.9   470.1
  6122.2  471.25  6178.5  470.43  6207.9  471.51  6228.7  471.19  6263.2  472.01
#Mann= 6 ,-1 , 0
  4320.9     .05       0    4869      .1       0  5180.2     .07       0
  5186.6      .1       0  5221.7     .05       0  6029.9      .1       0
Bank Sta=5180.2,5186.6
XS Rating Curve= 0 ,0
Exp/Cntr=0.3,0.1

Type RM Length L Ch R = 1 ,14246   ,415,415,415
BEGIN DESCRIPTION:
Mapping XS 809a7c96
END DESCRIPTION:
XS GIS Cut Line= 6
      2016957.38     13463982.72      2016652.66      13464326.5
      2016525.06      13464326.5      2016467.76     13464336.92
      2016407.87     13464362.96      2015666.65     13465351.25
#Sta/Elev= 30
  4353.7  475.65    4385  474.96  4413.5  472.49    4421  473.62  4441.9  471.21
  4449.4  472.47  4456.1  471.39  4505.5  471.47  4569.9  468.09  4838.2  460.69
  4920.7  459.63  4958.1  457.99  4963.2  458.85  4994.6  456.54  4995.1  455.74
    5001  456.54    5007  458.58  5030.5  458.18  5035.9  459.19  5075.2  456.92
  5110.6  458.11  5222.9  457.95  5339.8  458.97  5560.6  464.95  5589.8  466.09
    5596  467.36  5616.9  466.29  5666.9  467.77  6063.4  469.33  6299.6   470.7
#Mann= 6 ,-1 , 0
  4353.7     .05       0  4838.2      .1       0  4994.6     .07       0
    5001      .1       0  5222.9     .05       0  6063.4      .1       0
Bank Sta=4994.6,5001
XS Rating Curve= 0 ,0
Exp/Cntr=0.3,0.1

Type RM Length L Ch R = 1 ,13831   ,497,497,497
BEGIN DESCRIPTION:
UNT 030 in RCW 25.0
END DESCRIPTION:
XS GIS Cut Line= 3
      2016475.03     13463824.97        2016275.       13464075.
      2015074.99     13465175.01
#Sta/Elev= 30
  4674.1   473.6  4710.2  469.27    4731  465.99  4788.6   459.8  4879.8  456.15
  4943.9  455.21  4980.7  455.89  4991.1  454.54  4997.7  454.54  4998.2  453.21
  4998.7  452.41  5004.1  452.41  5004.6  453.21  5015.6   455.8    5171  455.21
  5262.7  456.41  5418.8  460.07  5539.1  461.32  5652.5  461.13    5766  461.87
  5801.2  460.47  5808.2  461.31  5836.3  462.14    5971   464.1  6183.8  469.63
  6204.4  470.25    6226  471.97  6261.2  472.01  6388.8  476.97  6622.2  483.04
#Mann= 5 ,-1 , 0
  4674.1      .1       0  4998.2     .07       0  5004.6      .1       0
  5262.7     .05       0  6183.8      .1       0
Bank Sta=4998.2,5004.6
XS Rating Curve= 0 ,0
Exp/Cntr=0.3,0.1

Type RM Length L Ch R = 1 ,13334   ,476,476,476
BEGIN DESCRIPTION:
UNT 030 in RCW 24.0
END DESCRIPTION:
XS GIS Cut Line= 3
      2016225.02     13463574.98        2016125.       13463675.
      2014893.51     13464743.85
#Sta/Elev= 30
  4855.9  470.97  4884.2  469.68  4898.4  468.24  4940.8  455.86  4983.2  451.76
  4990.6  450.43  4991.1  449.63  4996.6  449.63  4997.1  450.43  5000.7  450.43
  5004.5  452.52  5011.1  453.79  5103.3  454.13  5125.1  452.61  5188.7  454.21
  5337.8  453.95  5358.7  454.59  5550.5  455.12  5656.9  456.72  5904.7  458.46
  6060.5  461.39  6096.4  461.14  6138.3  463.01  6308.3  466.22  6322.5  465.71
  6344.4  466.86  6400.9  467.85  6428.9  469.44    6465   469.3    6628  476.36
#Mann= 3 ,-1 , 0
  4855.9      .1       0  4990.6     .07       0  4997.1      .1       0
Bank Sta=4990.6,4997.1
XS Rating Curve= 0 ,0
Exp/Cntr=0.3,0.1

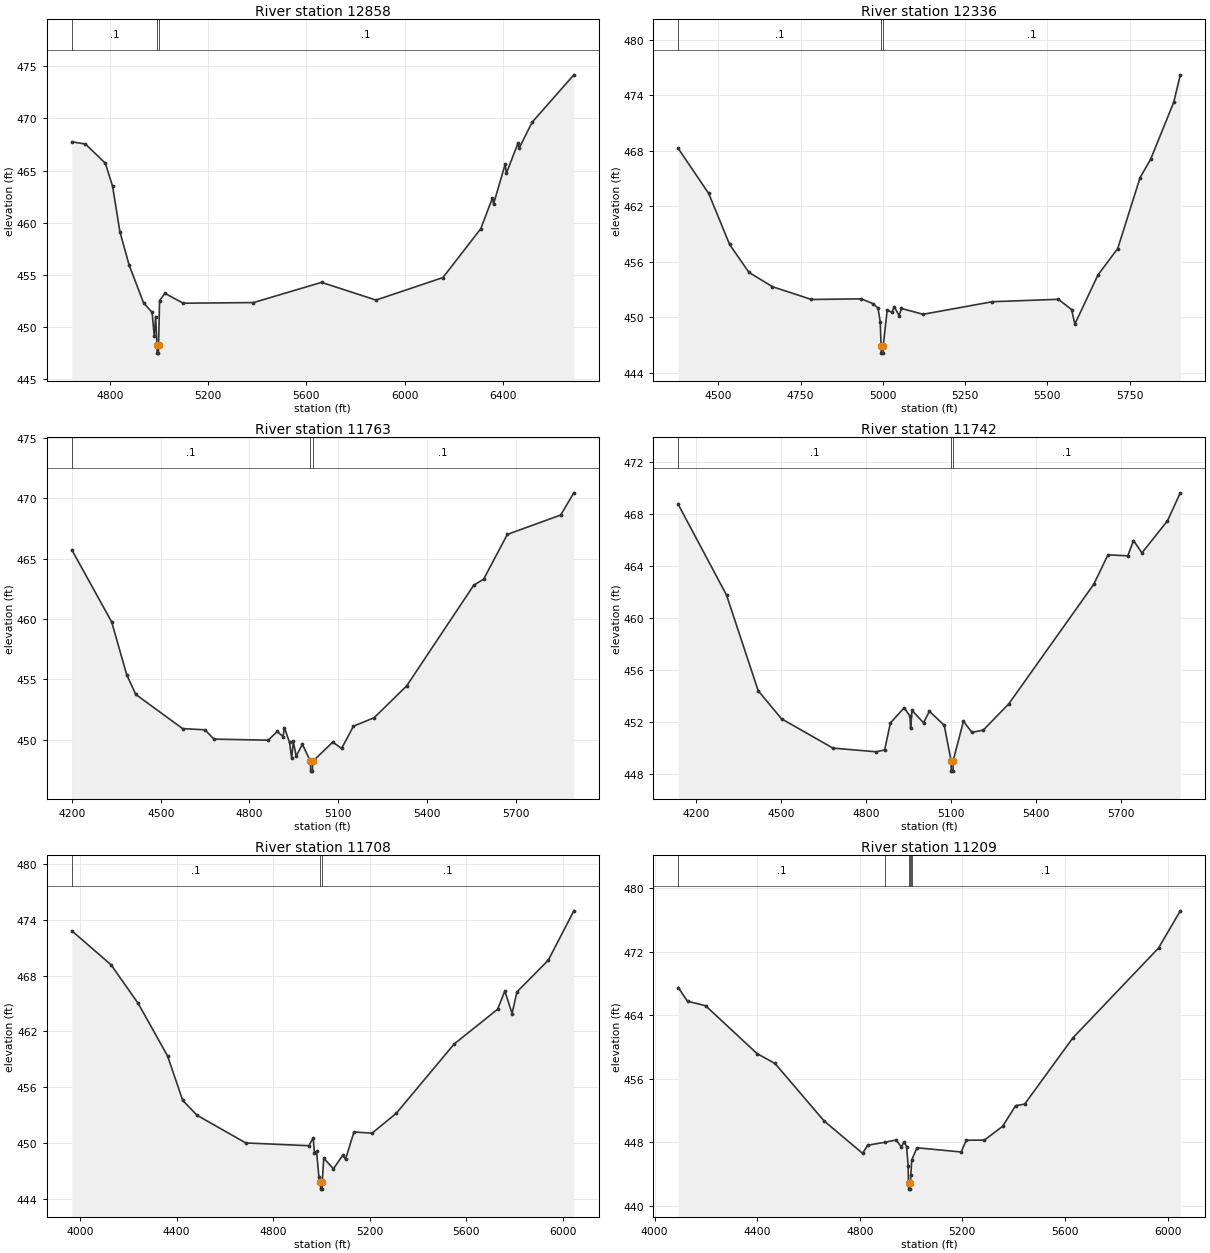
Type RM Length L Ch R = 1 ,12858   ,522,522,522
BEGIN DESCRIPTION:
UNT 030 in RCW 23.0
END DESCRIPTION:
XS GIS Cut Line= 3
      2016169.59     13463413.09      2015243.37     13463937.83
      2014281.55     13464121.86
#Sta/Elev= 30
  4645.1  467.76  4700.9  467.54  4781.7   465.7  4811.3  463.49  4840.9  459.14
  4878.4  455.94  4937.5   452.3  4972.2  451.39  4980.8  449.11  4986.6  450.99
  4991.9  448.28  4992.4  447.48  4997.9  447.48  4998.4  448.28  5002.5  452.52
  5024.1  453.22  5098.6  452.27  5384.8  452.33  5661.8  454.27  5883.5  452.57
    6156  454.73  6310.1  459.42  6357.1  462.34  6362.2   461.8  6409.2  465.59
  6414.3  464.72  6461.2  467.61  6466.3  467.14  6518.4  469.61  6688.9  474.18
#Mann= 3 ,-1 , 0
  4645.1      .1       0  4991.9     .07       0  4998.4      .1       0
Bank Sta=4991.9,4998.4
XS Rating Curve= 0 ,0
Exp/Cntr=0.3,0.1

Type RM Length L Ch R = 1 ,12336   ,573,573,573
BEGIN DESCRIPTION:
UNT 030 in RCW 22.0
END DESCRIPTION:
XS GIS Cut Line= 3
      2016005.94     13463158.77       2015239.9      13463649.2
      2014625.03       13463675.
#Sta/Elev= 30
  4378.6  468.25  4471.2  463.38  4534.6  457.87  4593.4  454.85  4664.9   453.3
  4783.2  451.92  4934.6  451.99  4970.9  451.46  4985.3  450.99  4992.1  449.53
  4994.8  446.92  4995.3  446.12  5000.8  446.12  5001.3  446.92  5013.2  450.74
  5028.4  450.55  5034.4  451.16  5049.6  450.16  5056.5  450.95  5122.3  450.32
  5333.1  451.68  5533.3  451.94  5573.3  450.83  5583.3  449.26  5653.4  454.57
  5713.5  457.43  5781.4   465.1  5813.5  467.08  5883.6  473.25  5903.6  476.21
#Mann= 3 ,-1 , 0
  4378.6      .1       0  4994.8     .07       0  5001.3      .1       0
Bank Sta=4994.8,5001.3
XS Rating Curve= 0 ,0
Exp/Cntr=0.3,0.1

Type RM Length L Ch R = 1 ,11763   ,21,21,21
BEGIN DESCRIPTION:
Mapping XS 349aa6e5
END DESCRIPTION:
XS GIS Cut Line= 6
      2015937.83     13463152.67       2015343.2     13463261.18
      2015226.01     13463239.48      2015150.06     13463211.27
      2015100.14     13463224.29       2014260.3     13463200.42
#Sta/Elev= 30
  4199.3  465.73  4334.3  459.75  4385.1  455.38  4415.6  453.76  4573.8  450.93
  4649.4  450.83  4679.9  450.06  4863.3  449.97  4893.9  450.69  4913.2  450.27
  4918.2     451  4935.4  449.78  4942.6   448.5  4948.2  449.88  4957.7  448.65
    4979  449.63  5006.2  448.21  5006.8  447.41    5013  447.41  5013.5  448.21
  5081.4  449.81  5111.4  449.29  5151.4  451.13  5221.4  451.83  5331.5  454.47
  5557.9  462.79  5591.6   463.3  5671.6     467  5851.7   468.6  5896.4  470.44
#Mann= 3 ,-1 , 0
  4199.3      .1       0  5006.2     .07       0  5013.5      .1       0
Bank Sta=5006.2,5013.5
XS Rating Curve= 0 ,0
Exp/Cntr=0.3,0.1

Type RM Length L Ch R = 1 ,11742   ,34,34,34
BEGIN DESCRIPTION:
Mapping XS 2c3eabd4
END DESCRIPTION:
XS GIS Cut Line= 6
      2016002.89     13463126.64      2015358.39     13463241.65
      2015254.22     13463226.46      2015202.14     13463200.42
      2015124.01     13463185.23      2014249.72     13463163.54
#Sta/Elev= 30
  4137.5  468.77    4308  461.79  4419.8  454.43  4502.1  452.27  4683.9  450.01
    4836  449.73  4866.3  449.87  4886.6  451.95    4935  453.11  4955.7  452.48
  4957.9  451.53    4963  452.91  5003.7  451.96  5024.1  452.85  5076.7  451.77
  5100.9  449.04  5101.4  448.24  5107.6  448.24  5108.2  449.04  5144.5  452.08
  5174.6  451.22  5214.6   451.4  5304.6  453.42  5604.8  462.63  5654.8  464.89
  5724.8  464.81  5744.8  465.99  5774.9  465.04  5864.9  467.51  5910.2  469.66
#Mann= 3 ,-1 , 0
  4137.5      .1       0  5100.9     .07       0  5108.2      .1       0
Bank Sta=5100.9,5108.2
XS Rating Curve= 0 ,0
Exp/Cntr=0.3,0.1

Type RM Length L Ch R = 1 ,11708   ,499,499,499
BEGIN DESCRIPTION:
UNT 030 in RCW 21.0
END DESCRIPTION:
XS GIS Cut Line= 6
      2016175.04     13463074.99      2015410.47     13463219.95
       2015302.4     13463205.63      2015190.42     13463157.45
      2015029.83     13463160.92      2014119.14      13463128.4
#Sta/Elev= 30
  3965.9  472.82  4128.8  469.15  4240.7  465.02  4362.9  459.35  4425.6  454.58
    4485  452.97  4687.1  449.99  4948.5  449.69  4966.6  450.52  4971.8  448.92
  4980.4  449.09  4990.4  446.31  4996.8  445.82  4997.3  445.02  5003.5  445.02
  5004.1  445.82  5010.4  448.35  5050.4  447.21  5089.2  448.67  5100.5  448.22
  5135.5  451.17  5210.5  451.04  5310.6  453.17  5550.7  460.63  5730.8  464.37
  5760.9  466.33  5790.9  463.91  5810.9  466.23    5941  469.65  6046.9  474.96
#Mann= 3 ,-1 , 0
  3965.9      .1       0  4996.8     .07       0  5004.1      .1       0
Bank Sta=4996.8,5004.1
XS Rating Curve= 0 ,0
Exp/Cntr=0.3,0.1

Type RM Length L Ch R = 1 ,11209   ,460,460,460
BEGIN DESCRIPTION:
UNT 030 in RCW 20.0
END DESCRIPTION:
XS GIS Cut Line= 3
      2016091.03     13462822.38      2015329.31     13462759.45
      2014150.88     13462943.92
#Sta/Elev= 30
  4092.5  467.49  4128.7  465.76  4198.9   465.2  4399.6  459.17  4469.8  457.92
  4660.5   450.7    4811   446.6    4831  447.62  4899.1     448  4942.2  448.28
  4962.4  447.38  4972.5  448.04  4982.6  447.46  4988.7  445.06  4990.1  442.89
  4990.7  442.09  4996.9  442.09  4997.4  442.89  4999.1  443.83  5002.6  445.76
  5023.1   447.3  5195.2  446.77  5215.4  448.25  5286.3  448.27  5357.1  450.01
  5407.8  452.61  5442.8   452.8  5630.4  461.13  5964.6  472.46  6049.6  477.15
#Mann= 6 ,-1 , 0
  4092.5      .1       0  4899.1     .07       0  4990.1     .07       0
  4997.4     .07       0  4999.1     .07       0  5002.6      .1       0
Bank Sta=4990.1,4997.4
XS Rating Curve= 0 ,0
Exp/Cntr=0.3,0.1

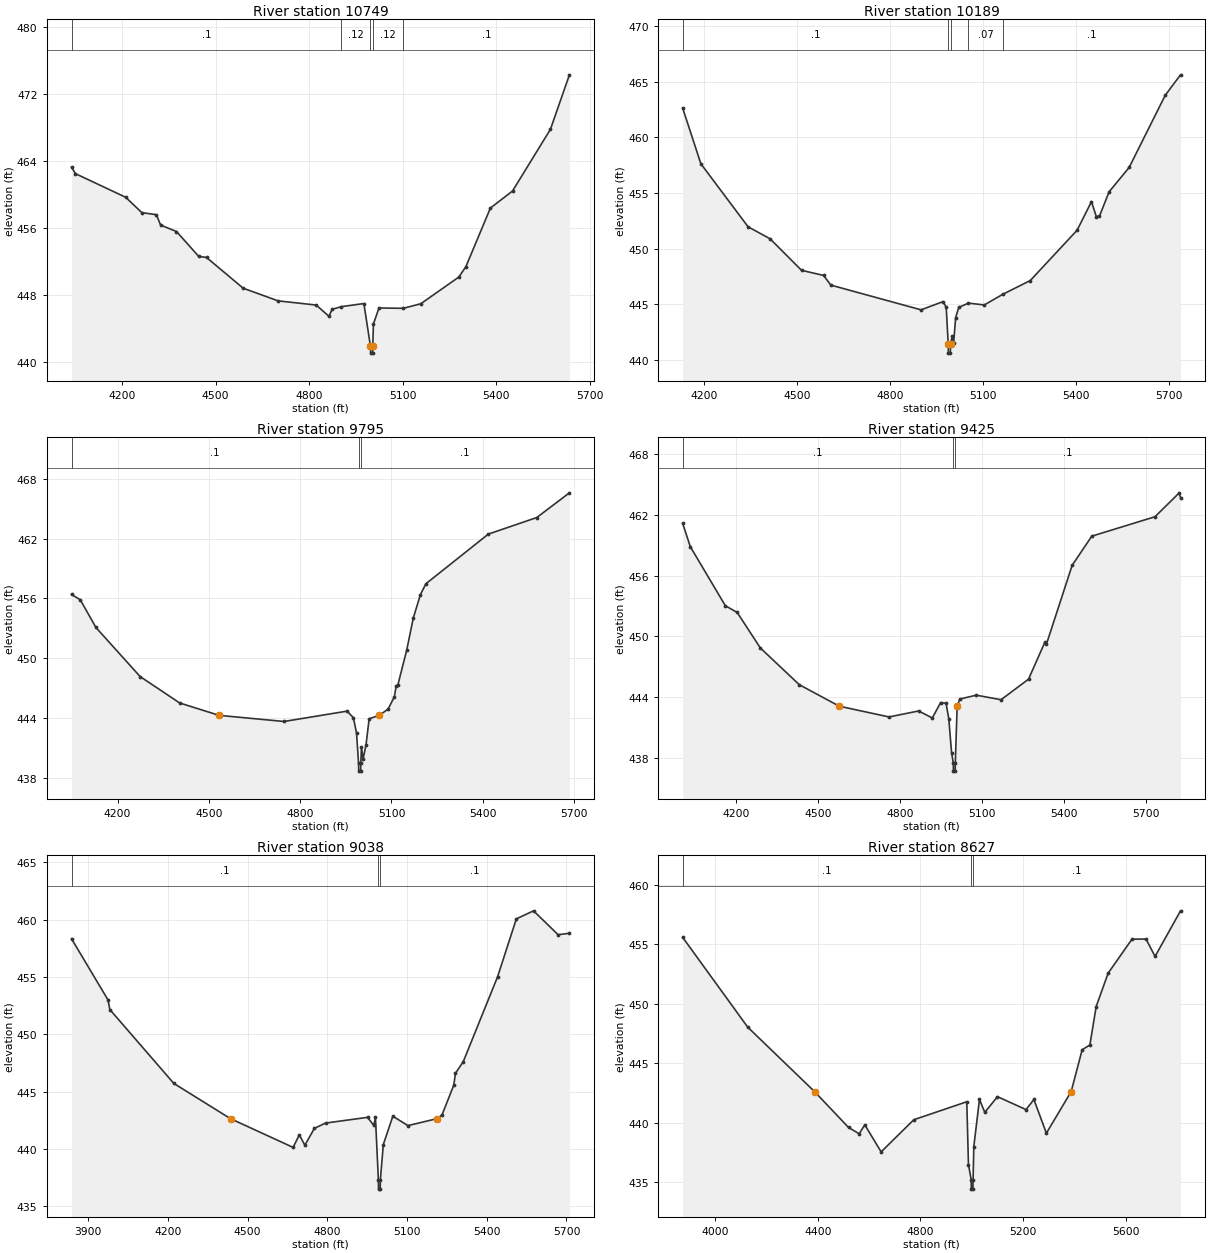
Type RM Length L Ch R = 1 ,10749   ,560,560,560
BEGIN DESCRIPTION:
UNT 030 in RCW 19.0
END DESCRIPTION:
XS GIS Cut Line= 3
      2016045.47     13462711.71        2015075.       13462525.
      2014475.05     13462425.01
#Sta/Elev= 30
    4038  463.27  4050.4   462.5  4211.6  459.68  4263.2  457.85    4310   457.6
  4323.6  456.36  4374.5  455.59  4445.8  452.62  4470.9  452.49  4588.4  448.82
  4700.4  447.31  4822.6  446.81  4863.3  445.47  4873.5   446.3    4903  446.62
  4975.4  446.99  4996.6  441.87  4997.2  441.07  5003.4  441.07    5004  441.87
  5005.9  444.53  5023.7  446.46  5101.8  446.42  5158.1  446.97  5279.7  450.15
  5302.5  451.39  5381.1  458.39  5452.1  460.43  5573.7   467.8  5634.5   474.3
#Mann= 5 ,-1 , 0
    4038      .1       0    4903     .12       0  4996.6     .07       0
    5004     .12       0  5101.8      .1       0
Bank Sta=4996.6,5004
XS Rating Curve= 0 ,0
Exp/Cntr=0.3,0.1

Type RM Length L Ch R = 1 ,10189   ,394,394,394
BEGIN DESCRIPTION:
UNT 030 in RCW 18.0
END DESCRIPTION:
XS GIS Cut Line= 3
      2016012.86     13462334.09        2015125.       13462175.
      2014441.72     13461997.73
#Sta/Elev= 30
  4130.5  462.63  4189.3  457.63  4341.7  451.97  4412.8  450.89  4514.4  448.06
  4585.5   447.6  4609.1  446.73  4900.4  444.51  4971.5  445.25  4981.7  444.74
  4988.2  441.42  4988.7  440.62    4995  440.62  4995.6  441.42  5000.6  442.12
  5005.6  441.55  5012.2  443.82  5022.3  444.73  5053.3  445.11  5104.8  444.95
    5164   445.9  5253.1  447.14  5404.4  451.66  5450.8  454.23  5466.4  452.89
  5476.7  452.93  5507.7  455.11  5572.5   457.3    5689  463.78  5738.4  465.62
#Mann= 5 ,-1 , 0
  4130.5      .1       0  4988.2     .07       0  4995.6      .1       0
  5053.3     .07       0    5164      .1       0
Bank Sta=4988.2,4995.6
XS Rating Curve= 0 ,0
Exp/Cntr=0.3,0.1

Type RM Length L Ch R = 1 ,9795    ,370,370,370
BEGIN DESCRIPTION:
UNT 030 in RCW 17.0
END DESCRIPTION:
XS GIS Cut Line= 3
      2015925.01     13462275.01      2015433.48      13461956.5
        2014420.     13461680.88
#Sta/Elev= 30
  4048.8  456.39  4077.5  455.86  4128.9  453.08    4274  448.16  4403.9  445.51
 4533.18444.2679  4746.9  443.65  4954.2  444.69  4974.9  444.03  4985.3  442.48
  4991.9  439.47  4992.5  438.67  4998.8  438.67  4999.3  439.47  5001.5  441.12
  5006.7  439.88  5016.4  441.29  5026.7  443.92 5060.05444.2676  5088.9  444.89
  5109.6  446.13  5115.7  447.24  5120.9  447.29  5150.3  450.83  5171.8  454.03
  5195.2  456.38  5213.3  457.47  5418.4  462.45  5577.5  464.11  5684.8  466.59
#Mann= 3 ,-1 , 0
  4048.8      .1       0  4991.9     .07       0  4999.3      .1       0
Bank Sta=4533.18,5060.05
XS Rating Curve= 0 ,0
Exp/Cntr=0.3,0.1

Type RM Length L Ch R = 1 ,9425    ,387,387,387
BEGIN DESCRIPTION:
UNT 030 in RCW 16.0
END DESCRIPTION:
XS GIS Cut Line= 3
      2016075.82     13462184.35      2015466.03     13461696.08
      2014432.15     13461589.87
#Sta/Elev= 30
    4006  461.16    4034  458.86  4162.1  453.03  4205.3  452.37  4290.1  448.86
  4432.6  445.23 4578.86443.1101  4760.7  442.05  4868.6  442.64  4918.9  441.95
  4949.3  443.47  4969.2  443.41  4979.2  441.85  4989.3  438.52  4995.6   437.5
  4996.2   436.7  5002.5   436.7    5003   437.5 5009.67443.1097  5019.4  443.82
  5079.7   444.2  5170.2  443.75  5270.7  445.78    5331  449.46    5336  449.22
  5430.2  457.02    5502   459.9  5733.2  461.82  5821.9  464.18  5826.5  463.71
#Mann= 3 ,-1 , 0
    4006      .1       0  4995.6     .07       0    5003      .1       0
Bank Sta=4578.86,5009.67
XS Rating Curve= 0 ,0
Exp/Cntr=0.3,0.1

Type RM Length L Ch R = 1 ,9038    ,411,411,411
BEGIN DESCRIPTION:
Mapping XS 363df18d
END DESCRIPTION:
XS GIS Cut Line= 4
      2016104.01     13462099.69      2015698.23     13461711.27
       2014988.6     13461218.65      2014630.84     13460949.79
#Sta/Elev= 30
    3838  458.32  3975.1  452.99  3982.1  452.15  4222.7  445.71 4436.08 442.634
  4671.5  440.13  4694.9  441.22  4715.8  440.32  4751.6  441.79  4793.5  442.25
  4951.6  442.75  4975.2  442.04  4981.3  442.74  4992.4  437.29    4993  436.49
  4999.3  436.49  4999.8  437.29    5011  440.38  5046.8  442.85  5103.5  442.03
 5212.92442.6343  5231.8  442.96  5276.2  445.57  5282.4  446.59  5311.6   447.6
  5440.7     455  5511.5  460.06  5576.1  460.76  5668.4  458.68  5711.1   458.8
#Mann= 3 ,-1 , 0
    3838      .1       0  4992.4     .07       0  4999.8      .1       0
Bank Sta=4436.08,5212.92
XS Rating Curve= 0 ,0
Exp/Cntr=0.3,0.1

Type RM Length L Ch R = 1 ,8627    ,372,372,372
BEGIN DESCRIPTION:
Mapping XS 275b96fc
END DESCRIPTION:
XS GIS Cut Line= 4
       2016095.4       13462039.      2015698.23     13461518.13
      2015298.93     13461053.72      2014671.78     13460812.84
#Sta/Elev= 30
  3873.9  455.56  4127.2  448.02 4387.63442.6047    4520  439.59  4561.4  439.06
  4583.4  439.81    4647  437.54  4774.3  440.24  4980.6  441.75  4987.2  436.46
  4997.8  435.21  4998.3  434.41  5004.6  434.41  5005.2  435.21    5008  437.98
    5030  441.94  5050.8  440.86  5100.2  442.18  5211.4  441.09    5242  441.94
  5290.7  439.11 5387.23442.6047  5430.1  446.12  5460.1  446.52  5484.7  449.75
  5531.2  452.55  5624.1  455.41  5678.8  455.42  5714.1  453.96  5813.2  457.79
#Mann= 3 ,-1 , 0
  3873.9      .1       0  4997.8     .07       0  5005.2      .1       0
Bank Sta=4387.63,5387.23
XS Rating Curve= 0 ,0
Exp/Cntr=0.3,0.1

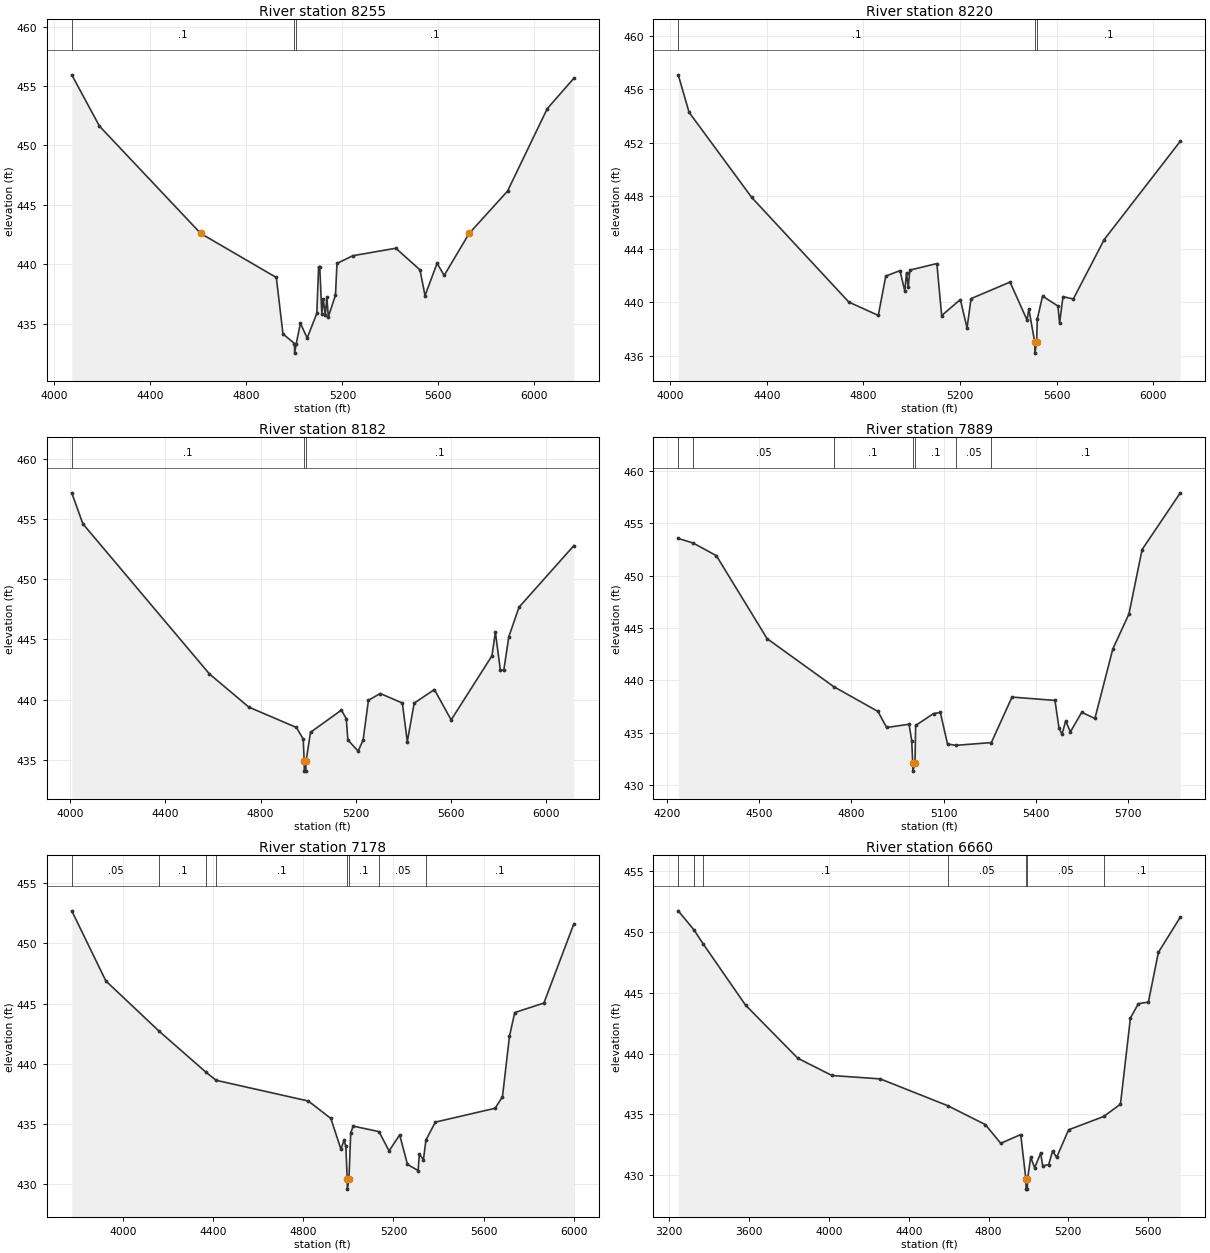
Type RM Length L Ch R = 1 ,8255    ,35,35,35
BEGIN DESCRIPTION:
Mapping XS 48e20beb
END DESCRIPTION:
XS GIS Cut Line= 6
      2016140.92     13461975.99      2015745.98      13461207.8
       2015700.4     13461140.52      2015617.94     13461129.67
      2015392.24     13460977.76      2014748.86     13460516.34
#Sta/Elev= 30
  4072.1  455.94  4187.4  451.63 4609.56442.6012  4924.6   438.9  4952.3  434.16
  5000.3  433.34  5000.9  432.54  5007.8  433.34  5024.9  435.05  5053.3  433.81
  5093.5  435.89  5100.8  439.81  5105.6  439.81  5114.2  435.87  5120.3  437.08
  5128.5  435.71  5135.3  437.26  5141.3  435.59  5171.2  437.42  5177.3  440.08
  5243.2  440.73  5422.7  441.36  5523.4  439.54  5544.3  437.37  5594.6   440.1
  5624.1  439.07 5728.13442.6011  5888.1  446.16  6053.9   453.1  6164.6  455.65
#Mann= 3 ,-1 , 0
  4072.1      .1       0  5000.3     .07       0  5007.8      .1       0
Bank Sta=4609.56,5728.13
XS Rating Curve= 0 ,0
Exp/Cntr=0.3,0.1

Type RM Length L Ch R = 1 ,8220    ,38,38,38
BEGIN DESCRIPTION:
UNT 030 in RCW 15.0
END DESCRIPTION:
XS GIS Cut Line= 6
      2016175.01     13461975.02      2015763.77     13461158.32
      2015709.08     13461104.93      2015632.26      13461086.7
      2015380.96      13460956.5      2014840.19     13460474.75
#Sta/Elev= 30
  4033.9  457.08  4078.7  454.27    4338  447.88  4739.8  440.03  4861.6  439.03
  4892.6  441.98  4951.3  442.39  4971.4  440.86  4978.4  442.24  4985.5  441.16
  4992.5  442.43    5104  442.92  5123.9  439.02  5201.1  440.22  5228.9  438.09
  5245.4  440.29  5406.8  441.53    5477  438.69  5484.6  439.51  5509.2     437
  5509.8   436.2  5516.7     437  5519.7  438.77  5541.4  440.48    5605  439.73
  5611.7  438.44  5625.9  440.44  5668.5  440.26  5796.4  444.72  6111.3   452.1
#Mann= 3 ,-1 , 0
  4033.9      .1       0  5509.2     .07       0  5516.7      .1       0
Bank Sta=5509.2,5516.7
XS Rating Curve= 0 ,0
Exp/Cntr=0.3,0.1

Type RM Length L Ch R = 1 ,8182    ,293,293,293
BEGIN DESCRIPTION:
Mapping XS 19368901
END DESCRIPTION:
XS GIS Cut Line= 6
      2016198.24     13461966.05      2015830.18     13461198.68
      2015760.73     13461097.99      2015698.23     13461059.79
      2015628.79     13461063.27      2014854.49     13460441.74
#Sta/Elev= 30
  4006.4  457.16    4053  454.59  4585.1  442.13  4750.6  439.38  4950.6  437.69
  4978.9  436.73  4983.1  434.87  4983.7  434.07    4990  434.07  4990.6  434.87
  5009.6  437.29  5139.2  439.13    5160  438.43  5166.4  436.66  5209.7  435.73
  5230.5  436.64    5253  439.95  5302.6  440.51  5395.5  439.72  5416.3  436.52
  5445.2  439.71  5530.1  440.84  5600.6  438.32    5772  443.64  5786.4   445.6
  5807.2  442.47  5821.6  442.43    5843  445.23  5885.7  447.67  6116.1  452.78
#Mann= 3 ,-1 , 0
  4006.4      .1       0  4983.1     .07       0  4990.6      .1       0
Bank Sta=4983.1,4990.6
XS Rating Curve= 0 ,0
Exp/Cntr=0.3,0.1

Type RM Length L Ch R = 1 ,7889    ,711,711,711
BEGIN DESCRIPTION:
UNT 030 in RCW 14.0
END DESCRIPTION:
XS GIS Cut Line= 3
      2016270.29     13461494.73      2016141.38      13461003.8
      2015175.02     13460425.01
#Sta/Elev= 30
  4236.5  453.54  4284.7  453.11  4360.6   451.9  4525.7  443.99  4742.7  439.41
  4886.6  437.05  4914.7  435.52  4987.7  435.83  4996.3  434.27  4999.6  432.16
  5000.1  431.36  5007.1  432.16  5009.1  435.71  5067.5  436.85  5089.5  436.95
  5112.9  433.94  5139.7  433.82  5255.5  434.08  5322.7  438.42  5462.6   438.1
  5475.8  435.44  5485.5  434.87  5497.5  436.15  5512.7   435.1  5549.7  436.97
  5592.5  436.38  5650.8     443  5703.3  446.34  5746.1  452.48  5870.5  457.89
#Mann= 7 ,-1 , 0
  4236.5      .1       0  4284.7     .05       0  4742.7      .1       0
  4999.6     .07       0  5007.1      .1       0  5139.7     .05       0
  5255.5      .1       0
Bank Sta=4999.6,5007.1
XS Rating Curve= 0 ,0
Exp/Cntr=0.3,0.1

Type RM Length L Ch R = 1 ,7178    ,518,518,518
BEGIN DESCRIPTION:
UNT 030 in RCW 13.0
END DESCRIPTION:
XS GIS Cut Line= 3
        2016275.       13461375.       2016498.8     13460416.57
      2015353.47      13459929.8
#Sta/Elev= 30
  3771.9   452.7  3923.3  446.88  4160.5   442.7  4368.9  439.29  4412.8  438.64
    4822  436.92  4922.1  435.47  4966.7  432.92  4980.2  433.66  4988.4  433.18
  4994.6  430.41  4995.2  429.61  5002.2  430.41  5010.2  434.27    5021  434.84
  5135.8  434.38  5180.3  432.78  5227.5  434.11  5262.1  431.66  5309.4  431.15
  5314.8  432.51    5333  432.05    5344  433.68  5385.8  435.17  5651.2  436.32
  5683.8  437.28  5714.9   442.3  5738.2  444.26  5867.7  445.05  6000.6  451.62
#Mann= 8 ,-1 , 0
  3771.9     .05       0  4160.5      .1       0  4368.9     .05       0
  4412.8      .1       0  4994.6     .07       0  5002.2      .1       0
  5135.8     .05       0    5344      .1       0
Bank Sta=4994.6,5002.2
XS Rating Curve= 0 ,0
Exp/Cntr=0.3,0.1

Type RM Length L Ch R = 1 ,6660    ,574,574,574
BEGIN DESCRIPTION:
UNT 030 in RCW 12.0
END DESCRIPTION:
XS GIS Cut Line= 4
      2016420.92     13461450.16      2016561.54      13460267.9
       2016248.8      13459874.9      2015425.05       13459875.
#Sta/Elev= 30
  3244.6  451.75  3323.2  450.19  3368.3  449.06  3582.1  443.99    3844  439.62
  4015.2   438.2  4257.3  437.92  4594.7  435.72    4784  434.16  4861.1  432.62
  4961.2  433.34  4987.4  429.65    4988  428.85  4994.5  428.85  4995.1  429.65
  5011.2  431.47  5031.2  430.61  5061.2  431.81  5071.2  430.78  5101.2  430.86
  5121.2  431.99  5141.2  431.46  5201.2  433.73  5377.6  434.83  5461.2  435.84
  5511.2  442.94  5551.2  444.11  5601.2  444.24  5651.2  448.33  5761.2  451.23
#Mann= 7 ,-1 , 0
  3244.6      .1       0  3323.2     .05       0  3368.3      .1       0
  4594.7     .05       0  4987.4    .035       0  4995.1     .05       0
  5377.6      .1       0
Bank Sta=4987.4,4995.1
XS Rating Curve= 0 ,0
Exp/Cntr=0.3,0.1