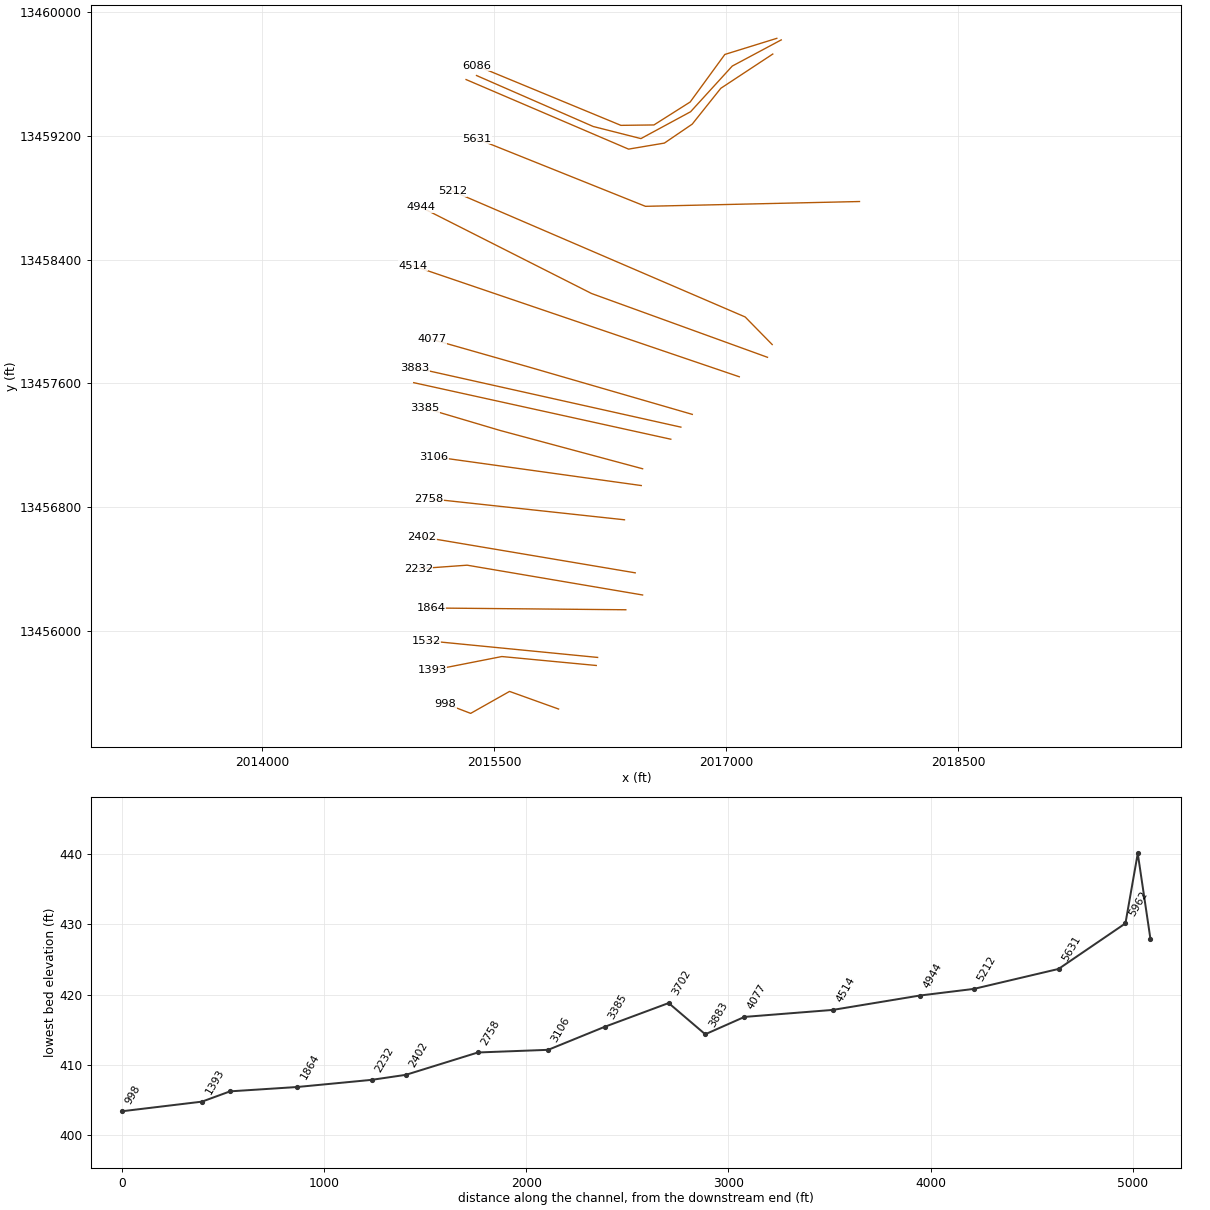
HEC-RAS study UNT 030 in RCW.prj: UNT 030 in RCW Base Level Engineering

--- UNT 030 in RCW.g01 (geometry) --- (continued)

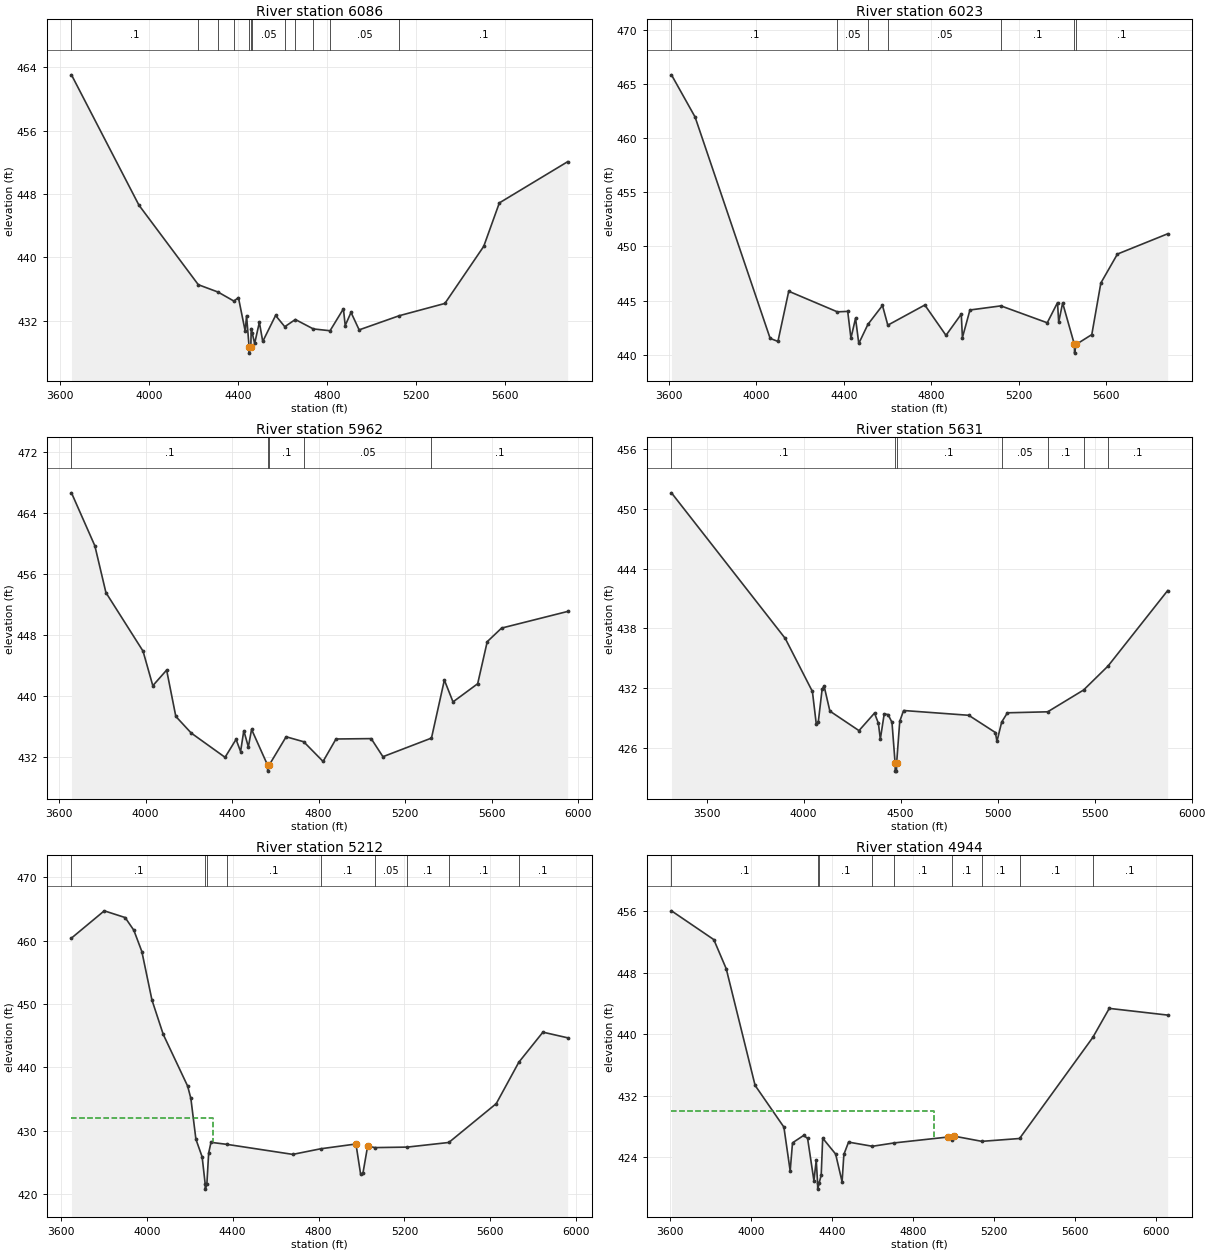
Type RM Length L Ch R = 1 ,6086    ,63,63,63
BEGIN DESCRIPTION:
UNT 030 in RCW 11.0
END DESCRIPTION:
XS GIS Cut Line= 6
      2017326.92     13459830.63      2016990.98     13459726.46
      2016767.03     13459419.17      2016532.65     13459270.73
      2016319.11     13459268.13      2015388.38     13459652.86
#Sta/Elev= 30
  3651.1  463.06  3954.3  446.59  4221.3  436.53    4310   435.6  4381.4  434.46
  4401.7   434.9  4432.2  430.65  4438.2  432.62  4449.6  428.68  4450.2  427.88
  4457.3  428.68  4459.3  430.98  4463.6  430.43  4474.6   429.1  4495.8  431.78
    4511  429.35  4568.7  432.64  4610.1  431.22  4657.5  432.13  4738.4  430.94
  4813.6  430.71  4873.6  433.48  4881.8  431.37  4907.8  433.03  4944.4  430.82
  5124.7  432.61  5329.8  434.16  5504.5  441.38  5574.7  446.87  5881.8  452.08
#Mann= 12 ,-1 , 0
  3651.1      .1       0  4221.3     .16       0    4310      .1       0
  4381.4     .16       0  4449.6    .035       0  4457.3     .16       0
  4463.6     .05       0  4610.1     .16       0  4657.5     .05       0
  4738.4      .1       0  4813.6     .05       0  5124.7      .1       0
Bank Sta=4449.6,4457.3
XS Rating Curve= 0 ,0
Exp/Cntr=0.3,0.1

Type RM Length L Ch R = 1 ,6023    ,61,61,61
BEGIN DESCRIPTION:
Mapping XS b2717543
END DESCRIPTION:
XS GIS Cut Line= 6
      2017355.63     13459820.56      2017038.83     13459651.31
      2016769.73     13459356.17      2016448.55     13459182.56
      2016140.39     13459260.68      2015385.81     13459590.27
#Sta/Elev= 30
  3612.2  465.83  3720.1  461.94  4063.3  441.51  4098.9  441.23  4148.2  445.86
  4370.4  443.96  4417.8     444  4432.6  441.53  4453.6  443.37  4468.4  441.04
  4510.1   442.8  4576.7  444.55  4601.1  442.73  4770.3  444.59    4867  441.79
  4936.9  443.75  4942.1  441.58  4976.5  444.13  5118.1  444.51  5329.9  442.95
  5376.8  444.81  5382.2     443  5400.2  444.78    5454  440.95  5454.6  440.15
  5461.7  440.95  5533.5  441.86  5574.9  446.62  5650.6  449.29  5880.2  451.16
#Mann= 7 ,-1 , 0
  3612.2      .1       0  4370.4     .05       0  4510.1      .1       0
  4601.1     .05       0  5118.1      .1       0    5454     .03       0
  5461.7      .1       0
Bank Sta=5454,5461.7
XS Rating Curve= 0 ,0
Exp/Cntr=0.3,0.1

Type RM Length L Ch R = 1 ,5962    ,331,331,331
BEGIN DESCRIPTION:
UNT 030 in RCW 10.0
END DESCRIPTION:
XS GIS Cut Line= 6
      2017300.89     13459729.07      2016964.94     13459507.71
      2016780.05     13459275.94      2016600.36     13459153.54
      2016368.59     13459114.48      2015318.27     13459564.18
#Sta/Elev= 30
  3657.5  466.62  3765.6  459.68  3816.8  453.55  3988.4  445.88  4033.6  441.35
  4097.5   443.4    4140  437.33  4211.2  435.15  4367.7  431.97  4418.5  434.32
  4439.5  432.73  4454.4  435.46  4475.4  433.33  4490.3  435.63  4564.1  430.96
  4564.7  430.16  4571.8  430.96  4650.1  434.66  4731.3  434.01  4820.9  431.43
  4880.6  434.37  5043.4  434.42  5097.7  432.05  5322.2  434.49  5381.8  442.09
  5421.8  439.23  5535.8  441.61    5580  447.12  5646.3   448.9  5951.9  451.08
#Mann= 5 ,-1 , 0
  3657.5      .1       0  4564.1     .03       0  4571.8      .1       0
  4731.3     .05       0  5322.2      .1       0
Bank Sta=4564.1,4571.8
XS Rating Curve= 0 ,0
Exp/Cntr=0.3,0.1

Type RM Length L Ch R = 1 ,5631    ,419,419,419
BEGIN DESCRIPTION:
UNT 030 in RCW 9.0
END DESCRIPTION:
XS GIS Cut Line= 3
      2017861.37     13458775.72      2016477.96     13458744.69
      2015388.43     13459181.54
#Sta/Elev= 30
  3318.6  451.61  3905.1  436.98  4045.1  431.65  4065.2  428.36  4075.2  428.55
  4095.2  431.88  4105.2  432.21  4135.2  429.68  4285.2  427.72  4365.2  429.48
  4385.2  428.46  4395.2  426.86  4415.2   429.4  4435.2  429.33  4455.3  428.55
  4471.4  424.45    4472  423.65  4478.5  423.65  4479.2  424.45  4495.3  428.66
  4515.3  429.74    4851  429.26  4988.2  427.53  4996.4  426.64  5020.7  428.58
  5050.3  429.51  5257.9  429.61  5442.9   431.8    5569  434.21  5876.2  441.79
#Mann= 7 ,-1 , 0
  3318.6      .1       0  4471.4     .07       0  4479.2      .1       0
  5020.7     .05       0  5257.9      .1       0  5442.9     .05       0
    5569      .1       0
Bank Sta=4471.4,4479.2
XS Rating Curve= 0 ,0
Exp/Cntr=0.3,0.1

Type RM Length L Ch R = 1 ,5212    ,268,268,268
BEGIN DESCRIPTION:
UNT 030 in RCW 8.0
END DESCRIPTION:
XS GIS Cut Line= 3
       2017297.1     13457851.23      2017122.18     13458029.63
      2015229.62     13458843.55
#Sta/Elev= 30
  3649.7   460.4  3802.4   464.7  3899.5  463.64    3940  461.64  3977.3  458.28
  4024.3  450.64  4076.9  445.21  4190.4  437.06  4205.5  435.11    4229  428.67
    4258  425.89  4272.2   421.6  4272.8   420.8    4280   421.6  4288.4  426.49
  4299.2  428.18  4373.7  427.86    4680  426.28  4809.1  427.16  4974.1  427.92
  4995.9  423.14  5006.8  423.35  5028.6   427.6  5062.2  427.35  5213.1  427.43
  5406.5  428.16  5627.3  434.29  5732.2  440.81  5844.5  445.56  5959.7  444.67
#Mann= 9 ,-1 , 0
  3649.7      .1       0  4272.2      .1       0    4280      .1       0
  4373.7      .1       0  4809.1      .1       0  5062.2     .05       0
  5213.1      .1       0  5406.5      .1       0  5732.2      .1       0
#XS Ineff= 2 , 0
       0  4310.5     432               0
Permanent Ineff=
       F       F
Bank Sta=4974.1,5028.6
XS Rating Curve= 0 ,0
Exp/Cntr=0.3,0.1

Type RM Length L Ch R = 1 ,4944    ,430,430,430
BEGIN DESCRIPTION:
Mapping XS 1b90ead0
END DESCRIPTION:
XS GIS Cut Line= 3
      2017266.66     13457768.79      2016129.55      13458181.1
      2015023.75     13458740.51
#Sta/Elev= 30
  3607.5  456.02  3816.5  452.28  3877.8  448.49  4020.3  433.33  4162.4  427.91
  4193.4  422.21  4204.9  425.87  4259.9  426.83  4279.4  426.44  4310.6  420.94
    4322  423.63  4328.7  420.65  4329.3  419.85  4336.5  420.65  4346.5  421.67
  4353.9  426.47  4417.7  424.41  4449.6   420.8  4458.4  424.36  4481.5  425.96
  4599.2  425.42  4708.1  425.86  4971.6  426.62  4989.9   426.3  5001.5  426.74
  5139.3  426.06  5325.4  426.43  5686.8  439.56  5768.2  443.34  6056.3  442.47
#Mann= 9 ,-1 , 0
  3607.5      .1       0  4328.7     .07       0  4336.5      .1       0
  4599.2      .1       0  4708.1      .1       0  4989.9      .1       0
  5139.3      .1       0  5325.4      .1       0  5686.8      .1       0
#XS Ineff= 2 , 0
       0  4904.7     430               0
Permanent Ineff=
       F       F
Bank Sta=4971.6,5001.5
XS Rating Curve= 0 ,0
Exp/Cntr=0.3,0.1

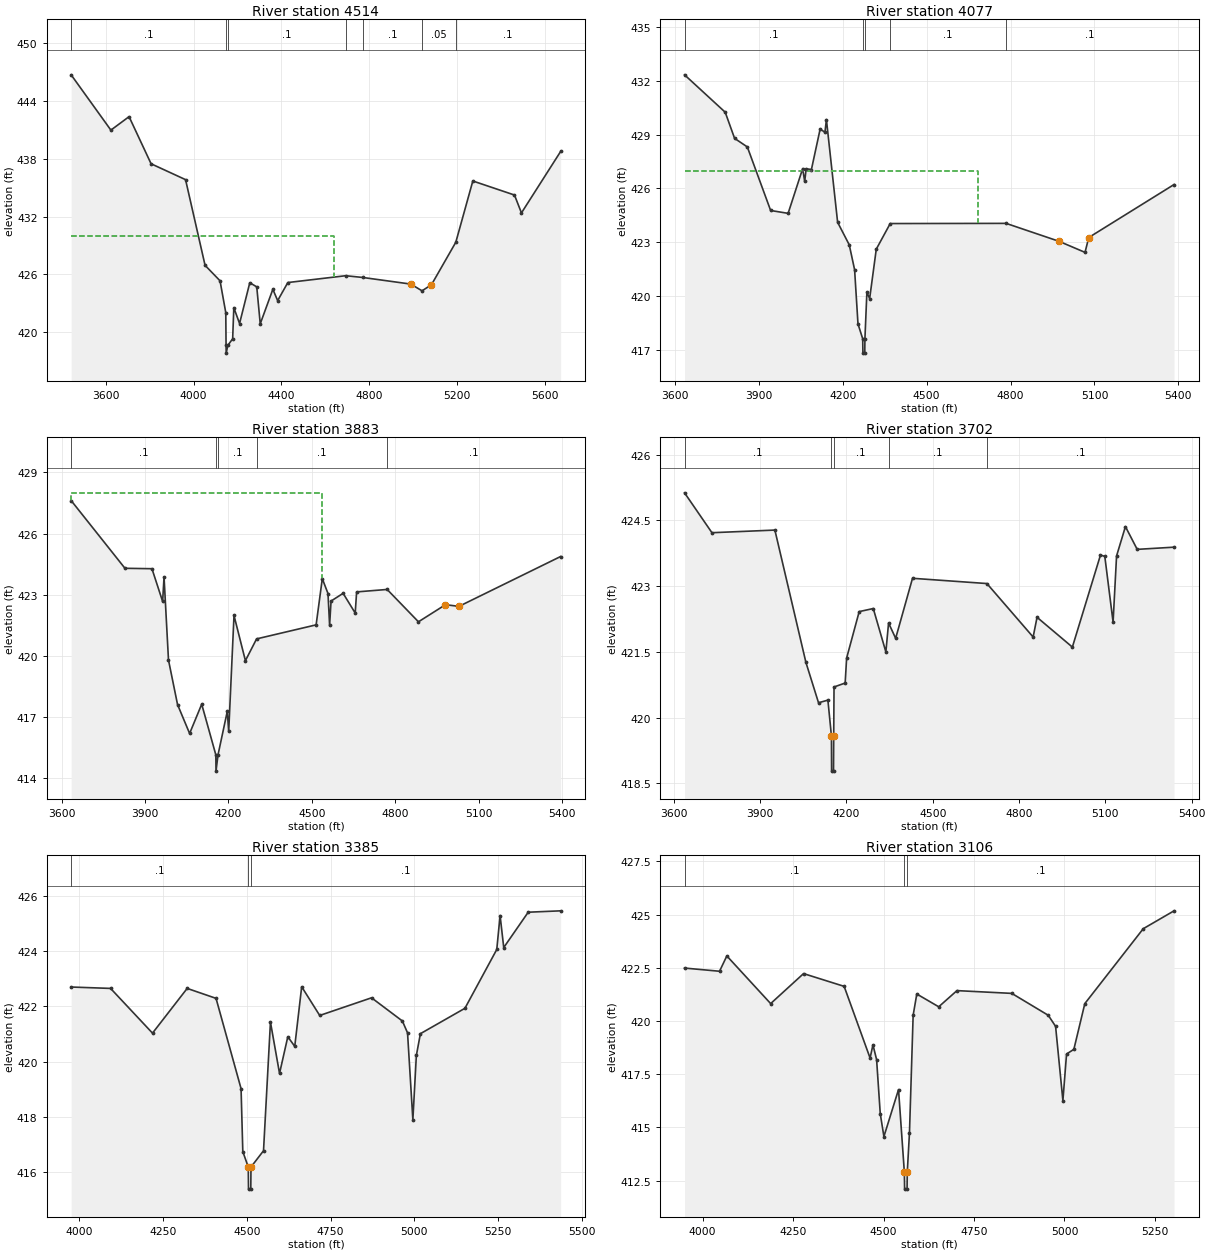
Type RM Length L Ch R = 1 ,4514    ,437,437,437
BEGIN DESCRIPTION:
UNT 030 in RCW 7.0
END DESCRIPTION:
XS GIS Cut Line= 2
      2017084.43      13457642.9      2014976.19     13458360.15
#Sta/Elev= 30
  3443.2  446.74    3624  440.99  3706.7  442.39  3806.9  437.49  3963.7  435.84
  4052.5  426.93  4120.6  425.32  4146.7  422.01    4148   418.6  4148.6   417.8
  4155.8   418.6    4178  419.29  4183.3  422.53  4209.4  420.88  4255.9  425.12
  4287.6  424.69  4303.5  420.85  4360.9  424.44  4382.7  423.26    4429  425.14
  4692.3  425.85  4769.1  425.67  4988.3  424.98  5039.5  424.28  5082.4  424.91
  5193.2  429.33  5270.6   435.7  5460.1  434.24  5491.8  432.38  5670.1  438.77
#Mann= 7 ,-1 , 0
  3443.2      .1       0    4148     .07       0  4155.8      .1       0
  4692.3      .1       0  4769.1      .1       0  5039.5     .05       0
  5193.2      .1       0
#XS Ineff= 2 , 0
       0 4637.33     430               0
Permanent Ineff=
       F       F
Bank Sta=4988.3,5082.4
XS Rating Curve= 0 ,0
Exp/Cntr=0.3,0.1

Type RM Length L Ch R = 1 ,4077    ,194,194,194
BEGIN DESCRIPTION:
UNT 030 in RCW 6.0
END DESCRIPTION:
XS GIS Cut Line= 3
      2016780.64     13457399.84      2015716.68     13457708.14
      2015098.88     13457884.13
#Sta/Elev= 30
  3634.5  432.35  3779.9  430.26  3813.4   428.8    3859  428.32  3942.3  424.77
  4004.8  424.61  4056.8  427.11  4064.1  426.39  4069.3   427.1  4088.1  427.06
  4119.3  429.32  4136.5  429.14  4141.7  429.85  4181.8  424.11  4223.4  422.85
  4242.5  421.46  4254.6  418.43  4271.5   417.6  4272.2   416.8  4278.8   416.8
  4279.4   417.6  4286.4   420.2  4296.3  419.85    4320  422.61  4369.8  424.04
  4784.1  424.05    4973  423.05  5066.3  422.43  5079.7  423.26  5384.6  426.22
#Mann= 5 ,-1 , 0
  3634.5      .1       0  4271.5     .07       0  4279.4      .1       0
  4369.8      .1       0  4784.1      .1       0
#XS Ineff= 2 , 0
       0  4681.9     427               0
Permanent Ineff=
       F       F
Bank Sta=4973,5079.7
XS Rating Curve= 0 ,0
Exp/Cntr=0.3,0.1

Type RM Length L Ch R = 1 ,3883    ,181,181,181
BEGIN DESCRIPTION:
Mapping XS b734e61e
END DESCRIPTION:
XS GIS Cut Line= 2
      2016706.83     13457317.38      2014988.18      13457700.8
#Sta/Elev= 30
    3634  427.62  3827.6  424.29  3924.7  424.27  3963.1  422.66  3968.2  423.86
  3984.2  419.78  4016.8  417.59  4060.2  416.17  4103.7  417.61  4154.5  415.12
  4155.1  414.32  4162.4  415.12  4195.7  417.26  4200.8  416.27  4219.9  421.97
  4260.9  419.75  4301.1  420.82  4515.3  421.51  4537.5  423.78    4558  423.05
  4563.8  421.49    4569  422.68  4612.4  423.06  4655.9  422.09    4661  423.13
  4770.8  423.25  4883.4  421.66  4980.5   422.5  5029.3  422.42  5394.9  424.87
#Mann= 5 ,-1 , 0
    3634      .1       0  4154.5     .07       0  4162.4      .1       0
  4301.1      .1       0  4770.8      .1       0
#XS Ineff= 2 , 0
       0  4537.5     428               0
Permanent Ineff=
       F       F
Bank Sta=4980.5,5029.3
XS Rating Curve= 0 ,0
Exp/Cntr=0.3,0.1

Type RM Length L Ch R = 1 ,3702    ,317,317,317
BEGIN DESCRIPTION:
Mapping XS 0b2adbb8
END DESCRIPTION:
XS GIS Cut Line= 2
      2016641.67     13457239.27      2014979.91     13457604.84
#Sta/Elev= 30
  3637.3  425.13  3732.5  424.22  3951.3  424.28  4059.2  421.26    4103  420.34
  4135.6   420.4  4147.9  419.58  4148.5  418.78  4155.1  418.78  4155.8  419.58
  4156.9   420.7  4195.6  420.79  4200.7  421.36  4244.4  422.42  4293.3  422.49
  4337.1   421.5  4346.5  422.16  4371.1  421.81  4429.7  423.18  4688.3  423.06
    4849  421.84  4862.6  422.29  4985.4  421.61  5083.1  423.71  5098.1  423.68
  5126.9  422.18    5139  423.69  5169.8  424.36  5210.7  423.84  5338.8  423.89
#Mann= 5 ,-1 , 0
  3637.3      .1       0  4147.9     .07       0  4155.8      .1       0
  4346.5      .1       0  4688.3      .1       0
Bank Sta=4147.9,4155.8
XS Rating Curve= 0 ,0
Exp/Cntr=0.3,0.1

Type RM Length L Ch R = 1 ,3385    ,279,279,279
BEGIN DESCRIPTION:
UNT 030 in RCW 5.0
END DESCRIPTION:
XS GIS Cut Line= 3
      2016459.41     13457048.29      2015538.29     13457295.82
      2015052.24     13457440.06
#Sta/Elev= 30
  3975.8   422.7  4093.5  422.65  4218.6  421.03  4322.1  422.65  4408.2  422.29
  4482.9  419.02  4488.1  416.74  4504.4  416.18  4505.1  415.38  4511.9  415.38
  4512.5  416.18  4549.9  416.77  4570.6  421.43  4597.7  419.57  4622.4   420.9
  4643.1  420.55  4663.8  422.71  4717.6  421.67  4872.3  422.31  4964.3  421.47
  4979.7  421.04  4995.6  417.89    5006  420.22  5018.1  421.01    5151  421.93
    5246  424.06  5255.9  425.29  5266.8  424.13  5339.8  425.41  5436.6  425.46
#Mann= 3 ,-1 , 0
  3975.8      .1       0  4504.4     .07       0  4512.5      .1       0
Bank Sta=4504.4,4512.5
XS Rating Curve= 0 ,0
Exp/Cntr=0.3,0.1

Type RM Length L Ch R = 1 ,3106    ,348,348,348
BEGIN DESCRIPTION:
Mapping XS 7ae1e364
END DESCRIPTION:
XS GIS Cut Line= 2
      2016450.76     13456939.78      2015110.76     13457126.12
#Sta/Elev= 30
  3949.9  422.49  4046.6  422.34  4066.8  423.06  4187.9  420.82  4278.8  422.23
    4391  421.63  4462.7  418.26  4470.6  418.88  4480.7  418.19  4490.8  415.65
  4500.9  414.57  4541.3  416.78  4557.4   412.9  4558.1   412.1  4564.9   412.1
  4565.5   412.9  4571.6  414.76  4581.7  420.27  4591.8  421.27  4652.4  420.67
  4702.8  421.43  4854.3   421.3  4955.2  420.27  4975.4  419.75  4995.6  416.26
  5005.7  418.45  5025.9  418.67  5056.2  420.82  5217.7  424.34  5302.8  425.18
#Mann= 3 ,-1 , 0
  3949.9      .1       0  4557.4     .07       0  4565.5      .1       0
Bank Sta=4557.4,4565.5
XS Rating Curve= 0 ,0
Exp/Cntr=0.3,0.1

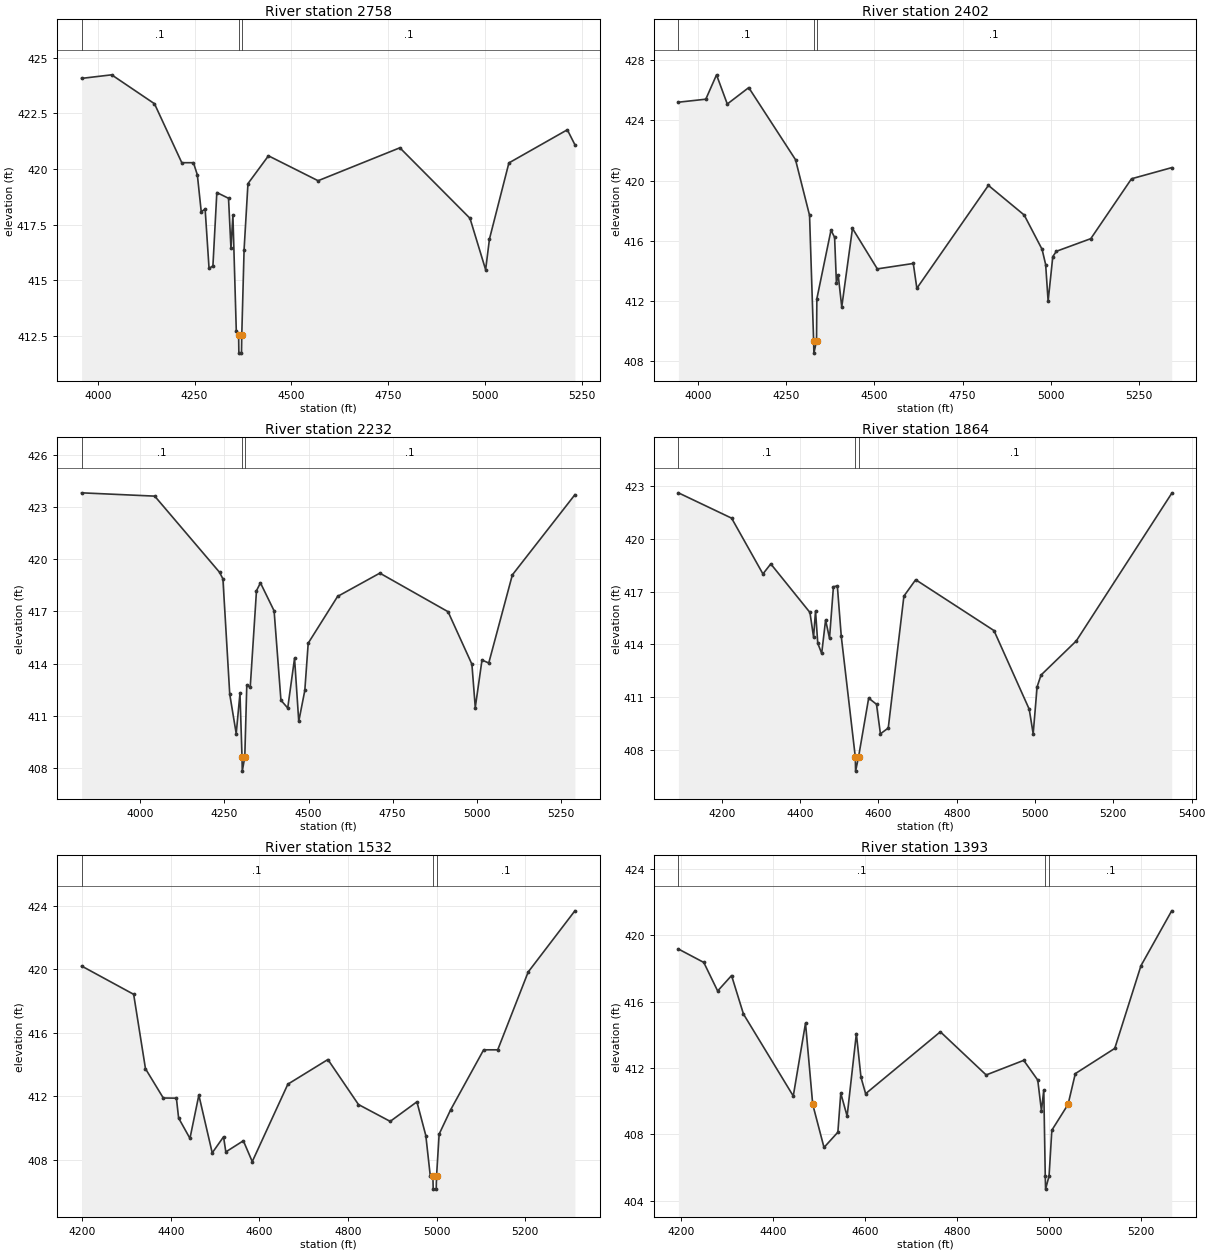
Type RM Length L Ch R = 1 ,2758    ,356,356,356
BEGIN DESCRIPTION:
Mapping XS 5c7c2744
END DESCRIPTION:
XS GIS Cut Line= 2
      2016342.26     13456718.43      2015075.63     13456855.28
#Sta/Elev= 30
  3958.3  424.07    4036  424.23  4146.6  422.93  4217.1  420.28  4247.2  420.28
  4257.3  419.73  4267.3  418.08  4277.4  418.19  4287.5  415.53  4297.5  415.64
  4307.6  418.94  4337.8  418.68  4344.1  416.43  4349.1  417.92  4357.9   412.7
  4363.9  412.52  4364.5  411.72  4371.3  411.72    4372  412.52    4378  416.37
    4388  419.34  4440.9  420.59  4569.1  419.47  4780.3  420.95  4961.4  417.78
  5001.8  415.47  5011.7  416.85  5061.9  420.27  5212.8  421.76  5232.3  421.09
#Mann= 3 ,-1 , 0
  3958.3      .1       0  4363.9     .07       0    4372      .1       0
Bank Sta=4363.9,4372
XS Rating Curve= 0 ,0
Exp/Cntr=0.3,0.1

Type RM Length L Ch R = 1 ,2402    ,170,170,170
BEGIN DESCRIPTION:
Mapping XS d5ed86b1
END DESCRIPTION:
XS GIS Cut Line= 2
      2016411.63     13456375.55      2015032.66     13456607.88
#Sta/Elev= 30
  3944.5  425.21  4022.2  425.41  4052.6  427.03  4083.1  425.09  4143.9  426.18
  4276.5  421.39  4316.3  417.69  4327.9  409.33  4328.6  408.53  4336.1  409.33
    4337  412.14  4377.1   416.7  4387.3  416.23  4392.5  413.19  4397.5  413.73
  4407.6   411.6    4438  416.82  4508.4  414.13  4610.4  414.49  4620.5  412.84
  4823.3  419.68  4924.8  417.71  4975.5  415.43  4985.6  414.42  4992.6  411.99
  5005.9  414.95    5016   415.3  5113.6  416.14    5229  420.12  5342.9  420.86
#Mann= 3 ,-1 , 0
  3944.5      .1       0  4327.9     .07       0  4336.1      .1       0
Bank Sta=4327.9,4336.1
XS Rating Curve= 0 ,0
Exp/Cntr=0.3,0.1

Type RM Length L Ch R = 1 ,2232    ,368,368,368
BEGIN DESCRIPTION:
UNT 030 in RCW 4.0
END DESCRIPTION:
XS GIS Cut Line= 3
      2016459.39     13456232.32        2015325.       13456425.
      2015009.56     13456402.18
#Sta/Elev= 30
  3825.1  423.82  4042.6  423.63  4235.3  419.25  4245.4  418.87  4265.7  412.23
  4284.9  409.97  4296.1  412.28  4302.2  408.61  4302.9  407.81  4310.4  408.61
  4316.4  412.77  4326.6  412.63  4345.2  418.19    4357  418.64  4397.6  417.03
  4417.9  411.89  4438.1  411.44  4458.4   414.3  4470.9  410.67  4488.9  412.45
    4499  415.17  4586.4  417.86    4712   419.2  4914.9  416.98  4985.8  413.96
  4995.8  411.47  5015.8   414.2  5035.9  414.03  5106.1   419.1    5292  423.71
#Mann= 3 ,-1 , 0
  3825.1      .1       0  4302.2     .07       0  4310.4      .1       0
Bank Sta=4302.2,4310.4
XS Rating Curve= 0 ,0
Exp/Cntr=0.3,0.1

Type RM Length L Ch R = 1 ,1864    ,332,332,332
BEGIN DESCRIPTION:
Mapping XS bf35f06a
END DESCRIPTION:
XS GIS Cut Line= 2
      2016350.91     13456136.83      2015091.26     13456148.25
#Sta/Elev= 30
  4089.3  422.61  4225.2  421.17  4305.2     418  4325.2  418.57  4425.2  415.81
  4434.5  414.41  4439.5  415.89  4445.2  414.06  4455.2  413.48  4465.2  415.38
  4475.2  414.34  4485.2  417.27  4495.2  417.32  4505.2  414.46  4541.1  407.59
  4541.8  406.79  4549.3  407.59  4575.2  410.94  4595.2  410.59  4605.2  408.91
  4625.2  409.24  4665.2  416.74  4695.2  417.67  4895.2  414.78  4985.2  410.31
  4995.3  408.91  5005.3  411.58  5015.3  412.25  5105.3  414.19    5349  422.58
#Mann= 3 ,-1 , 0
  4089.3      .1       0  4541.1     .07       0  4549.3      .1       0
Bank Sta=4541.1,4549.3
XS Rating Curve= 0 ,0
Exp/Cntr=0.3,0.1

Type RM Length L Ch R = 1 ,1532    ,139,139,139
BEGIN DESCRIPTION:
UNT 030 in RCW 3.0
END DESCRIPTION:
XS GIS Cut Line= 2
      2016168.58     13455828.68      2015059.99     13455937.31
#Sta/Elev= 30
  4198.4   420.2    4316  418.42  4342.7  413.74  4382.9   411.9  4412.5  411.89
  4417.5  410.64  4443.1  409.36  4463.2  412.08  4493.4  408.45    4519  409.46
  4524.1  408.51  4563.7  409.21  4583.8   407.9  4664.2  412.77  4754.6  414.32
  4823.6  411.49  4895.3  410.43  4955.6  411.66  4975.7  409.54  4985.7  407.02
  4991.7  406.97  4992.4  406.17  4999.2  406.17  4999.9  406.97  5005.8  409.63
  5031.6  411.15  5106.3  414.93  5138.1  414.93  5206.8  419.82  5312.3  423.67
#Mann= 3 ,-1 , 0
  4198.4      .1       0  4991.7     .07       0  4999.9      .1       0
Bank Sta=4991.7,4999.9
XS Rating Curve= 0 ,0
Exp/Cntr=0.3,0.1

Type RM Length L Ch R = 1 ,1393    ,395,395,395
BEGIN DESCRIPTION:
Mapping XS 8ae6b4ce
END DESCRIPTION:
XS GIS Cut Line= 3
      2016159.95     13455776.59      2015549.58     13455834.45
       2015099.5     13455745.99
#Sta/Elev= 30
  4194.5  419.17  4249.7  418.36  4279.8  416.64    4310  417.57  4335.9  415.25
  4444.1  410.31  4470.7   414.7 4486.36409.8073  4510.9  407.21    4541  408.13
  4547.3  410.48  4561.1   409.1  4581.2  414.07  4591.2  411.44  4601.3  410.45
  4763.7  414.18  4863.2  411.58  4944.8  412.46  4975.3  411.27  4983.3  409.42
  4988.4  410.68  4991.6   405.5  4992.3   404.7  4999.9   405.5  5005.9  408.25
 5041.15409.8063  5056.9  411.66  5142.6  413.18  5199.5  418.16  5266.3  421.47
#Mann= 3 ,-1 , 0
  4194.5      .1       0  4991.6     .07       0  4999.9      .1       0
Bank Sta=4486.36,5041.15
XS Rating Curve= 0 ,0
Exp/Cntr=0.3,0.1

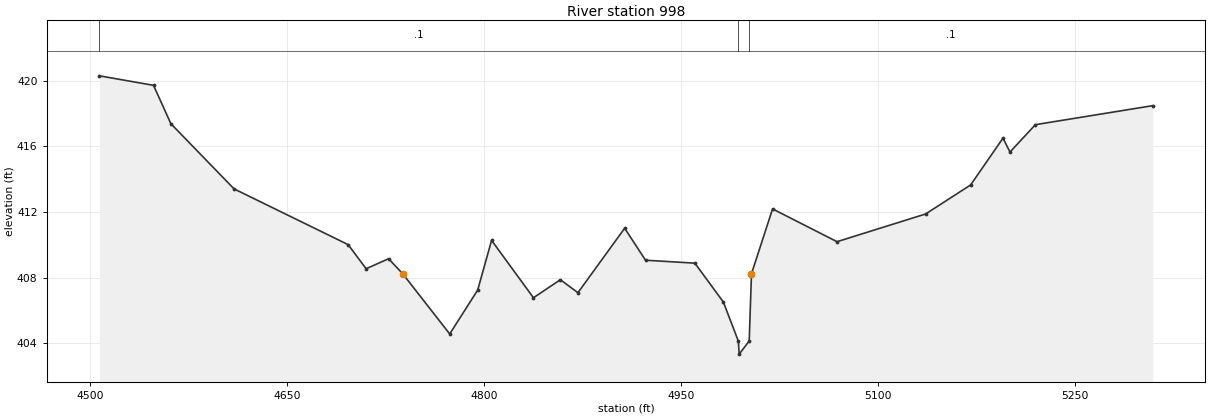
Type RM Length L Ch R = 1 ,998     ,319,319,319
BEGIN DESCRIPTION:
UNT 030 in RCW 2.0
END DESCRIPTION:
XS GIS Cut Line= 4
      2015916.29     13455495.14      2015599.27     13455608.97
      2015347.97     13455467.04      2015182.43     13455530.41
#Sta/Elev= 30
  4506.9  420.31  4548.2  419.73  4561.4  417.39  4609.6  413.41  4696.5  410.01
  4710.2  408.54  4727.3  409.15 4738.14408.2283  4773.9  404.56  4795.2  407.24
  4805.8  410.27  4837.7  406.77  4858.2  407.87  4871.6  407.08  4907.2  411.01
  4923.1  409.06  4960.7  408.88  4982.4  406.51  4993.8  404.13  4994.5  403.33
  5002.1  404.13 5003.84408.2323  5019.9  412.19    5069  410.19  5136.5  411.88
  5170.8  413.65  5195.5  416.51  5200.8  415.66  5220.2  417.33  5309.6  418.49
#Mann= 3 ,-1 , 0
  4506.9      .1       0  4993.8     .07       0  5002.1      .1       0
Bank Sta=4738.14,5003.84
XS Rating Curve= 0 ,0
Exp/Cntr=0.3,0.1