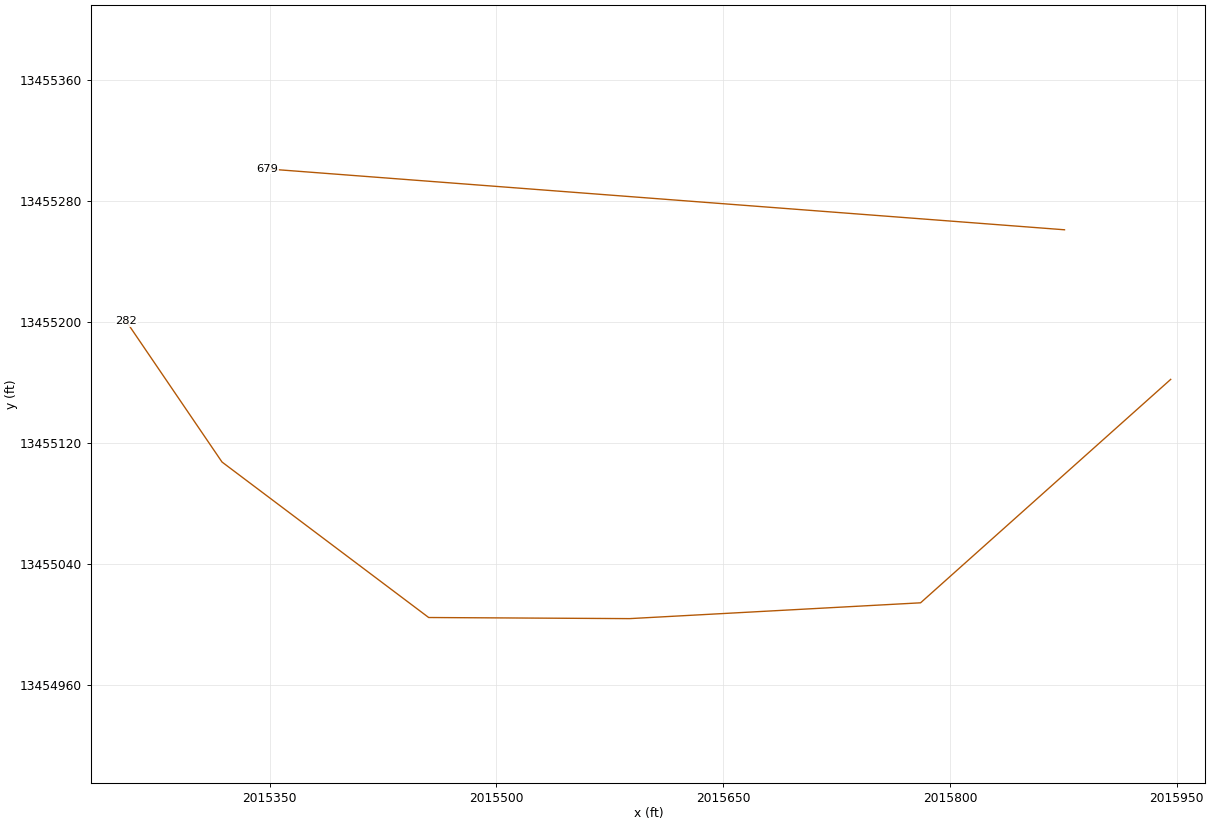
HEC-RAS study UNT 030 in RCW.prj: UNT 030 in RCW Base Level Engineering

--- UNT 030 in RCW.g01 (geometry) --- (continued)

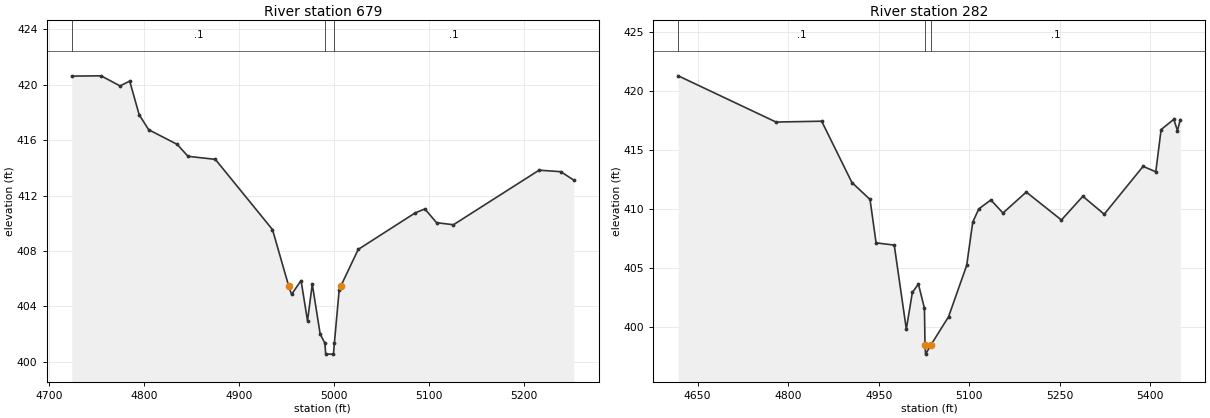
Type RM Length L Ch R = 1 ,679     ,397,397,397
BEGIN DESCRIPTION:
Mapping XS 3066c2e4
END DESCRIPTION:
XS GIS Cut Line= 2
       2015875.8     13455260.96      2015348.53     13455301.22
#Sta/Elev= 30
  4724.2  420.63  4755.1  420.65  4775.1  419.92  4785.2  420.27  4795.2  417.84
  4805.2  416.76  4835.3   415.7  4846.6  414.84  4875.4  414.62  4935.6  409.55
 4952.82405.4432  4955.7  404.87  4965.7  405.87  4972.5  402.96  4977.5  405.61
  4985.8  402.02  4990.7  401.36  4991.7  400.56  4999.8  400.56  5000.8  401.36
  5005.8  405.16 5007.37405.4427  5025.9  408.12    5086  410.76  5096.1  411.04
  5108.4  410.05  5126.2   409.9  5216.4  413.84  5239.2  413.73    5253  413.12
#Mann= 3 ,-1 , 0
  4724.2      .1       0  4990.7     .07       0  5000.8      .1       0
Bank Sta=4952.82,5007.37
XS Rating Curve= 0 ,0
Exp/Cntr=0.3,0.1

Type RM Length L Ch R = 1 ,282     ,0,0,0
BEGIN DESCRIPTION:
UNT 030 in RCW 1.0
END DESCRIPTION:
XS GIS Cut Line= 6
      2015946.05       13455162.      2015780.59     13455014.19
      2015588.11     13455003.73      2015455.18     13455004.46
      2015318.46     13455107.32      2015255.03     13455200.52
#Sta/Elev= 30
  4618.1  421.31    4780  417.39  4855.6  417.46  4905.7  412.26  4935.7  410.82
  4945.7  407.14  4975.8  406.95  4995.8  399.82  5005.8  402.94  5015.8  403.64
  5025.8   401.6  5026.7   398.5  5027.7   397.7  5036.8   398.5  5065.8  400.88
  5095.8  405.24  5105.8   408.9  5115.8  410.02  5135.8  410.78  5155.8  409.67
  5194.4  411.45  5252.6  409.08  5288.1  411.09  5323.5  409.57  5387.9  413.63
  5408.9  413.17  5417.7  416.75  5438.7  417.62  5444.8  416.66  5449.5  417.59
#Mann= 3 ,-1 , 0
  4618.1      .1       0  5026.7     .07       0  5036.8      .1       0
Bank Sta=5026.7,5036.8
XS Rating Curve= 0 ,0
Exp/Cntr=0.3,0.1
LCMann Table=0

Chan Stop Cuts=-1
Use User Specified Reach Order=0
Composite Channel Slope=5