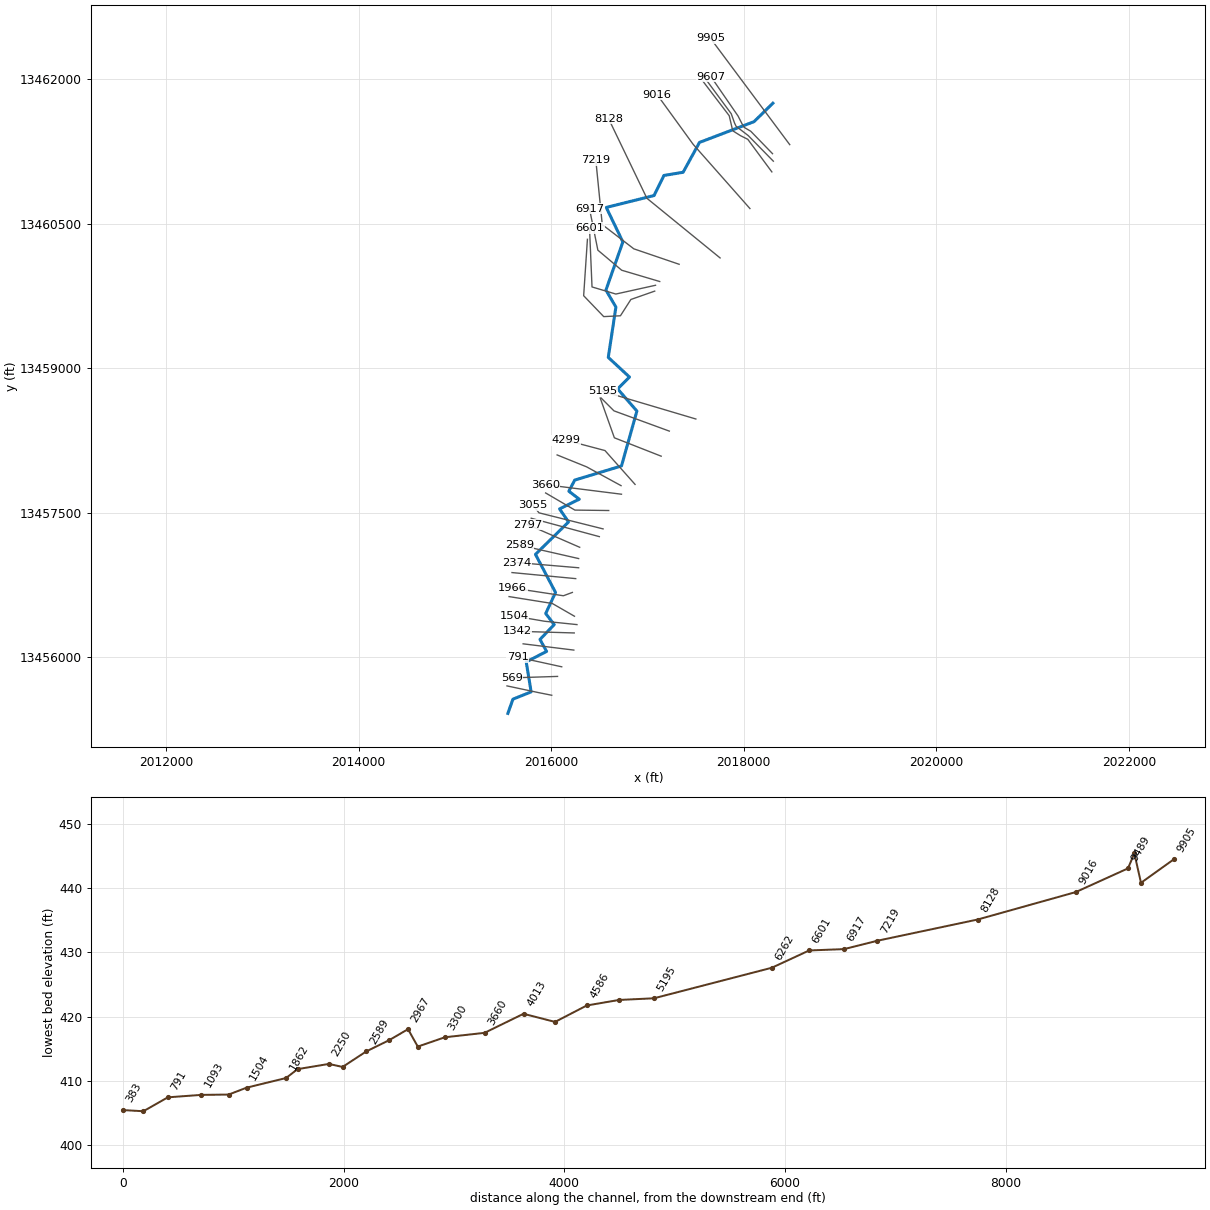
--- UNT 031 in RCW.prj (project) ---

Proj Title=UNT 031 in RCW Base Level Engineering
Current Plan=p01
Default Exp/Contr=0.3,0.1
English Units
Geom File=g01
Flow File=f01
Plan File=p01
Y Axis Title=Elevation
X Axis Title(PF)=Main Channel Distance
X Axis Title(XS)=Station
BEGIN DESCRIPTION:
UNT 031 in RCW
END DESCRIPTION:
DSS Export Rating Curves= 0
DSS Export Rating Curve Sorted= 0
DSS Export Volume Flow Curves= 0
DXF OffsetX= 0
DXF OffsetY= 0
DXF ScaleX= 1
DXF ScaleY= 10

--- UNT 031 in RCW.p01 (plan) ---

Plan Title=Multiple Run
Short Identifier=Multiple
Geom File=g01
Flow File=f01
Subcritical Flow
K Sum by GR= 0
Std Step Tol= 0.01
Critical Tol= 0.01
Num of Std Step Trials= 20
Max Error Tol= 0.3
Flow Tol Ratio= 0.001
Split Flow NTrial= 30
Split Flow Tol= 0.02
Split Flow Ratio= 0.02
Log Output Level= 0
Friction Slope Method= 1
Unsteady Friction Slope Method= 2
Unsteady Bridges Friction Slope Method= 1
Parabolic Critical Depth
Global Vel Dist=  1 , 1 , 1
Global Log Level= 0
CheckData=True
Encroach Param= -1, 0, 0, 0
BEGIN DESCRIPTION:
Multiple Run
END DESCRIPTION:

--- UNT 031 in RCW.f01 (steady flow) ---

Flow Title=Multiple
Number of Profiles=7
Profile Names=10-year,25-year,50-year,1pct_min,100-year,1pct_plu,500-year
River Rch & RM= UNT 031 in RCW,Reach-1,9905
     176     239     291     177     353     704     526
River Rch & RM= UNT 031 in RCW,Reach-1,7219
     196     268     327     199     397     792     594
Boundary for River Rch & Prof#=UNT 031 in RCW,Reach-1,1
Up Type=0
Dn Type=3
Dn Slope=0.005
Boundary for River Rch & Prof#=UNT 031 in RCW,Reach-1,2
Up Type=0
Dn Type=3
Dn Slope=0.005
Boundary for River Rch & Prof#=UNT 031 in RCW,Reach-1,3
Up Type=0
Dn Type=3
Dn Slope=0.005
Boundary for River Rch & Prof#=UNT 031 in RCW,Reach-1,4
Up Type=0
Dn Type=3
Dn Slope=0.005
Boundary for River Rch & Prof#=UNT 031 in RCW,Reach-1,5
Up Type=0
Dn Type=3
Dn Slope=0.005
Boundary for River Rch & Prof#=UNT 031 in RCW,Reach-1,6
Up Type=0
Dn Type=3
Dn Slope=0.005
Boundary for River Rch & Prof#=UNT 031 in RCW,Reach-1,7
Up Type=0
Dn Type=3
Dn Slope=0.005

--- UNT 031 in RCW.g01 (geometry) ---

Geom Title=Existing Conditions
Program Version=5.05

River Reach=UNT 031 in RCW  ,Reach-1
Reach XY= 30
      2018303.05     13461751.63      2018107.52     13461560.23
       2017540.8     13461344.54       2017370.8     13461034.54
      2017171.38     13461001.23       2017069.3      13460792.9
      2016572.77     13460669.29      2016744.99     13460310.96
       2016569.3     13459810.96      2016672.77     13459634.57
      2016593.61     13459111.65      2016813.96      13458907.7
       2016690.8     13458784.54       2016890.8     13458554.54
       2016730.8     13457984.54      2016245.48     13457837.64
      2016183.85     13457722.19      2016292.36     13457638.86
      2016087.49     13457538.16       2016180.9     13457402.33
      2015837.49     13457065.94      2016045.83     13456670.11
       2015943.4     13456451.36      2016031.94     13456336.77
      2015884.37     13456182.26      2015952.95     13456058.13
      2015741.16      13455948.8      2015792.36     13455637.99
      2015603.38     13455562.12       2015550.8     13455414.54

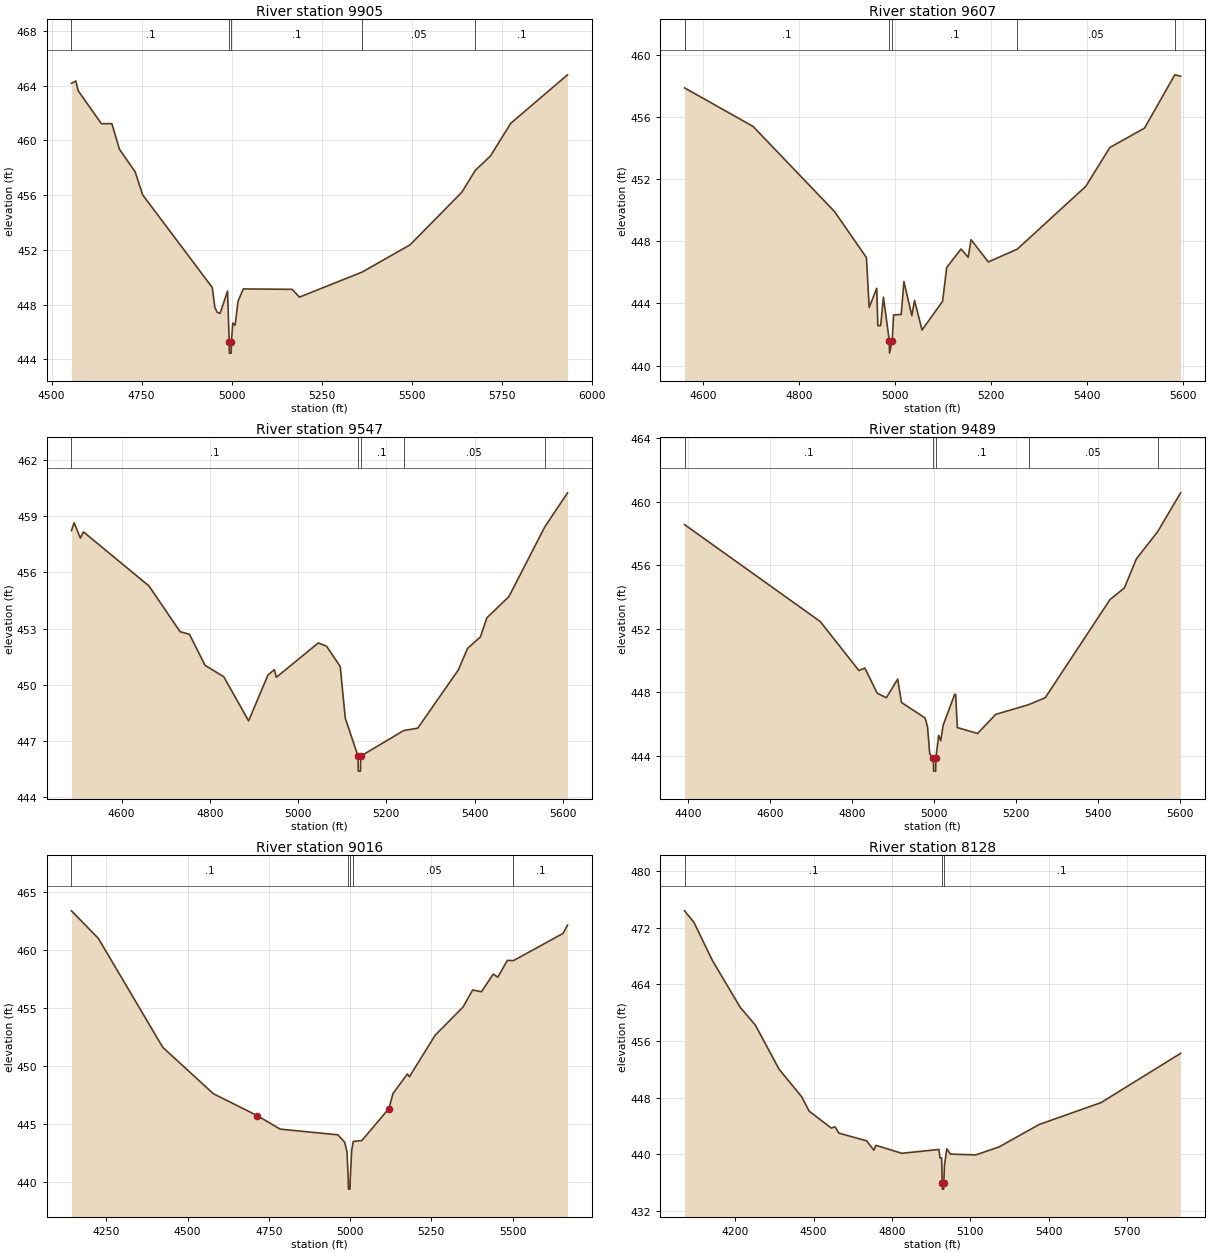
Type RM Length L Ch R = 1 ,9905    ,298,298,298
BEGIN DESCRIPTION:
Mapping XS 6022f9db
END DESCRIPTION:
XS GIS Cut Line= 2
      2018478.18     13461321.51      2017655.26     13462425.68
#Sta/Elev= 30
  4555.4  464.17  4567.5  464.34  4573.8  463.64  4638.4  461.22  4667.6  461.22
  4688.5  459.36  4732.3   457.7  4753.1  456.02  4946.4  449.25  4953.3  447.82
  4959.5  447.45  4967.9  447.36  4988.7  448.99  4993.3  445.26  4993.8  444.46
  4998.8  444.46  4999.3  445.26  5003.3  446.66  5009.6  446.49  5017.9  448.26
  5032.5  449.15  5168.1  449.12  5188.3  448.55  5362.3  450.38  5495.4  452.37
  5639.3  456.22  5676.4  457.81  5718.6  458.86  5774.9  461.25  5932.5  464.79
#Mann= 5 ,-1 , 0
  4555.4      .1       0  4993.3     .07       0  4999.3      .1       0
  5362.3     .05       0  5676.4      .1       0
Bank Sta=4993.3,4999.3
XS Rating Curve= 0 ,0
Exp/Cntr=0.3,0.1

Type RM Length L Ch R = 1 ,9607    ,60,60,60
BEGIN DESCRIPTION:
UNT 031 in RCW 4.0
END DESCRIPTION:
XS GIS Cut Line= 6
      2018299.35     13461227.77      2018073.67      13461460.4
      2018005.96     13461500.33      2017985.13     13461533.32
      2017941.72     13461618.39      2017660.46     13462026.39
#Sta/Elev= 30
  4561.9  457.87  4704.5  455.39  4874.2  449.91  4940.5  446.95  4946.3  443.74
    4962  444.97  4964.3  442.57  4970.2  442.57  4975.9   444.4  4988.2   441.6
  4988.7   440.8  4994.2   441.6  4997.1  443.26    5013  443.29  5018.6  445.41
  5035.1  443.21  5040.7  444.19  5056.3  442.29  5099.1  444.13  5107.7  446.31
  5137.5   447.5  5152.4  446.97  5158.4   448.1  5194.3  446.67  5254.6  447.49
  5397.2  451.53  5447.3  454.03  5519.5  455.28  5582.6  458.71  5594.7  458.62
#Mann= 5 ,-1 , 0
  4561.9      .1       0  4988.2     .07       0  4994.2      .1       0
  5254.6     .05       0  5582.6      .1       0
Bank Sta=4988.2,4994.2
XS Rating Curve= 0 ,0
Exp/Cntr=0.3,0.1

Type RM Length L Ch R = 1 ,9547    ,58,58,58
BEGIN DESCRIPTION:
Mapping XS e38f3dbf
END DESCRIPTION:
XS GIS Cut Line= 6
      2018308.05     13461149.63      2018047.63     13461415.26
      2017920.89     13461512.49      2017905.26     13461545.47
      2017870.54     13461642.69      2017601.46     13462007.25
#Sta/Elev= 30
  4486.2  458.24  4492.2  458.66  4506.4  457.84  4513.4  458.17  4661.8  455.28
  4732.5  452.83  4753.8  452.69  4789.1  451.03  4831.5  450.42  4887.8  448.06
  4931.6  450.51  4946.2   450.8  4950.6  450.39  5045.9  452.23  5064.6  452.05
  5095.5  450.97    5107   448.2  5135.9  446.17  5136.4  445.37  5141.4  445.37
  5141.9  446.17  5239.4  447.54  5271.3  447.67  5363.2  450.78  5384.3  451.94
  5413.3  452.55  5427.9  453.57    5478  454.71  5559.1  458.43  5610.8  460.26
#Mann= 5 ,-1 , 0
  4486.2      .1       0  5135.9     .07       0  5141.9      .1       0
  5239.4     .05       0  5559.1      .1       0
Bank Sta=5135.9,5141.9
XS Rating Curve= 0 ,0
Exp/Cntr=0.3,0.1

Type RM Length L Ch R = 1 ,9489    ,473,473,473
BEGIN DESCRIPTION:
Mapping XS 8f3d832f
END DESCRIPTION:
XS GIS Cut Line= 6
      2018292.42     13461038.52      2018042.42     13461377.07
      2017966.03     13461415.26      2017886.17     13461465.61
      2017849.71     13461621.86      2017577.15     13461979.48
#Sta/Elev= 30
  4391.6  458.55  4722.9  452.45  4817.1  449.37  4831.9  449.52  4861.8  447.94
  4884.2  447.66  4911.8  448.83  4921.1  447.36  4978.8  446.38  4984.7  445.83
    4990  444.13    4999  443.84  4999.5  443.04  5004.5  443.04    5005  443.84
  5011.8  445.29  5016.9  444.95  5022.7  445.92  5050.9  447.87  5053.3  447.87
  5057.4  445.78  5106.8  445.41  5151.1  446.61  5231.3  447.22    5272  447.66
  5429.9  453.83  5465.2  454.57  5494.3  456.39  5546.5  458.11  5602.4  460.55
#Mann= 5 ,-1 , 0
  4391.6      .1       0    4999     .07       0    5005      .1       0
  5231.3     .05       0  5546.5      .1       0
Bank Sta=4999,5005
XS Rating Curve= 0 ,0
Exp/Cntr=0.3,0.1

Type RM Length L Ch R = 1 ,9016    ,888,888,888
BEGIN DESCRIPTION:
UNT 031 in RCW 3.0
END DESCRIPTION:
XS GIS Cut Line= 3
       2018064.8     13460657.85        2017475.       13461325.
      2017101.32     13461840.05
#Sta/Elev= 30
  4142.3  463.39  4225.1  461.01  4423.4   451.6    4579   447.6  4713.6  445.71
  4784.8  444.54  4962.1  444.05    4983  443.42  4990.5  442.57  4994.2  440.16
  4994.7  439.36  4999.7  439.36  5000.2  440.16  5004.8  442.69  5009.6  443.48
  5035.9  443.55  5119.3  446.31  5132.1  447.62  5176.2   449.3  5182.4  449.06
    5262  452.66  5347.8  455.09  5377.2  456.56  5404.2   456.4  5440.5  457.93
  5454.5  457.66  5483.9  459.11  5502.7  459.09  5655.5  461.44  5669.1  462.16
#Mann= 5 ,-1 , 0
  4142.3      .1       0  4994.2     .07       0  5000.2      .1       0
  5009.6     .05       0  5502.7      .1       0
Bank Sta=4713.6,5119.3
XS Rating Curve= 0 ,0
Exp/Cntr=0.3,0.1

Type RM Length L Ch R = 1 ,8128    ,909,909,909
BEGIN DESCRIPTION:
UNT 031 in RCW 2.0
END DESCRIPTION:
XS GIS Cut Line= 3
      2017754.85     13460144.88      2016994.46     13460764.66
       2016596.7     13461591.37
#Sta/Elev= 30
  4006.3  474.39  4042.2  472.76  4112.6   467.4  4219.6  460.75    4277  458.27
  4368.2  452.02  4454.4  448.14  4483.1  446.11  4567.8  443.72  4582.2   443.9
  4596.6  443.01  4702.8  441.92  4730.8   440.6  4738.8  441.28  4837.8  440.16
    4980   440.7  4983.7  439.51  4990.2  439.51  4992.4   435.9  4992.9   435.1
  4997.9   435.1  4998.4   435.9  5000.9  438.45  5009.9  440.79  5023.6  440.04
  5120.8  439.93  5210.1  441.06    5363  444.22  5600.4  447.32  5904.7  454.27
#Mann= 3 ,-1 , 0
  4006.3      .1       0  4992.4     .07       0  4998.4      .1       0
Bank Sta=4992.4,4998.4
XS Rating Curve= 0 ,0
Exp/Cntr=0.3,0.1

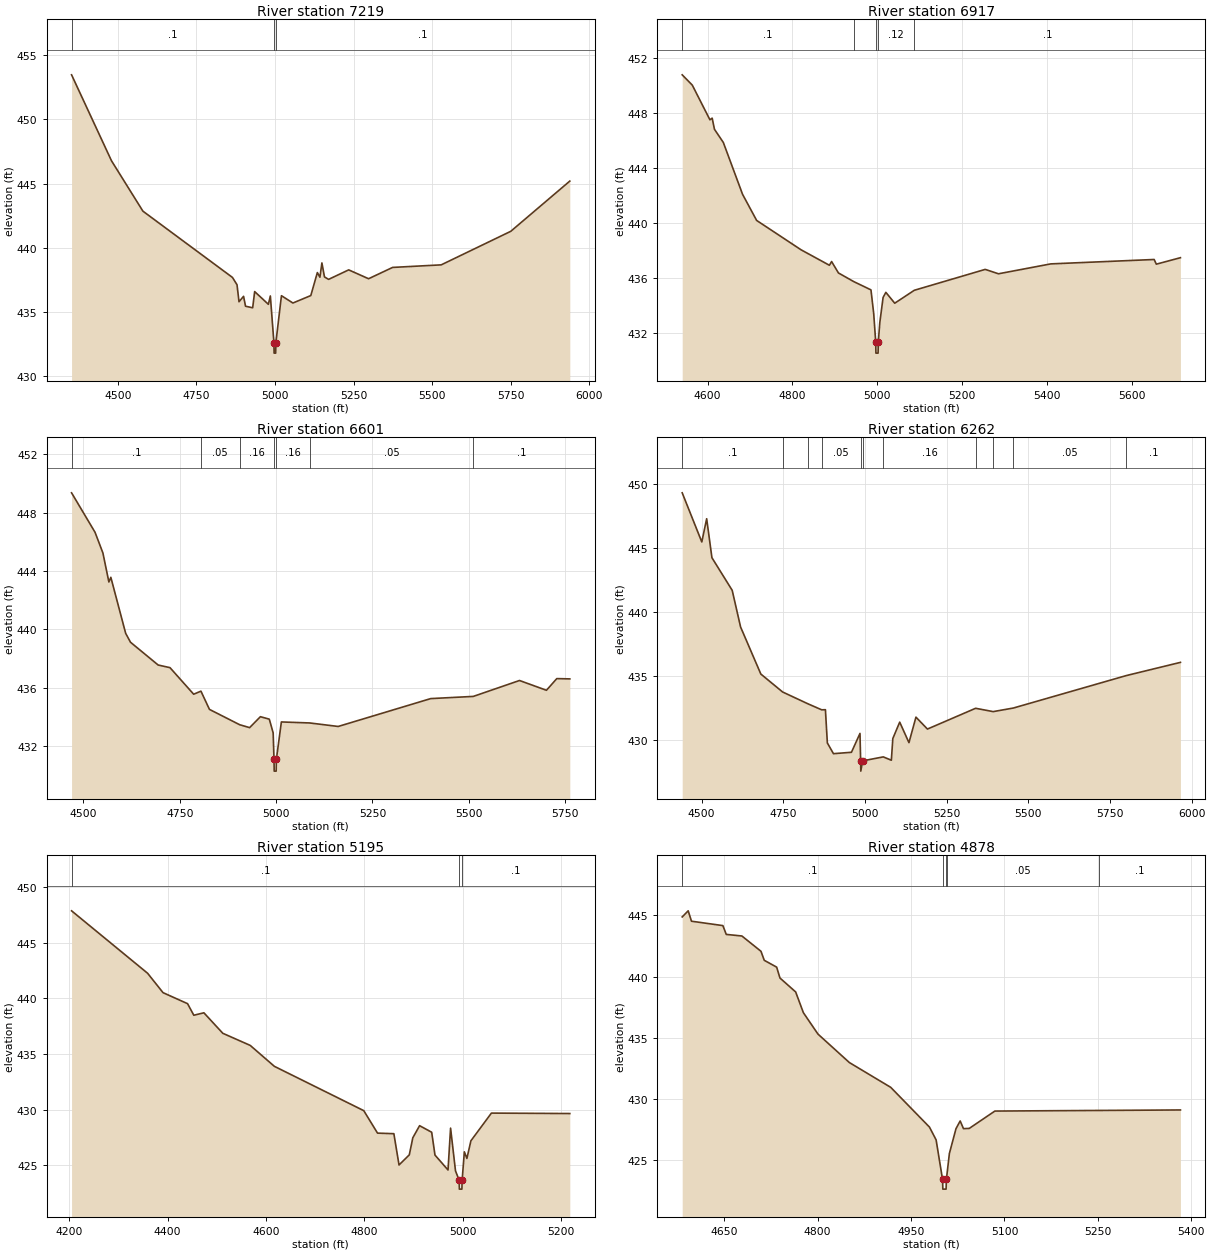
Type RM Length L Ch R = 1 ,7219    ,302,302,302
BEGIN DESCRIPTION:
Mapping XS 1096534a
END DESCRIPTION:
XS GIS Cut Line= 4
      2017329.73     13460078.87      2016858.78     13460239.47
      2016531.09     13460491.21      2016464.01     13461161.95
#Sta/Elev= 30
    4353  453.46    4480  446.77  4579.9  442.85  4864.8  437.69  4879.3  437.12
  4885.6   435.8  4900.1  436.22  4906.4  435.45  4929.1  435.33  4935.4  436.59
    4979   435.6  4985.3  436.25  4996.7   432.6  4997.2   431.8  5002.3   431.8
  5002.8   432.6  5020.6  436.27  5057.1   435.7    5114  436.28  5134.8  438.07
    5143  437.71  5149.3  438.82  5157.5  437.73  5170.6  437.54  5234.5  438.28
  5297.8  437.59  5374.2  438.47  5528.9  438.67    5750  441.28  5937.9  445.19
#Mann= 3 ,-1 , 0
    4353      .1       0  4996.7     .07       0  5002.8      .1       0
Bank Sta=4996.7,5002.8
XS Rating Curve= 0 ,0
Exp/Cntr=0.3,0.1

Type RM Length L Ch R = 1 ,6917    ,316,316,316
BEGIN DESCRIPTION:
Mapping XS 491e635d
END DESCRIPTION:
XS GIS Cut Line= 4
      2017127.85     13459899.99      2016732.84     13460017.19
      2016485.44     13460225.52      2016398.64     13460655.18
#Sta/Elev= 30
  4540.3  450.74  4564.1  449.99  4605.6  447.47  4610.9  447.59  4616.3  446.78
  4637.2  445.82  4682.5  442.05  4715.7  440.15  4820.6  438.01  4887.1  436.89
  4892.3  437.16  4908.4  436.33  4944.6   435.7    4985   435.1  4991.5  433.37
  4996.2   431.3  4996.7   430.5  5001.8   430.5  5002.3   431.3  5005.8  432.71
  5013.6  434.55  5020.1  434.92    5041  434.13  5087.1  435.07  5254.2  436.59
  5285.4  436.27  5408.6  436.99  5652.2  437.31  5657.3  436.97  5714.1  437.44
#Mann= 5 ,-1 , 0
  4540.3      .1       0  4944.6     .12       0  4996.2     .07       0
  5002.3     .12       0  5087.1      .1       0
Bank Sta=4996.2,5002.3
XS Rating Curve= 0 ,0
Exp/Cntr=0.3,0.1

Type RM Length L Ch R = 1 ,6601    ,339,339,339
BEGIN DESCRIPTION:
Mapping XS c6968b53
END DESCRIPTION:
XS GIS Cut Line= 4
      2017084.35     13459860.93      2016672.08      13459769.8
      2016424.68     13459843.58      2016398.64     13460455.53
#Sta/Elev= 30
  4469.4  449.36  4530.2  446.66  4550.7  445.24  4566.2  443.25  4571.3  443.57
  4609.8  439.73  4622.4  439.12  4694.1  437.56  4724.8  437.38  4786.2  435.56
  4805.1  435.77  4827.2  434.52  4905.6  433.47  4931.4  433.27  4959.4  434.02
  4982.5  433.85  4992.5  432.91  4994.7  431.09  4995.2  430.29  5000.3  430.29
  5000.8  431.09  5013.8  433.66  5087.6  433.59  5161.2  433.35  5401.4  435.26
  5511.9  435.41  5631.7   436.5  5701.7  435.83  5728.5  436.63  5762.3  436.61
#Mann= 7 ,-1 , 0
  4469.4      .1       0  4805.1     .05       0  4905.6     .16       0
  4994.7     .07       0  5000.8     .16       0  5087.6     .05       0
  5511.9      .1       0
Bank Sta=4994.7,5000.8
XS Rating Curve= 0 ,0
Exp/Cntr=0.3,0.1

Type RM Length L Ch R = 1 ,6262    ,1067,1067,1067
BEGIN DESCRIPTION:
Mapping XS 8f64fefc
END DESCRIPTION:
XS GIS Cut Line= 6
      2017075.69     13459800.17      2016828.33     13459713.37
      2016719.82      13459544.1      2016546.21     13459535.42
      2016337.87     13459752.43      2016376.94     13460338.36
#Sta/Elev= 30
  4440.7   449.3  4500.7  445.47  4515.6  447.28  4531.7  444.24  4593.7   441.7
  4619.4  438.84  4681.4  435.17  4748.1  433.77  4825.5  432.85  4867.7  432.38
  4879.1  432.39    4885   429.8  4903.7  428.96  4958.8  429.07  4984.9  430.54
  4986.9   428.4  4987.4   427.6    4993   428.4  5056.1  428.71  5080.9  428.45
  5085.4  430.14  5106.5  431.42  5134.8  429.82  5156.2  431.81  5191.4  430.88
  5338.9   432.5  5392.6  432.24  5454.4  432.52    5800  435.05  5965.8  436.08
#Mann= 11 ,-1 , 0
  4440.7      .1       0  4748.1     .05       0  4825.5     .16       0
  4867.7     .05       0  4986.9    .035       0    4993     .05       0
  5056.1     .16       0  5338.9     .05       0  5392.6     .16       0
  5454.4     .05       0    5800      .1       0
Bank Sta=4986.9,4993
XS Rating Curve= 0 ,0
Exp/Cntr=0.3,0.1

Type RM Length L Ch R = 1 ,5195    ,317,317,317
BEGIN DESCRIPTION:
Mapping XS 2195157c
END DESCRIPTION:
XS GIS Cut Line= 2
      2017503.21     13458472.06       2016532.2     13458760.33
#Sta/Elev= 30
  4204.7  447.86  4359.3  442.25  4390.6  440.51  4440.5  439.52  4453.2  438.48
  4473.7   438.7  4512.1  436.86  4567.9  435.77    4617  433.89  4798.7  429.91
  4826.7  427.89  4859.9  427.84  4870.4  425.03  4891.3  425.94  4898.4  427.47
  4912.2  428.56  4936.8  427.97  4943.5  425.92    4970  424.58  4975.2  428.34
  4985.2   424.5  4992.6  423.66  4993.1  422.86  4998.2  422.86  4998.7  423.66
  5003.2  426.21  5008.4  425.62  5016.5   427.2  5058.2  429.69  5217.6  429.65
#Mann= 3 ,-1 , 0
  4204.7      .1       0  4992.6     .07       0  4998.7      .1       0
Bank Sta=4992.6,4998.7
XS Rating Curve= 0 ,0
Exp/Cntr=0.3,0.1

Type RM Length L Ch R = 1 ,4878    ,292,292,292
BEGIN DESCRIPTION:
Mapping XS f294d13c
END DESCRIPTION:
XS GIS Cut Line= 3
      2017227.63     13458346.18      2016652.54     13458556.69
      2016520.17     13458689.06
#Sta/Elev= 30
  4582.8  444.88  4592.4  445.38  4597.7  444.53  4648.1  444.17  4653.5  443.45
  4678.6  443.32  4709.2  442.07  4714.5  441.33  4734.4  440.77  4739.7  439.88
  4764.9  438.74  4777.3  437.04  4800.7  435.29  4851.1  432.96  4917.5  430.93
  4979.6  427.68  4990.3  426.63  5000.6   423.4  5001.1   422.6  5006.3   422.6
  5006.8   423.4  5007.3  423.62  5011.6  425.52  5022.2  427.55  5028.9  428.18
  5034.2  427.55  5043.5  427.57  5084.6  428.99  5252.4  429.04  5382.4  429.08
#Mann= 5 ,-1 , 0
  4582.8      .1       0  5000.6     .07       0  5006.8      .1       0
  5007.3     .05       0  5252.4      .1       0
Bank Sta=5000.6,5006.8
XS Rating Curve= 0 ,0
Exp/Cntr=0.3,0.1

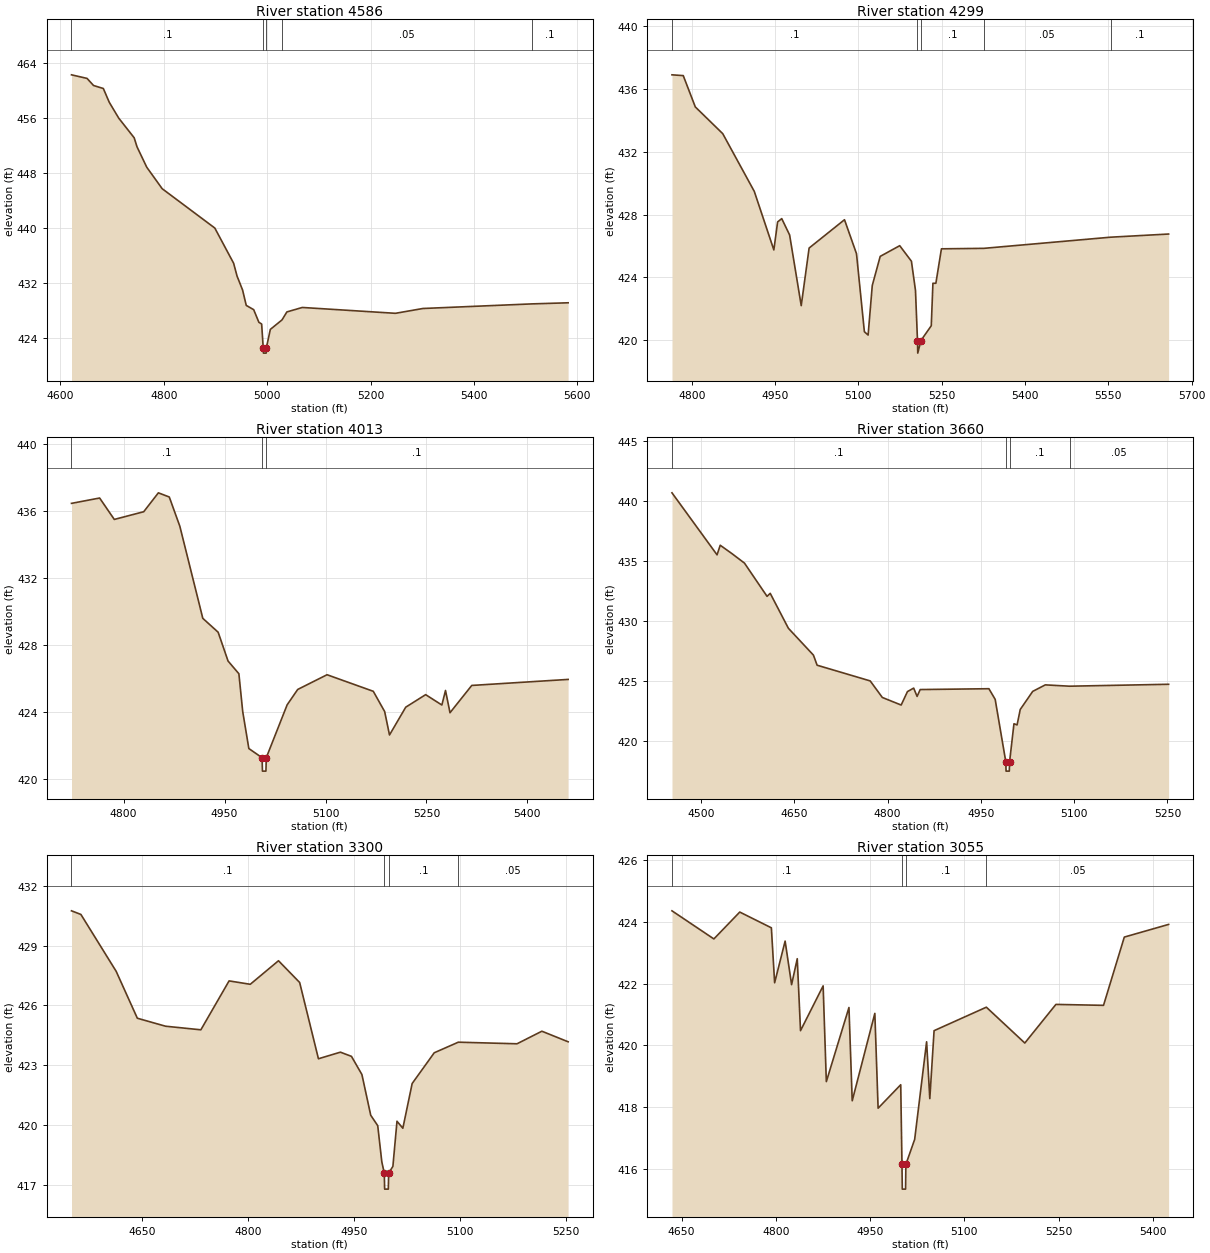
Type RM Length L Ch R = 1 ,4586    ,287,287,287
BEGIN DESCRIPTION:
Mapping XS 93f567bd
END DESCRIPTION:
XS GIS Cut Line= 3
      2017142.99     13458085.77      2016656.88     13458276.74
      2016509.87     13458689.67
#Sta/Elev= 30
  4621.6  462.21  4651.7  461.69  4664.2  460.66  4683.2  460.22  4694.7  458.21
    4713  455.91  4742.8  453.06  4748.4  451.73  4767.2  448.77    4797  445.65
  4898.8  439.93  4935.2  434.81  4941.8  432.95  4952.5  430.92  4959.6  428.68
    4974  428.06    4984  426.23  4989.4  425.97  4992.4  422.54  4992.9  421.74
  4998.1  421.74  4998.6  422.54  5006.2  425.19  5028.8  426.57  5038.2  427.73
    5068  428.38  5248.2  427.53  5301.3  428.23  5512.4   428.9  5582.2  429.06
#Mann= 5 ,-1 , 0
  4621.6      .1       0  4992.4     .07       0  4998.6      .1       0
  5028.8     .05       0  5512.4      .1       0
Bank Sta=4992.4,4998.6
XS Rating Curve= 0 ,0
Exp/Cntr=0.3,0.1

Type RM Length L Ch R = 1 ,4299    ,286,286,286
BEGIN DESCRIPTION:
Mapping XS 54b0bfe3
END DESCRIPTION:
XS GIS Cut Line= 3
       2016871.7     13457792.83      2016559.23     13458144.36
      2016149.56     13458252.74
#Sta/Elev= 30
  4764.4  436.88  4784.7  436.83  4806.4  434.84  4855.8  433.14  4912.6  429.47
  4947.8  425.75  4954.6  427.53    4962  427.74  4976.2   426.7  4997.1  422.21
  5011.3  425.87    5075  427.67  5096.6  425.51  5110.8  420.55  5117.5  420.34
    5125  423.49  5139.3  425.34  5174.4  426.02  5195.5  425.03  5202.8  423.17
  5206.4  419.99  5206.9  419.19  5212.6  419.99  5231.2  420.93  5234.2  423.63
  5239.5  423.63  5249.5  425.82  5325.8  425.85  5554.3  426.56  5658.5  426.76
#Mann= 5 ,-1 , 0
  4764.4      .1       0  5206.4     .07       0  5212.6      .1       0
  5325.8     .05       0  5554.3      .1       0
Bank Sta=5206.4,5212.6
XS Rating Curve= 0 ,0
Exp/Cntr=0.3,0.1

Type RM Length L Ch R = 1 ,4013    ,353,353,353
BEGIN DESCRIPTION:
Mapping XS 9b1d1173
END DESCRIPTION:
XS GIS Cut Line= 3
      2016726.31     13457779.79      2016368.26     13457975.09
      2016062.27     13458098.79
#Sta/Elev= 30
  4722.6  436.45  4764.4  436.77  4786.2  435.49  4829.9  435.95  4851.7  437.08
  4867.9  436.83  4883.6  435.08  4917.7  429.58  4940.5  428.75  4955.2  427.03
  4971.3  426.27    4977  424.01  4986.1   421.8  5005.8  421.25  5006.3  420.45
  5011.5  420.45    5012  421.25    5043  424.41  5058.7  425.33  5102.3  426.21
    5171  425.22  5187.9  424.01  5195.1  422.61  5219.2  424.27  5248.8  425.02
  5272.9   424.4  5278.3  425.27    5285  423.94  5317.3  425.57  5460.5  425.93
#Mann= 3 ,-1 , 0
  4722.6      .1       0  5005.8     .07       0    5012      .1       0
Bank Sta=5005.8,5012
XS Rating Curve= 0 ,0
Exp/Cntr=0.3,0.1

Type RM Length L Ch R = 1 ,3660    ,360,360,360
BEGIN DESCRIPTION:
Mapping XS 77d106ef
END DESCRIPTION:
XS GIS Cut Line= 2
      2016730.71      13457690.8      2015938.24      13457790.4
#Sta/Elev= 30
  4453.2  440.69  4525.7  435.52  4530.8  436.32  4549.7  435.62  4569.8  434.83
  4606.1  432.06  4611.2  432.31  4640.4   429.4  4680.7  427.16  4686.6  426.32
    4772  425.01  4791.5  423.63  4821.8     423  4831.9  424.12  4841.9  424.41
  4847.4  423.72  4852.4  424.29  4962.9  424.36    4973  423.47    4990  418.29
  4990.5  417.49  4995.7  417.49  4996.2  418.29  5003.2  421.44  5008.2  421.34
  5013.3  422.63  5033.4  424.14  5053.6  424.68  5092.6  424.57  5251.9  424.73
#Mann= 4 ,-1 , 0
  4453.2      .1       0    4990     .07       0  4996.2      .1       0
  5092.6     .05       0
Bank Sta=4990,4996.2
XS Rating Curve= 0 ,0
Exp/Cntr=0.3,0.1

Type RM Length L Ch R = 1 ,3300    ,245,245,245
BEGIN DESCRIPTION:
Mapping XS 36b5ec86
END DESCRIPTION:
XS GIS Cut Line= 3
      2016598.28     13457521.53      2016246.73     13457525.87
      2015942.89     13457703.83
#Sta/Elev= 30
  4549.7  430.74    4563  430.56    4613  427.71    4643  425.36    4683  424.96
    4733  424.78    4773  427.23    4803  427.06    4843  428.24    4873  427.15
  4899.6  423.33  4930.7  423.66  4946.4  423.45  4961.2  422.54  4973.7   420.5
  4983.6  419.98  4989.4  418.17  4992.9   417.6  4993.4   416.8  4998.6   416.8
  4999.1   417.6  5005.1  417.94  5010.9   420.2  5019.2  419.85  5032.4  422.09
  5063.7  423.63  5097.8  424.16    5181  424.08  5216.2  424.71  5253.4  424.18
#Mann= 4 ,-1 , 0
  4549.7      .1       0  4992.9     .07       0  4999.1      .1       0
  5097.8     .05       0
Bank Sta=4992.9,4999.1
XS Rating Curve= 0 ,0
Exp/Cntr=0.3,0.1

Type RM Length L Ch R = 1 ,3055    ,88,88,88
BEGIN DESCRIPTION:
Mapping XS 655cc8c6
END DESCRIPTION:
XS GIS Cut Line= 3
      2016539.69     13457330.56      2015873.46     13457497.66
      2015809.25       13457579.
#Sta/Elev= 30
  4634.7  424.36  4701.4  423.45  4742.6  424.32  4792.9  423.81  4798.1  422.03
  4814.8  423.38  4825.1  421.97  4834.1  422.81  4839.3  420.48  4875.3  421.93
  4880.4  418.83  4916.4  421.23  4921.6  418.21  4957.6  421.04  4962.8  417.97
  4998.8  418.73  5000.8  416.15  5001.3  415.35  5006.5  415.35    5007  416.15
    5021  416.96    5040  420.12  5045.1  418.28  5051.9  420.48  5135.1  421.24
  5196.3  420.08  5245.8  421.33  5321.6   421.3  5354.7  423.51  5425.2  423.92
#Mann= 4 ,-1 , 0
  4634.7      .1       0  5000.8     .07       0    5007      .1       0
  5135.1     .05       0
Bank Sta=5000.8,5007
XS Rating Curve= 0 ,0
Exp/Cntr=0.3,0.1

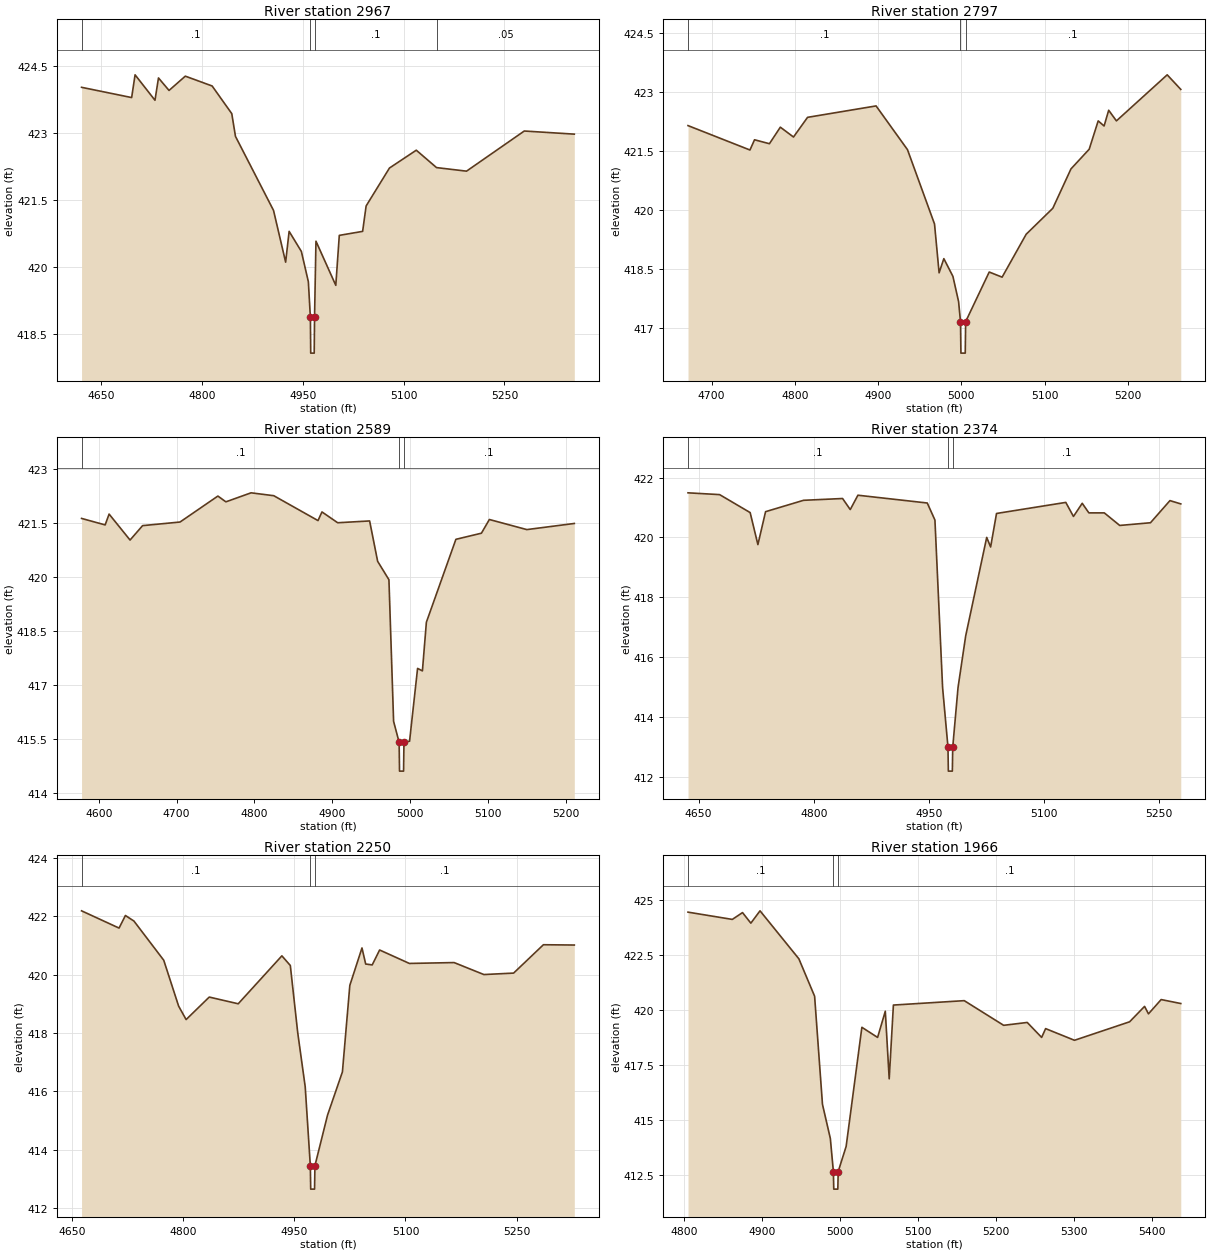
Type RM Length L Ch R = 1 ,2967    ,170,170,170
BEGIN DESCRIPTION:
Mapping XS f1aec438
END DESCRIPTION:
XS GIS Cut Line= 2
      2016500.65     13457250.26      2015793.17     13457441.24
#Sta/Elev= 30
  4621.1  424.02  4695.6  423.79  4700.7   424.3  4730.3  423.73  4735.5  424.23
  4751.2  423.95  4775.4  424.27  4815.3  424.05  4844.5  423.43    4850  422.92
  4906.6  421.26  4924.6   420.1  4929.8  420.79    4948  420.34  4958.4  419.66
  4961.4  418.86  4961.9  418.06  4967.1  418.06  4967.6  418.86  4969.7  420.57
  4999.2  419.58  5004.4   420.7  5039.1  420.79  5044.3  421.36    5079  422.21
  5118.9  422.61    5149  422.22  5193.6  422.14  5279.5  423.04  5353.9  422.97
#Mann= 4 ,-1 , 0
  4621.1      .1       0  4961.4     .07       0  4967.6      .1       0
    5149     .05       0
Bank Sta=4961.4,4967.6
XS Rating Curve= 0 ,0
Exp/Cntr=0.3,0.1

Type RM Length L Ch R = 1 ,2797    ,208,208,208
BEGIN DESCRIPTION:
Mapping XS 7e79a3eb
END DESCRIPTION:
XS GIS Cut Line= 2
      2016296.67     13457139.57       2015754.1     13457376.14
#Sta/Elev= 30
  4671.6  422.14    4746  421.52  4751.5  421.78  4769.4  421.68  4782.5   422.1
  4798.3  421.85  4815.2  422.35  4897.5  422.64  4935.2  421.53  4967.7  419.64
  4973.2   418.4  4978.9  418.76  4989.8  418.31  4996.6  417.67  4998.9  417.16
  4999.4  416.36  5004.6  416.36  5005.1  417.16  5033.4  418.42  5048.9  418.29
  5077.8  419.38  5109.8  420.04  5131.6  421.04  5153.5  421.54  5164.3  422.26
  5171.4  422.13  5176.9  422.53  5186.2  422.26  5247.2  423.43  5263.5  423.06
#Mann= 3 ,-1 , 0
  4671.6      .1       0  4998.9     .07       0  5005.1      .1       0
Bank Sta=4998.9,5005.1
XS Rating Curve= 0 ,0
Exp/Cntr=0.3,0.1

Type RM Length L Ch R = 1 ,2589    ,215,215,215
BEGIN DESCRIPTION:
Mapping XS 1cba5471
END DESCRIPTION:
XS GIS Cut Line= 2
      2016285.75     13457022.41       2015668.7     13457163.14
#Sta/Elev= 30
  4577.9  421.62  4608.2  421.44  4613.3  421.74  4640.2  421.02  4656.3  421.42
  4704.4  421.52    4753  422.24  4763.3  422.08  4795.6  422.33  4824.8  422.25
  4881.6  421.56  4886.7   421.8  4906.9   421.5  4947.9  421.55  4958.2  420.43
  4972.7  419.92  4978.7  415.99  4985.8  415.41  4986.3  414.61  4991.5  414.61
    4992  415.41  4999.2  415.44  5009.5  417.46  5015.7  417.39  5020.8  418.74
  5058.7  421.04  5091.5  421.21  5101.7  421.59  5149.8  421.31  5210.8  421.48
#Mann= 3 ,-1 , 0
  4577.9      .1       0  4985.8     .07       0    4992      .1       0
Bank Sta=4985.8,4992
XS Rating Curve= 0 ,0
Exp/Cntr=0.3,0.1

Type RM Length L Ch R = 1 ,2374    ,124,124,124
BEGIN DESCRIPTION:
Mapping XS 6e4ccfc4
END DESCRIPTION:
XS GIS Cut Line= 2
      2016285.74     13456926.92      2015645.64     13456981.16
#Sta/Elev= 30
  4636.1  421.49  4677.3  421.43  4717.1  420.83  4727.2  419.76  4737.2  420.86
  4786.7  421.24  4837.6   421.3  4847.6  420.93  4857.6  421.41    4948  421.15
    4958  420.58    4968  414.98    4975  412.99  4975.5  412.19  4980.7  412.19
  4981.2  412.99  4988.1  414.98  4998.1  416.71  5025.5     420  5030.6  419.68
  5038.3   420.8  5128.6  421.17  5138.6   420.7    5150  421.14  5158.7  420.82
  5178.8  420.82  5198.9   420.4    5239  420.49  5264.4  421.23  5278.5  421.12
#Mann= 3 ,-1 , 0
  4636.1      .1       0    4975     .07       0  4981.2      .1       0
Bank Sta=4975,4981.2
XS Rating Curve= 0 ,0
Exp/Cntr=0.3,0.1

Type RM Length L Ch R = 1 ,2250    ,284,284,284
BEGIN DESCRIPTION:
Mapping XS f544081a
END DESCRIPTION:
XS GIS Cut Line= 2
      2016255.42     13456814.07      2015593.51       13456877.
#Sta/Elev= 30
  4662.9  422.18  4713.5  421.59  4722.1  422.02  4733.6  421.83  4773.8  420.49
  4793.9  418.92    4804  418.46  4835.2  419.23  4874.3     419  4933.2  420.64
  4944.6  420.31  4954.6  418.01  4964.7  416.16  4971.6  413.46  4972.1  412.66
  4977.3  412.66  4977.8  413.46  4994.8  415.19  5014.9  416.67  5024.9  419.63
  5041.3  420.91  5046.3  420.36  5055.1  420.33  5065.1  420.84  5105.3  420.38
  5165.6  420.41  5205.8     420  5245.9  420.05  5286.1  421.02  5327.8  421.01
#Mann= 3 ,-1 , 0
  4662.9      .1       0  4971.6     .07       0  4977.8      .1       0
Bank Sta=4971.6,4977.8
XS Rating Curve= 0 ,0
Exp/Cntr=0.3,0.1

Type RM Length L Ch R = 1 ,1966    ,104,104,104
BEGIN DESCRIPTION:
Mapping XS da8885b0
END DESCRIPTION:
XS GIS Cut Line= 3
      2016220.64     13456670.82      2016127.37     13456636.11
      2015600.07      13456716.4
#Sta/Elev= 30
  4804.6  424.43  4861.5   424.1  4874.6  424.41  4885.3  423.93  4897.1  424.49
    4947  422.31  4967.2  420.61  4977.3   415.7  4987.4  414.15  4991.3  412.65
  4991.8  411.85    4997  411.85  4997.5  412.65  5007.7  413.79  5027.9   419.2
  5048.1  418.74    5058  419.93    5063  416.86  5068.4  420.21  5159.4  420.41
    5210  419.29  5240.3  419.42  5258.8  418.74  5263.9  419.14    5301  418.61
  5371.8  419.45    5391  420.15    5396  419.81  5412.3  420.46  5437.5  420.28
#Mann= 3 ,-1 , 0
  4804.6      .1       0  4991.3     .07       0  4997.5      .1       0
Bank Sta=4991.3,4997.5
XS Rating Curve= 0 ,0
Exp/Cntr=0.3,0.1

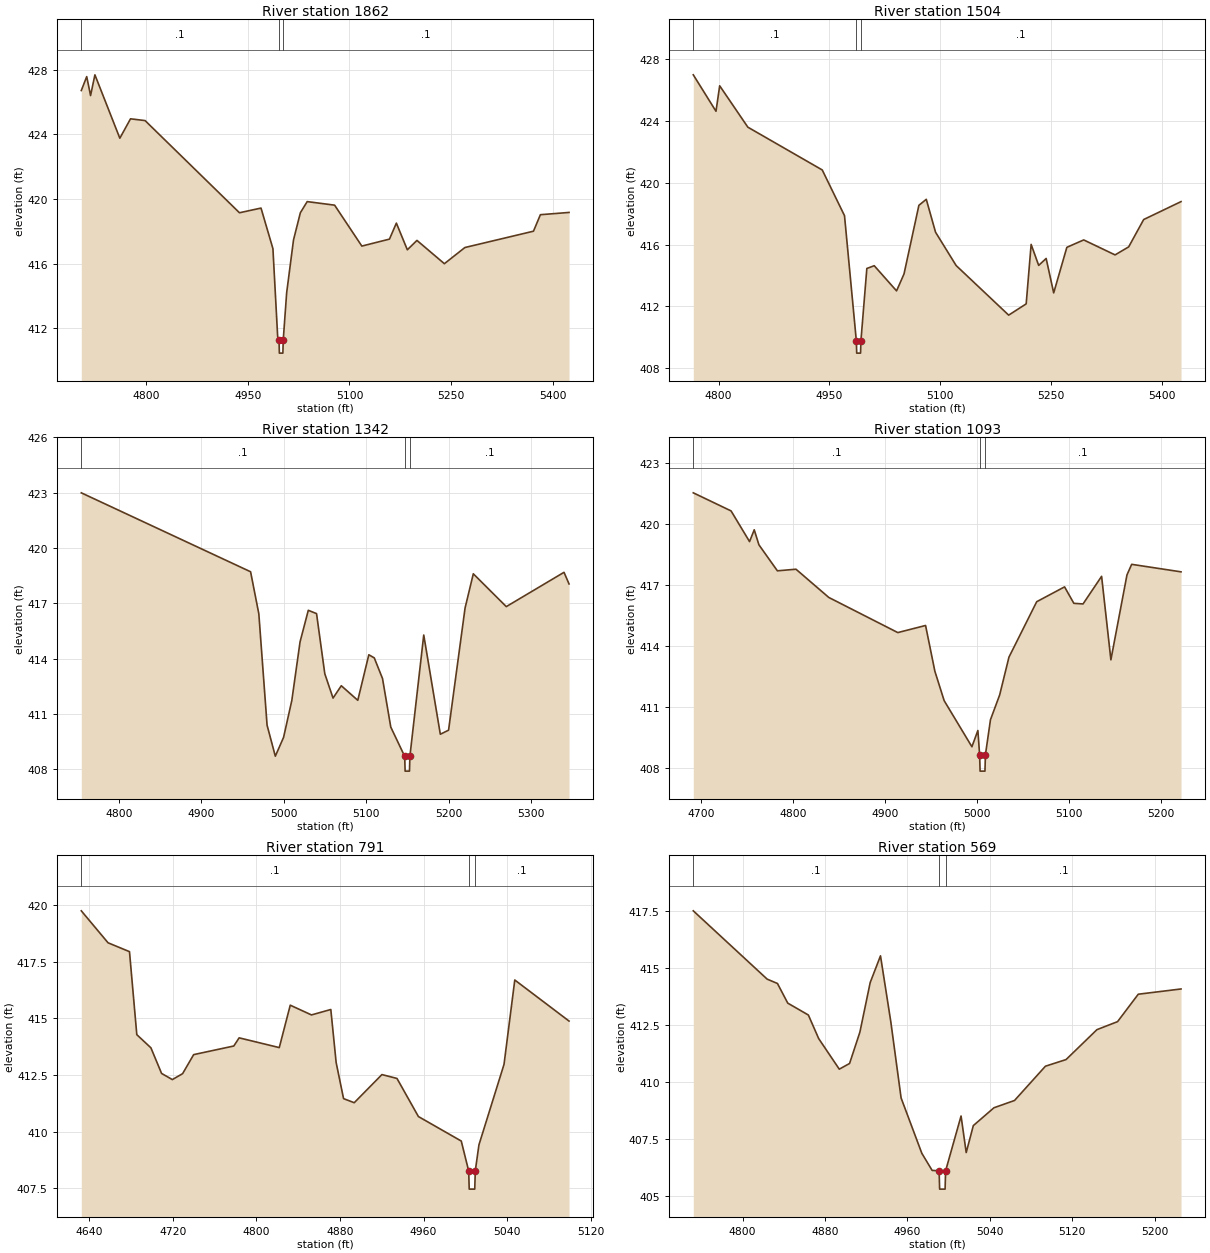
Type RM Length L Ch R = 1 ,1862    ,358,358,358
BEGIN DESCRIPTION:
Mapping XS 38374b1a
END DESCRIPTION:
XS GIS Cut Line= 3
      2016242.41     13456423.43      2016012.35     13456555.82
      2015563.15     13456627.43
#Sta/Elev= 30
    4704  426.71    4712  427.57  4717.7   426.4  4724.1  427.68  4760.9  423.76
  4776.7  424.96  4798.2  424.85  4937.6  419.15  4969.4  419.44    4987  416.93
    4994  411.49    4996  411.27  4996.5  410.47  5001.7  410.47  5002.2  411.27
  5007.3  414.21  5017.4  417.47  5027.5  419.15  5037.6  419.84  5078.1  419.62
  5118.3  417.09  5159.1  417.52  5169.3  418.51  5185.5  416.86  5199.7  417.44
  5240.2     416  5270.5     417  5371.8  418.01    5382  419.03  5424.3  419.17
#Mann= 3 ,-1 , 0
    4704      .1       0    4996     .07       0  5002.2      .1       0
Bank Sta=4996,5002.2
XS Rating Curve= 0 ,0
Exp/Cntr=0.3,0.1

Type RM Length L Ch R = 1 ,1504    ,162,162,162
BEGIN DESCRIPTION:
Mapping XS 5ddcf781
END DESCRIPTION:
XS GIS Cut Line= 3
      2016268.44     13456336.63      2015932.06     13456371.36
      2015615.24     13456425.61
#Sta/Elev= 30
  4765.8  426.99  4796.5  424.63  4801.5  426.28  4839.6   423.6  4940.2  420.83
  4970.3  417.87  4986.3  409.77  4986.8  408.97    4992  408.97  4992.5  409.77
  5000.5  414.45  5010.5  414.63  5040.7     413  5050.8   414.1  5070.9  418.54
  5080.9  418.93  5093.4   416.8  5121.3  414.64  5192.3  411.43    5216  412.16
  5222.7  416.01  5232.9  414.65    5243   415.1  5253.2  412.87    5271  415.82
  5293.8   416.3  5336.2  415.33  5354.6  415.85  5374.9  417.62  5425.4  418.78
#Mann= 3 ,-1 , 0
  4765.8      .1       0  4986.3     .07       0  4992.5      .1       0
Bank Sta=4986.3,4992.5
XS Rating Curve= 0 ,0
Exp/Cntr=0.3,0.1

Type RM Length L Ch R = 1 ,1342    ,249,249,249
BEGIN DESCRIPTION:
Mapping XS 9ac6f778
END DESCRIPTION:
XS GIS Cut Line= 2
      2016240.17     13456249.83      2015648.92     13456267.16
#Sta/Elev= 30
  4754.3  422.99  4959.6  418.71  4969.6  416.43  4979.6  410.39  4989.6  408.71
  4999.6  409.73  5009.6  411.73  5019.6  414.91  5029.6  416.62  5039.6  416.44
  5049.6  413.18  5059.6  411.86  5069.6  412.53  5089.6  411.74    5103  414.21
  5109.6  414.04  5119.6  412.92  5129.6  410.29  5146.5   408.7    5147   407.9
  5152.3   407.9  5152.8   408.7  5169.6  415.28  5189.7   409.9  5199.7  410.12
  5219.7  416.74  5229.7   418.6  5269.7  416.82  5339.7  418.68  5345.8  418.05
#Mann= 3 ,-1 , 0
  4754.3      .1       0  5146.5     .07       0  5152.8      .1       0
Bank Sta=5146.5,5152.8
XS Rating Curve= 0 ,0
Exp/Cntr=0.3,0.1

Type RM Length L Ch R = 1 ,1093    ,302,302,302
BEGIN DESCRIPTION:
Mapping XS 64e2a459
END DESCRIPTION:
XS GIS Cut Line= 2
      2016235.83     13456071.88      2015709.23      13456136.9
#Sta/Elev= 30
  4691.3  421.55  4732.4  420.66  4752.5  419.15  4757.6  419.73  4762.7  418.99
  4782.8  417.71    4803  417.79  4838.7   416.4  4913.8  414.67    4944  415.02
  4954.1  412.77  4964.2  411.32  4994.4  409.05  5000.9  409.85  5002.8  408.65
  5003.3  407.85  5008.6  407.85  5009.1  408.65  5014.6  410.38  5024.6   411.6
  5034.7  413.46  5064.9  416.19  5095.2  416.92  5105.3  416.11  5115.3  416.08
  5135.5  417.44  5145.6  413.33  5163.1  417.51  5168.2  418.03  5221.9  417.66
#Mann= 3 ,-1 , 0
  4691.3      .1       0  5002.8     .07       0  5009.1      .1       0
Bank Sta=5002.8,5009.1
XS Rating Curve= 0 ,0
Exp/Cntr=0.3,0.1

Type RM Length L Ch R = 1 ,791     ,222,222,222
BEGIN DESCRIPTION:
Mapping XS 49d31b60
END DESCRIPTION:
XS GIS Cut Line= 2
      2016110.05     13455898.26      2015654.26      13455998.1
#Sta/Elev= 30
  4632.6  419.74  4658.2  418.33  4678.7  417.94  4685.7  414.28  4699.2   413.7
  4709.4  412.57  4719.7   412.3  4729.5  412.56  4740.1   413.4  4778.5  413.78
  4783.6  414.14    4822  413.71  4832.5  415.58  4852.8  415.15  4871.3  415.39
  4876.4  413.05  4883.5  411.46  4893.7  411.28  4920.2  412.52  4934.6  412.35
  4955.1  410.67  4996.1  409.59  5003.2  408.27  5003.7  407.47    5009  407.47
  5009.5  408.27    5013  409.42    5037  412.97  5047.3  416.69  5099.2  414.88
#Mann= 3 ,-1 , 0
  4632.6      .1       0  5003.2     .07       0  5009.5      .1       0
Bank Sta=5003.2,5009.5
XS Rating Curve= 0 ,0
Exp/Cntr=0.3,0.1

Type RM Length L Ch R = 1 ,569     ,186,186,186
BEGIN DESCRIPTION:
Mapping XS 813e4f82
END DESCRIPTION:
XS GIS Cut Line= 2
      2016066.64     13455798.44      2015593.48     13455783.25
#Sta/Elev= 30
  4752.2  417.49  4823.9   414.5  4833.9  414.31  4843.9  413.45  4863.9  412.93
  4873.9   411.9  4893.9  410.56  4903.9  410.81  4913.9  412.18  4923.9  414.35
  4933.9  415.52  4943.9  412.64  4953.9   409.3    4974  406.88    4984  406.13
  4990.8  406.11  4991.3  405.31  4996.6  405.31  4997.1  406.11  5012.1  408.51
  5017.1  406.91    5024  408.09    5044  408.87    5064  409.19    5094  410.69
    5114  410.98    5144  412.29    5164  412.64  5184.1  413.84  5225.6  414.07
#Mann= 3 ,-1 , 0
  4752.2      .1       0  4990.8     .07       0  4997.1      .1       0
Bank Sta=4990.8,4997.1
XS Rating Curve= 0 ,0
Exp/Cntr=0.3,0.1

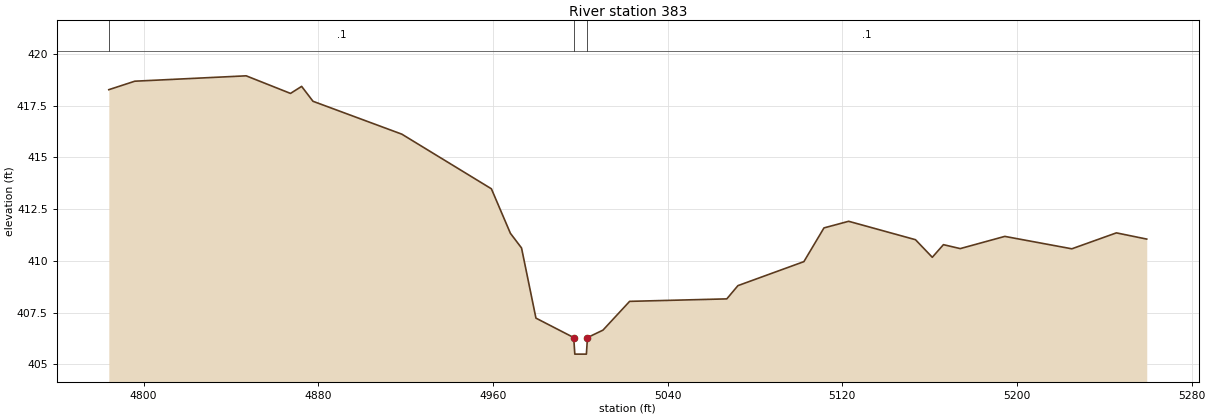
Type RM Length L Ch R = 1 ,383     ,0,0,0
BEGIN DESCRIPTION:
UNT 031 in RCW 1.0
END DESCRIPTION:
XS GIS Cut Line= 3
       2016006.7      13455602.7      2015867.82     13455630.47
      2015541.45     13455699.91
#Sta/Elev= 30
  4784.1  418.27    4796  418.68    4847  418.94  4867.3  418.09  4872.4  418.43
  4877.6  417.71  4918.3  416.12  4959.3  413.48    4968  411.33  4973.1  410.62
  4979.7  407.23    4997  406.29  4997.5  405.49  5002.8  405.49  5003.3  406.29
  5010.4  406.65  5022.6  408.04  5067.1  408.16  5072.2   408.8  5102.4  409.96
  5111.6  411.59  5122.9  411.91  5153.5  411.02  5161.2  410.17  5166.3  410.78
    5174  410.59  5194.4  411.18  5225.1  410.58  5245.5  411.35  5259.4  411.05
#Mann= 3 ,-1 , 0
  4784.1      .1       0    4997     .07       0  5003.3      .1       0
Bank Sta=4997,5003.3
XS Rating Curve= 0 ,0
Exp/Cntr=0.3,0.1
LCMann Table=0

Chan Stop Cuts=-1
Use User Specified Reach Order=0
Composite Channel Slope=5