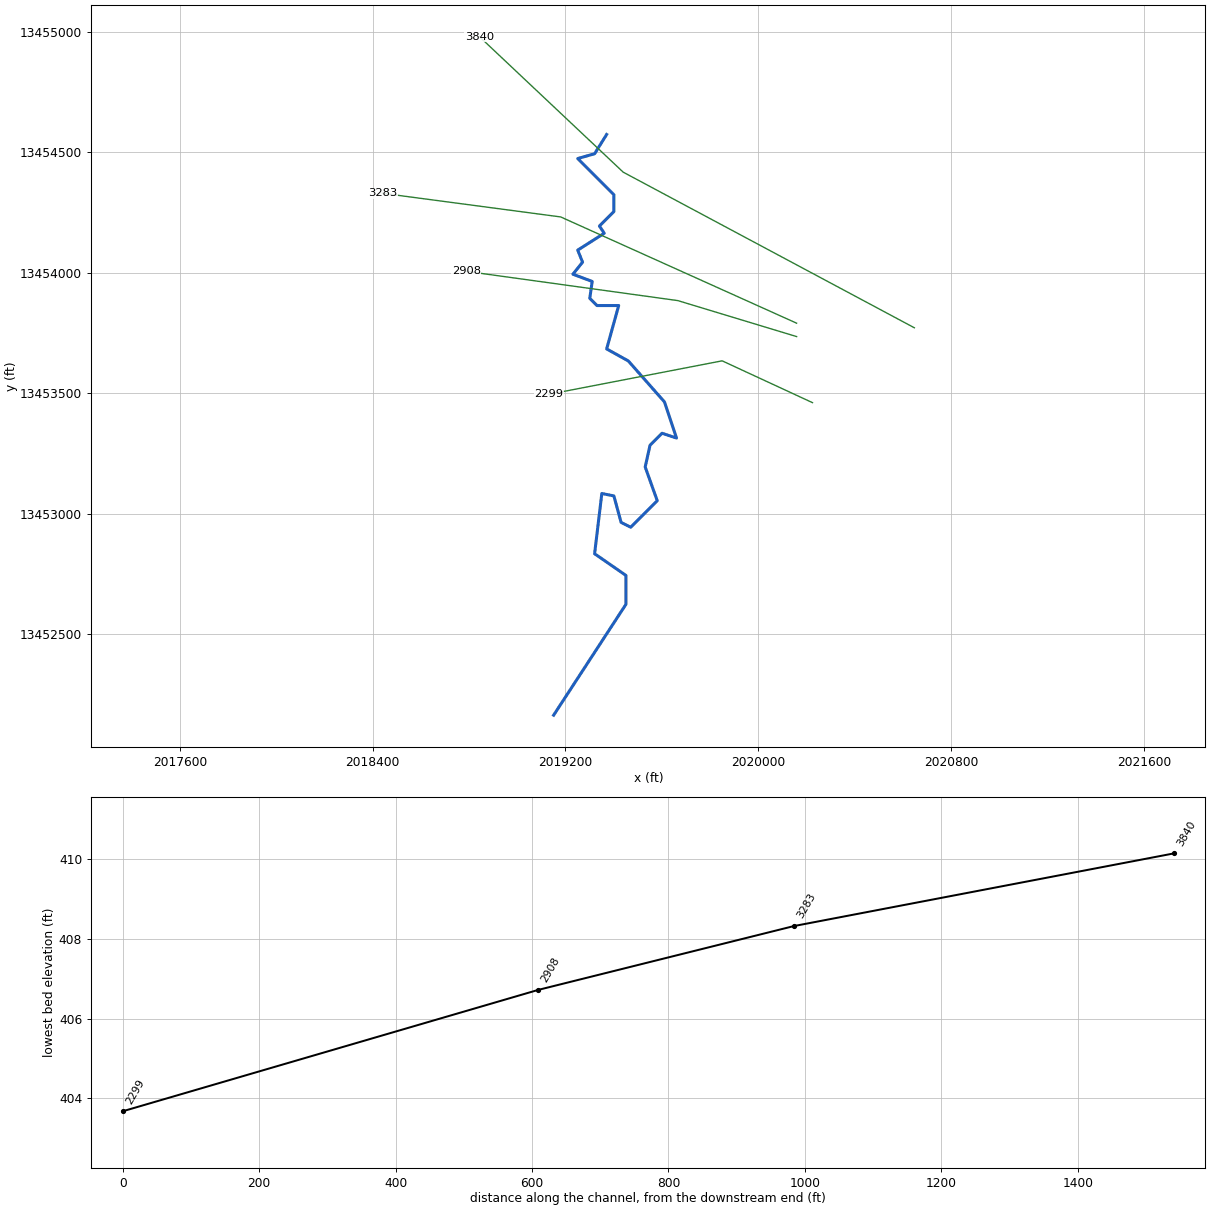
--- UNT 032 in RCW.prj (project) ---

Proj Title=UNT 032 in RCW Base Level Engineering
Current Plan=p01
Default Exp/Contr=0.3,0.1
English Units
Geom File=g01
Flow File=f01
Plan File=p01
Y Axis Title=Elevation
X Axis Title(PF)=Main Channel Distance
X Axis Title(XS)=Station
BEGIN DESCRIPTION:
UNT 032 in RCW
END DESCRIPTION:
DSS Export Rating Curves= 0
DSS Export Rating Curve Sorted= 0
DSS Export Volume Flow Curves= 0
DXF OffsetX= 0
DXF OffsetY= 0
DXF ScaleX= 1
DXF ScaleY= 10

--- UNT 032 in RCW.p01 (plan) ---

Plan Title=Multiple Run
Short Identifier=Multiple
Geom File=g01
Flow File=f01
Subcritical Flow
K Sum by GR= 0
Std Step Tol= 0.01
Critical Tol= 0.01
Num of Std Step Trials= 20
Max Error Tol= 0.3
Flow Tol Ratio= 0.001
Split Flow NTrial= 30
Split Flow Tol= 0.02
Split Flow Ratio= 0.02
Log Output Level= 0
Friction Slope Method= 1
Unsteady Friction Slope Method= 2
Unsteady Bridges Friction Slope Method= 1
Parabolic Critical Depth
Global Vel Dist=  1 , 1 , 1
Global Log Level= 0
CheckData=True
Encroach Param= -1, 0, 0, 0
BEGIN DESCRIPTION:
Multiple Run
END DESCRIPTION:

--- UNT 032 in RCW.f01 (steady flow) ---

Flow Title=Multiple
Number of Profiles=7
Profile Names=10-year,25-year,50-year,1pct_min,100-year,1pct_plu,500-year
River Rch & RM= UNT 032 in RCW,Reach-1,3840
     147     197     238     144     287     572     421
River Rch & RM= UNT 032 in RCW,Reach-1,3283
     211     290     355     217     433     863     652
Boundary for River Rch & Prof#=UNT 032 in RCW,Reach-1,1
Up Type=0
Dn Type=3
Dn Slope=0.005
Boundary for River Rch & Prof#=UNT 032 in RCW,Reach-1,2
Up Type=0
Dn Type=3
Dn Slope=0.005
Boundary for River Rch & Prof#=UNT 032 in RCW,Reach-1,3
Up Type=0
Dn Type=3
Dn Slope=0.005
Boundary for River Rch & Prof#=UNT 032 in RCW,Reach-1,4
Up Type=0
Dn Type=3
Dn Slope=0.005
Boundary for River Rch & Prof#=UNT 032 in RCW,Reach-1,5
Up Type=0
Dn Type=3
Dn Slope=0.005
Boundary for River Rch & Prof#=UNT 032 in RCW,Reach-1,6
Up Type=0
Dn Type=3
Dn Slope=0.005
Boundary for River Rch & Prof#=UNT 032 in RCW,Reach-1,7
Up Type=0
Dn Type=3
Dn Slope=0.005

--- UNT 032 in RCW.g01 (geometry) ---

Geom Title=Existing Conditions
Program Version=5.05

River Reach=UNT 032 in RCW  ,Reach-1
Reach XY= 30
       2019370.8     13454574.54       2019320.8     13454494.54
       2019250.8     13454474.54       2019400.8     13454324.54
       2019400.8     13454254.54       2019340.8     13454194.54
       2019360.8     13454164.54       2019250.8     13454094.54
       2019270.8     13454044.54       2019230.8     13453994.54
       2019310.8     13453964.54       2019300.8     13453894.54
       2019330.8     13453864.54       2019420.8     13453864.54
       2019370.8     13453684.54       2019460.8     13453634.54
       2019610.8     13453464.54       2019660.8     13453314.54
       2019600.8     13453334.54       2019550.8     13453284.54
       2019530.8     13453194.54       2019580.8     13453054.54
       2019470.8     13452944.54       2019430.8     13452964.54
       2019400.8     13453074.54       2019350.8     13453084.54
       2019320.8     13452834.54       2019450.8     13452744.54
       2019450.8     13452624.54       2019150.8     13452164.54

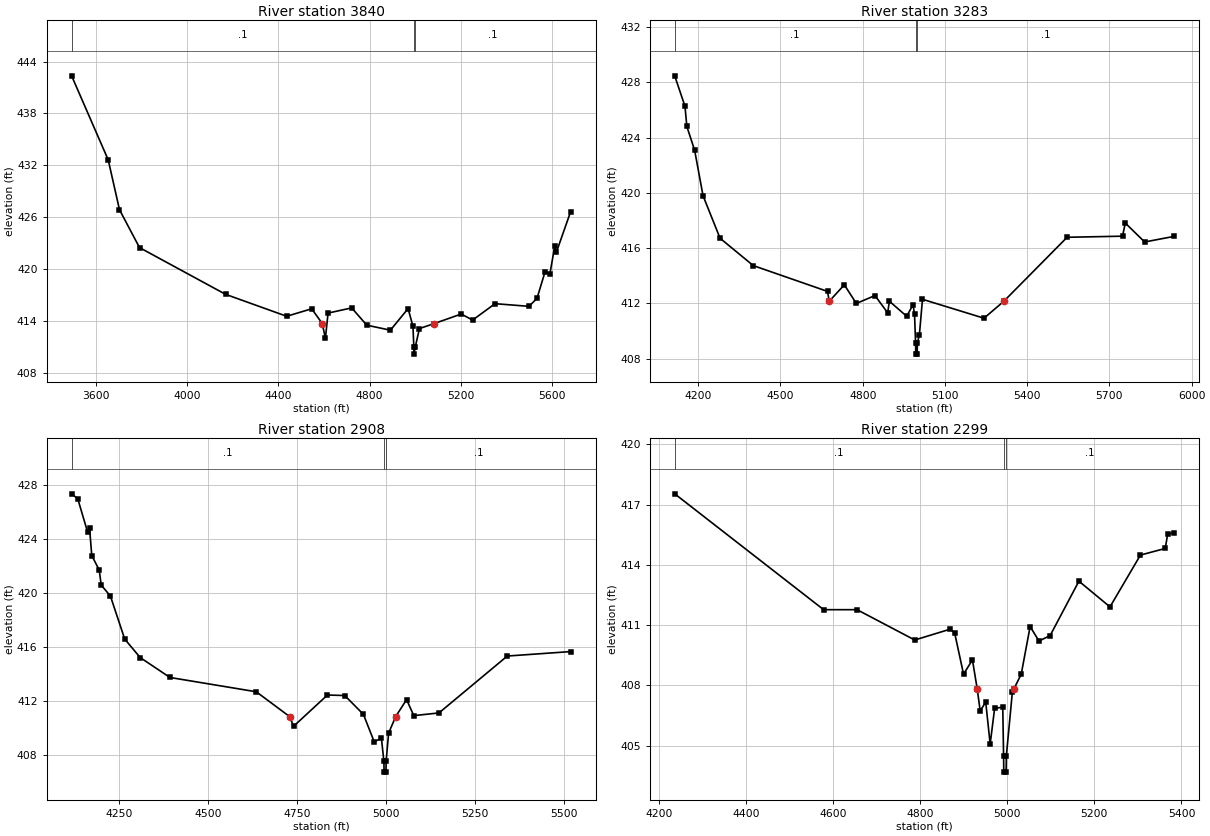
Type RM Length L Ch R = 1 ,3840    ,557,557,557
BEGIN DESCRIPTION:
UNT 032 in RCW 4.0
END DESCRIPTION:
XS GIS Cut Line= 3
      2020647.89     13453772.25      2019439.55     13454418.08
      2018842.31     13454980.97
#Sta/Elev= 30
  3491.8  442.35  3652.5  432.62    3702  426.85  3789.9  422.47  4167.8  417.06
  4436.1  414.52  4545.8  415.39 4592.14413.6823    4606  411.97  4617.6  414.89
  4721.4  415.49  4787.7  413.49  4891.3  412.91    4969  415.41  4990.4  413.36
  4994.3  410.94  4994.8  410.14  5000.3  410.94  5018.8   413.1 5084.22413.6837
  5202.4  414.78  5252.2  414.08  5350.9  415.98  5499.8  415.67    5535   416.6
  5570.2  419.66  5591.6  419.42  5612.7  422.62    5620  421.93  5682.6  426.63
#Mann= 3 ,-1 , 0
  3491.8      .1       0  4994.3     .07       0  5000.3      .1       0
Bank Sta=4592.14,5084.22
XS Rating Curve= 0 ,0
Exp/Cntr=0.3,0.1

Type RM Length L Ch R = 1 ,3283    ,375,375,375
BEGIN DESCRIPTION:
Mapping XS ce8195b6
END DESCRIPTION:
XS GIS Cut Line= 3
      2020159.16     13453791.35        2019180.     13454232.32
      2018439.87      13454330.6
#Sta/Elev= 30
  4114.1  428.47  4151.6  426.26  4158.3  424.81  4186.9  423.07  4217.4  419.79
  4279.5  416.71  4400.7  414.73  4671.7  412.86 4677.66 412.141  4732.8  413.34
  4776.7  411.99  4844.7  412.56    4891  411.31  4897.3  412.15  4960.4  411.06
  4983.5   411.9    4989  411.21  4992.9  409.12  4993.4  408.32  4998.7  408.32
  4999.2  409.12  5006.7  409.71    5018  412.29  5242.4  410.92 5314.49412.1413
  5545.6  416.78  5747.8  416.86  5757.9  417.81  5828.5  416.44  5934.6  416.84
#Mann= 3 ,-1 , 0
  4114.1      .1       0  4992.9     .07       0  4999.2      .1       0
Bank Sta=4677.66,5314.49
XS Rating Curve= 0 ,0
Exp/Cntr=0.3,0.1

Type RM Length L Ch R = 1 ,2908    ,609,609,609
BEGIN DESCRIPTION:
UNT 032 in RCW 3.0
END DESCRIPTION:
XS GIS Cut Line= 3
      2020159.18     13453735.79      2019666.11      13453885.1
      2018788.85     13454006.46
#Sta/Elev= 30
    4117  427.36  4134.3  426.99    4162  424.51  4167.2  424.86  4173.6  422.78
  4194.5  421.71  4200.1  420.59  4225.9  419.78    4266  416.59  4309.4  415.22
    4393  413.74  4635.3  412.68 4728.99410.8389  4740.1  410.12  4835.2  412.44
  4883.8   412.4  4936.2     411  4966.4  408.97  4986.6  409.24  4993.6  407.52
  4994.1  406.72  4999.4  406.72  4999.9  407.52  5006.8  409.61 5026.73 410.839
  5057.3   412.1  5077.5  410.91  5148.2  411.11    5340  415.33  5517.8  415.66
#Mann= 3 ,-1 , 0
    4117      .1       0  4993.6     .07       0  4999.9      .1       0
Bank Sta=4728.99,5026.73
XS Rating Curve= 0 ,0
Exp/Cntr=0.3,0.1

Type RM Length L Ch R = 1 ,2299    ,0,0,0
BEGIN DESCRIPTION:
Mapping XS 7fab9104
END DESCRIPTION:
XS GIS Cut Line= 3
      2020225.13     13453461.49      2019850.14      13453635.1
      2019131.36      13453496.2
#Sta/Elev= 30
  4236.9  417.54  4578.7  411.77  4655.4  411.77  4787.8  410.26  4869.2   410.8
  4879.4  410.61  4899.8  408.56  4920.2  409.27 4931.15407.8296    4938  406.73
  4950.7  407.17  4960.9  405.08  4971.1  406.85  4989.8  406.92  4991.7  404.48
  4992.2  403.68  4997.5  403.68    4998  404.48  5011.8  407.66 5015.55407.8291
  5032.2  408.56  5052.6  410.93  5072.9  410.21  5098.5  410.48  5164.6  413.19
  5235.9  411.91  5305.8  414.49  5362.7  414.82  5368.3  415.53  5382.2   415.6
#Mann= 3 ,-1 , 0
  4236.9      .1       0  4991.7     .07       0    4998      .1       0
Bank Sta=4931.15,5015.55
XS Rating Curve= 0 ,0
Exp/Cntr=0.3,0.1
LCMann Table=0

Chan Stop Cuts=-1
Use User Specified Reach Order=0
Composite Channel Slope=5