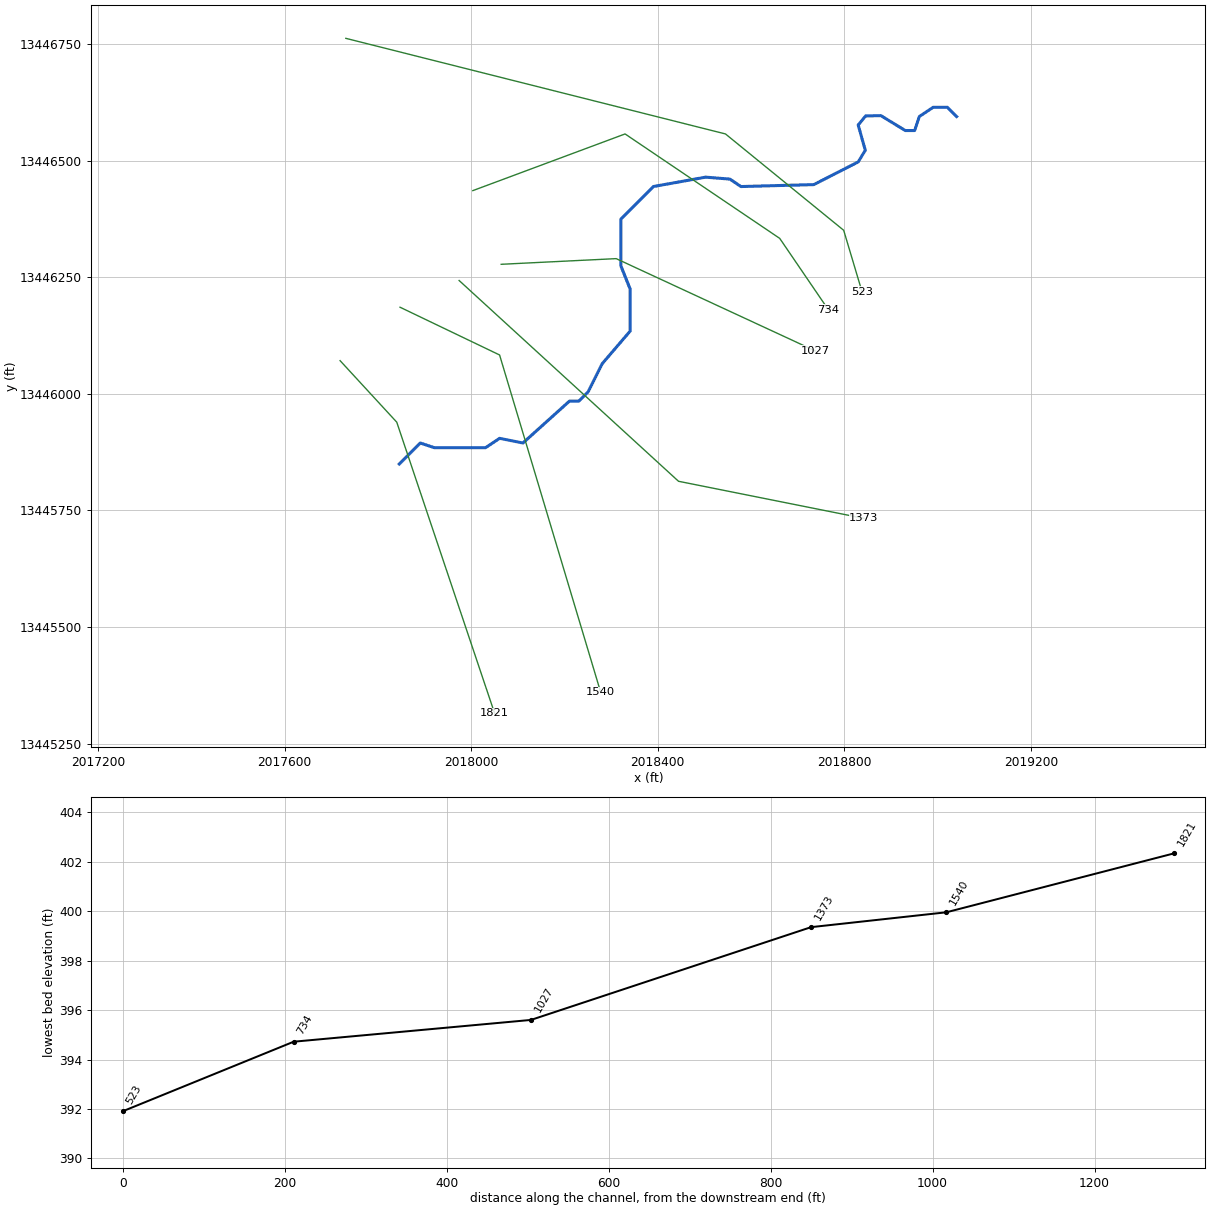
--- UNT 034 in RCW.prj (project) ---

Proj Title=UNT 034 in RCW Base Level Engineering
Current Plan=p01
Default Exp/Contr=0.3,0.1
English Units
Geom File=g01
Flow File=f01
Plan File=p01
BEGIN DESCRIPTION:
UNT 034 in RCW
END DESCRIPTION:

--- UNT 034 in RCW.p01 (plan) ---

Plan Title=Multiple Run
Short Identifier=Multiple
Geom File=g01
Flow File=f01
Subcritical Flow
K Sum by GR= 0
Std Step Tol= 0.01
Critical Tol= 0.01
Num of Std Step Trials= 20
Max Error Tol= 0.3
Flow Tol Ratio= 0.001
Split Flow NTrial= 30
Split Flow Tol= 0.02
Split Flow Ratio= 0.02
Log Output Level= 0
Friction Slope Method= 1
Unsteady Friction Slope Method= 2
Unsteady Bridges Friction Slope Method= 1
Parabolic Critical Depth
Global Vel Dist=  1 , 1 , 1
Global Log Level= 0
CheckData=True
Encroach Param= -1, 0, 0, 0
BEGIN DESCRIPTION:
Multiple Run
END DESCRIPTION:

--- UNT 034 in RCW.f01 (steady flow) ---

Flow Title=Multiple
Number of Profiles=7
Profile Names=10-year,25-year,50-year,1pct_min,100-year,1pct_plu,500-year
River Rch & RM= UNT 034 in RCW,Reach-1,1821
     155     210     254     153     306     610     451
Boundary for River Rch & Prof#=UNT 034 in RCW,Reach-1,1
Up Type=0
Dn Type=3
Dn Slope=0.005
Boundary for River Rch & Prof#=UNT 034 in RCW,Reach-1,2
Up Type=0
Dn Type=3
Dn Slope=0.005
Boundary for River Rch & Prof#=UNT 034 in RCW,Reach-1,3
Up Type=0
Dn Type=3
Dn Slope=0.005
Boundary for River Rch & Prof#=UNT 034 in RCW,Reach-1,4
Up Type=0
Dn Type=3
Dn Slope=0.005
Boundary for River Rch & Prof#=UNT 034 in RCW,Reach-1,5
Up Type=0
Dn Type=3
Dn Slope=0.005
Boundary for River Rch & Prof#=UNT 034 in RCW,Reach-1,6
Up Type=0
Dn Type=3
Dn Slope=0.005
Boundary for River Rch & Prof#=UNT 034 in RCW,Reach-1,7
Up Type=0
Dn Type=3
Dn Slope=0.005

--- UNT 034 in RCW.g01 (geometry) ---

Geom Title=Existing Conditions

River Reach=UNT 034 in RCW,Reach-1
Reach XY= 30
      2017845.80     13445849.54      2017890.80     13445894.54
      2017920.80     13445884.54      2018030.80     13445884.54
      2018060.80     13445904.54      2018110.80     13445894.54
      2018210.80     13445984.54      2018230.80     13445984.54
      2018250.80     13446004.54      2018280.80     13446064.54
      2018340.80     13446134.54      2018340.80     13446224.54
      2018320.80     13446274.54      2018320.80     13446374.54
      2018390.80     13446444.54      2018502.64     13446464.59
      2018554.73     13446460.42      2018578.34     13446444.45
      2018734.59     13446448.62      2018829.73     13446497.23
      2018845.00     13446522.23      2018829.73     13446576.40
      2018845.70     13446595.84      2018878.34     13446596.54
      2018930.80     13446564.54      2018950.80     13446564.54
      2018960.80     13446594.54      2018990.80     13446614.54
      2019020.80     13446614.54      2019040.80     13446594.54

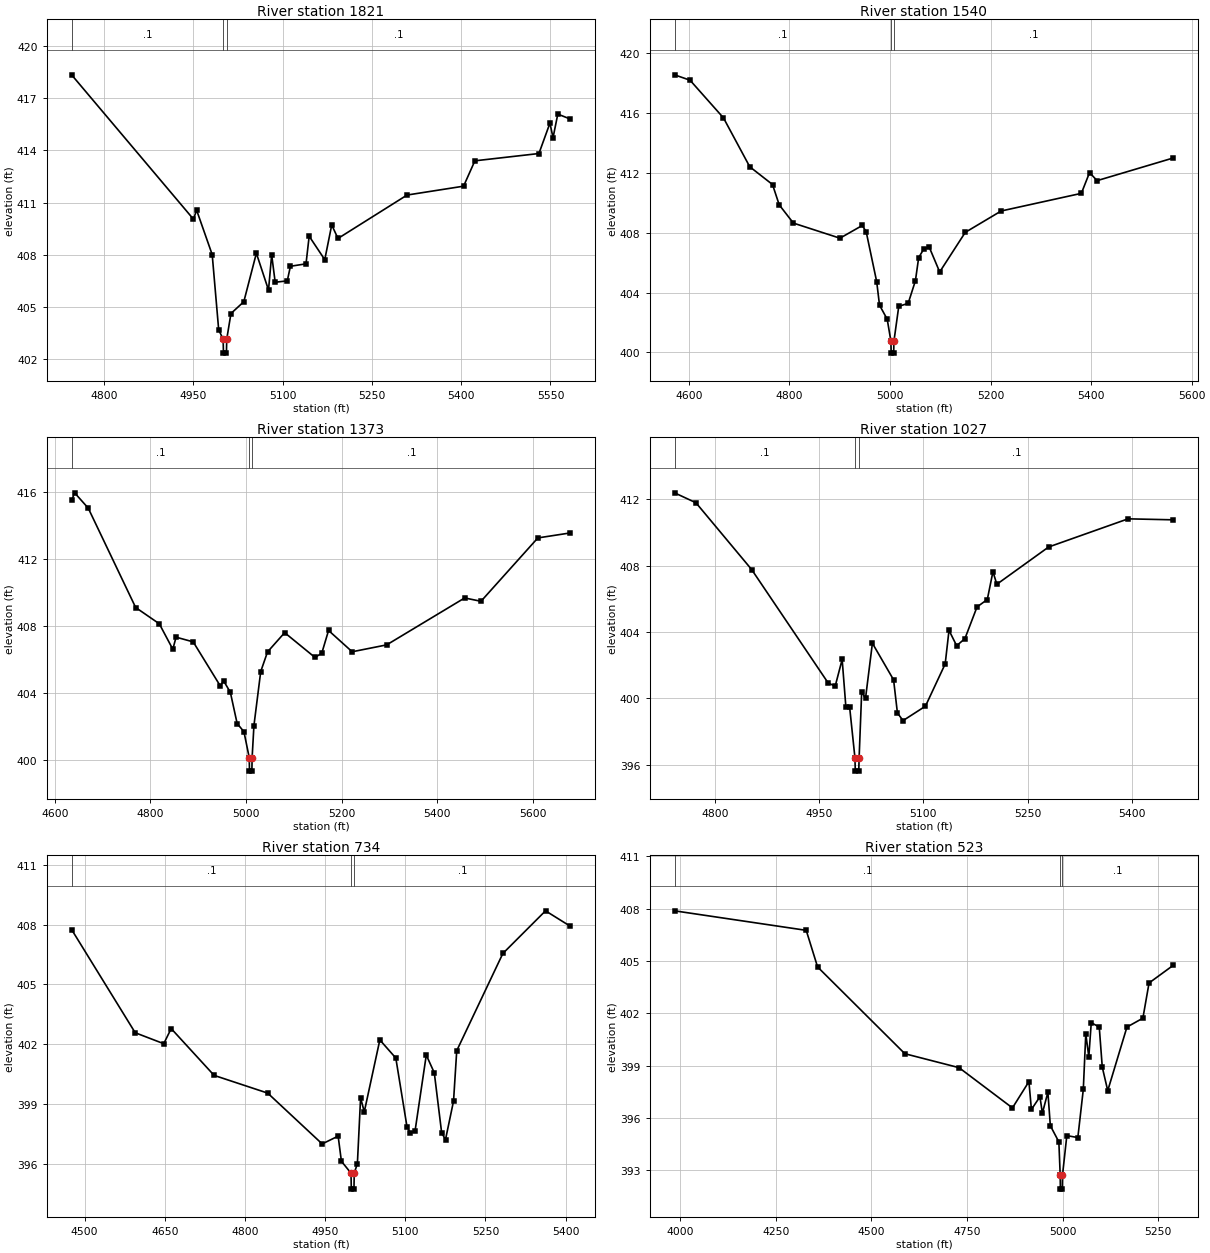
Type RM Length L Ch R = 1,1821,281,281,281
BEGIN DESCRIPTION:
UNT 034 in RCW 2.0
END DESCRIPTION:
XS GIS Cut Line= 3
      2017718.79     13446071.13      2017840.30     13445939.21
      2018050.18     13445314.79
#Sta/Elev= 30
  4745.5  418.35  4950.2  410.04  4955.5  410.56  4981.7  408.00  4992.6  403.67
  5000.1  403.13  5000.6  402.33  5005.6  402.33  5006.1  403.13  5013.2  404.61
  5034.8  405.29  5055.9  408.08  5076.3  405.96  5081.6  407.99  5087.5  406.41
  5107.8  406.49  5113.1  407.33  5139.3  407.47  5144.6  409.06  5170.8  407.71
  5182.5  409.71  5193.0  408.93  5309.1  411.43  5404.0  411.94  5423.0  413.40
  5530.6  413.82  5549.1  415.57  5554.3  414.73  5562.3  416.09  5583.6  415.80
#Mann=3,-1,0
  4745.5     0.1       0  5000.1    0.07       0  5006.1     0.1       0
Bank Sta=5000.1,5006.1
Exp/Cntr=0.3,0.1

Type RM Length L Ch R = 1,1540,167,167,167
BEGIN DESCRIPTION:
Mapping XS a8be9dca
END DESCRIPTION:
XS GIS Cut Line= 3
      2017847.27     13446185.73      2018060.79     13446083.30
      2018277.72     13445359.64
#Sta/Elev= 30
  4571.4  418.57  4602.2  418.21  4668.7  415.69  4721.0  412.42  4766.3  411.23
  4779.6  409.87  4807.8  408.65  4900.4  407.64  4944.8  408.49  4952.6  408.07
  4973.5  404.73  4979.1  403.16  4994.4  402.22  5001.8  400.75  5002.3  399.95
  5007.3  399.95  5007.8  400.75  5017.4  403.08  5036.1  403.28  5050.5  404.79
  5057.0  406.34  5067.4  406.93  5077.9  407.05  5098.8  405.38  5149.7  408.03
  5221.1  409.46  5380.6  410.64  5396.9  412.03  5411.9  411.49  5563.7  413.01
#Mann=3,-1,0
  4571.4     0.1       0  5001.8    0.07       0  5007.8     0.1       0
Bank Sta=5001.8,5007.8
Exp/Cntr=0.3,0.1

Type RM Length L Ch R = 1,1373,346,346,346
BEGIN DESCRIPTION:
Mapping XS 131d26d9
END DESCRIPTION:
XS GIS Cut Line= 3
      2017974.01     13446243.01      2018444.47     13445812.47
      2018841.87     13445732.99
#Sta/Elev= 30
  4635.3  415.50  4641.6  415.95  4670.0  415.04  4769.2  409.11  4818.6  408.14
  4846.9  406.62  4853.7  407.34  4889.5  407.06  4946.2  404.43  4953.0  404.74
  4967.2  404.05  4981.4  402.19  4995.6  401.70  5006.7  400.15  5007.2  399.35
  5012.2  399.35  5012.7  400.15  5016.5  402.07  5030.7  405.29  5044.9  406.46
  5080.7  407.61  5144.2  406.13  5158.4  406.39  5172.5  407.74  5221.9  406.47
  5294.0  406.88  5457.1  409.68  5491.2  409.48  5610.1  413.26  5678.3  413.56
#Mann=3,-1,0
  4635.3     0.1       0  5006.7    0.07       0  5012.7     0.1       0
Bank Sta=5006.7,5012.7
Exp/Cntr=0.3,0.1

Type RM Length L Ch R = 1,1027,293,293,293
BEGIN DESCRIPTION:
Mapping XS 69cf0697
END DESCRIPTION:
XS GIS Cut Line= 3
      2018064.22     13446277.75      2018310.79     13446289.90
      2018737.89     13446091.98
#Sta/Elev= 30
  4742.1  412.40  4772.9  411.80  4853.0  407.77  4963.1  400.92  4973.2  400.73
  4983.2  402.34  4988.6  399.45  4994.0  399.45  5001.6  396.40  5002.1  395.60
  5007.1  395.60  5007.6  396.40  5011.3  400.39  5016.8  399.99  5026.7  403.32
  5057.2  401.11  5062.7  399.11  5070.8  398.65  5103.0  399.52  5131.4  402.07
  5136.9  404.10  5147.9  403.17  5159.8  403.60  5177.2  405.51  5192.0  405.96
  5200.1  407.64  5205.7  406.88  5280.2  409.13  5394.5  410.83  5459.7  410.77
#Mann=3,-1,0
  4742.1     0.1       0  5001.6    0.07       0  5007.6     0.1       0
Bank Sta=5001.6,5007.6
Exp/Cntr=0.3,0.1

Type RM Length L Ch R = 1,734,211,211,211
BEGIN DESCRIPTION:
Mapping XS 6fe084d8
END DESCRIPTION:
XS GIS Cut Line= 4
      2018003.46     13446435.72      2018329.89     13446557.26
      2018661.49     13446333.30      2018765.67     13446180.50
#Sta/Elev= 30
  4475.7  407.75  4594.7  402.57  4648.1  402.02  4662.0  402.78  4742.3  400.43
  4842.6  399.54  4944.5  396.99  4974.4  397.38  4980.5  396.12  4998.5  395.52
  4999.0  394.72  5004.0  394.72  5004.5  395.52  5010.4  396.00  5016.4  399.30
  5023.3  398.60  5052.4  402.21  5082.3  401.30  5103.3  397.84  5109.4  397.55
  5118.3  397.64  5139.3  401.45  5154.3  400.56  5168.1  397.54  5175.3  397.21
  5190.3  399.14  5196.3  401.67  5282.6  406.55  5362.4  408.69  5409.1  407.91
#Mann=3,-1,0
  4475.7     0.1       0  4998.5    0.07       0  5004.5     0.1       0
Bank Sta=4998.5,5004.5
Exp/Cntr=0.3,0.1

Type RM Length L Ch R = 1,523,0,0,0
BEGIN DESCRIPTION:
Mapping XS 9c0bd4a3
END DESCRIPTION:
XS GIS Cut Line= 4
      2017731.08     13446762.27      2018545.17     13446557.26
      2018798.64     13446350.67      2018838.10     13446218.54
#Sta/Elev= 30
  3985.2  407.88  4329.5  406.76  4359.2  404.66  4587.4  399.68  4729.1  398.88
  4868.7  396.57  4911.8  398.08  4918.3  396.48  4940.6  397.21  4947.0  396.27
  4961.4  397.47  4967.8  395.55  4990.1  394.62  4993.6  392.71  4994.1  391.91
  4999.1  391.91  4999.6  392.71  5010.9  394.98  5039.7  394.87  5054.0  397.63
  5060.5  400.82  5068.4  399.50  5074.8  401.46  5095.7  401.21  5103.6  398.91
  5117.9  397.56  5168.1  401.21  5209.8  401.72  5225.9  403.74  5289.6  404.76
#Mann=3,-1,0
  3985.2     0.1       0  4993.6    0.07       0  4999.6     0.1       0
Bank Sta=4993.6,4999.6
Exp/Cntr=0.3,0.1

Chan Stop Cuts=-1