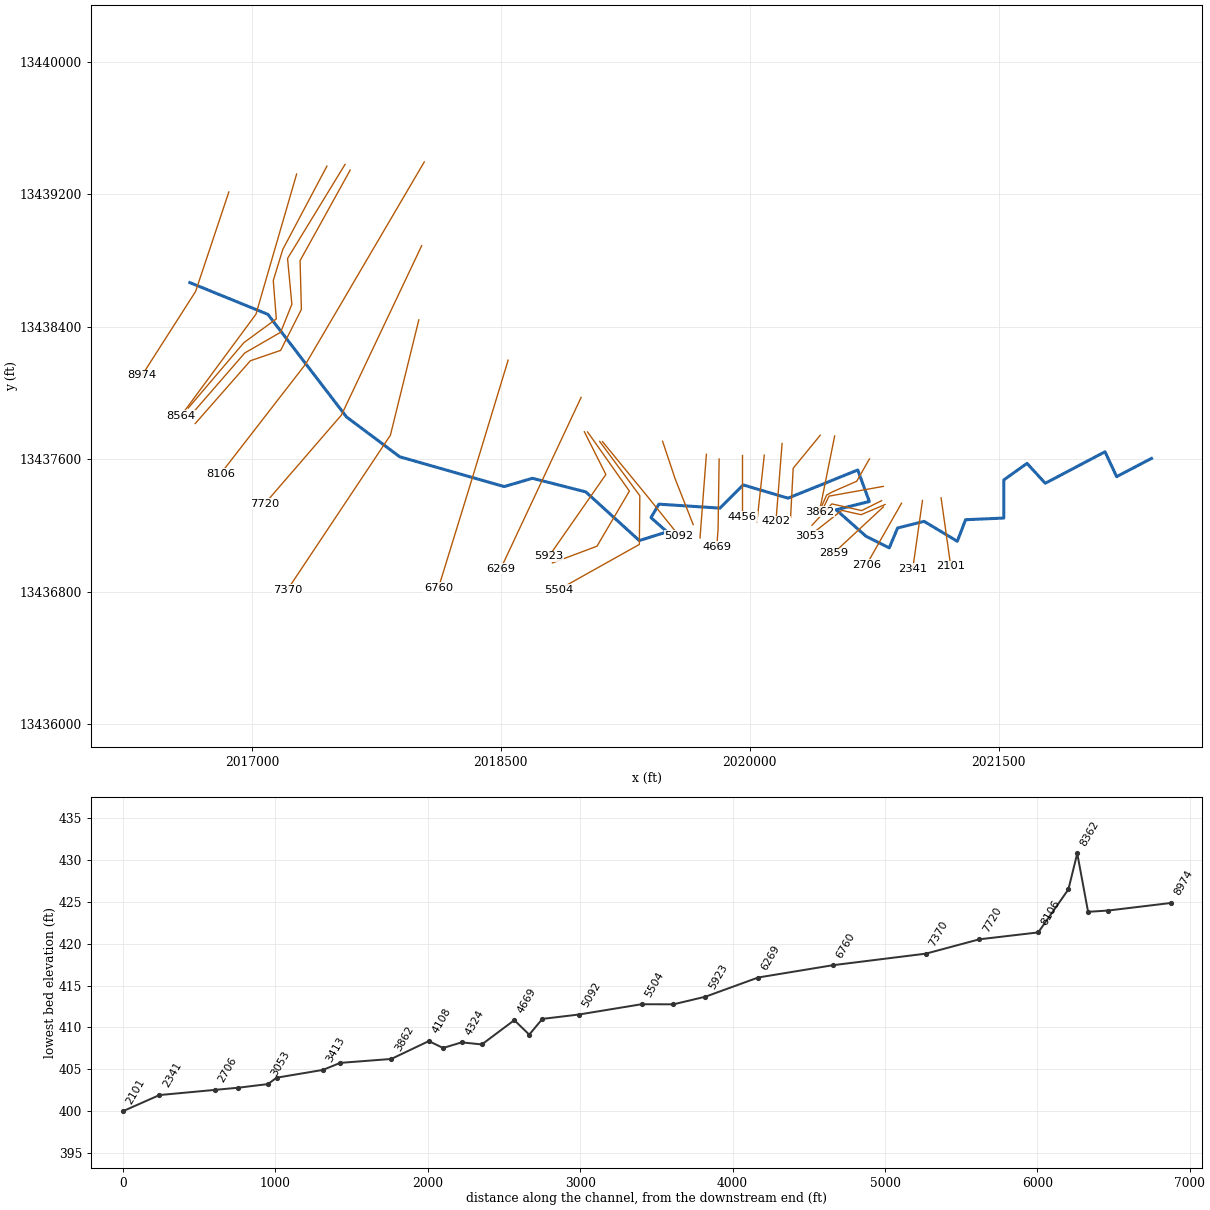
--- UNT 035 in RCW.prj (project) ---

Proj Title=UNT 035 in RCW Base Level Engineering
Current Plan=p01
Default Exp/Contr=0.3,0.1
English Units
Geom File=g01
Flow File=f01
Plan File=p01
BEGIN DESCRIPTION:
UNT 035 in RCW
END DESCRIPTION:

--- UNT 035 in RCW.p01 (plan) ---

Plan Title=Multiple Run
Short Identifier=Multiple
Geom File=g01
Flow File=f01
Subcritical Flow
K Sum by GR= 0
Std Step Tol= 0.01
Critical Tol= 0.01
Num of Std Step Trials= 20
Max Error Tol= 0.3
Flow Tol Ratio= 0.001
Split Flow NTrial= 30
Split Flow Tol= 0.02
Split Flow Ratio= 0.02
Log Output Level= 0
Friction Slope Method= 1
Unsteady Friction Slope Method= 2
Unsteady Bridges Friction Slope Method= 1
Parabolic Critical Depth
Global Vel Dist=  1 , 1 , 1
Global Log Level= 0
CheckData=True
Encroach Param= -1, 0, 0, 0
BEGIN DESCRIPTION:
Multiple Run
END DESCRIPTION:

--- UNT 035 in RCW.f01 (steady flow) ---

Flow Title=Multiple
Number of Profiles=7
Profile Names=10-year,25-year,50-year,1pct_min,100-year,1pct_plu,500-year
River Rch & RM= UNT 035 in RCW,Reach-1,8974
     161     219     265     160     320     639     474
River Rch & RM= UNT 035 in RCW,Reach-1,8433
     185     251     305     185     369     736     548
Boundary for River Rch & Prof#=UNT 035 in RCW,Reach-1,1
Up Type=0
Dn Type=3
Dn Slope=0.005
Boundary for River Rch & Prof#=UNT 035 in RCW,Reach-1,2
Up Type=0
Dn Type=3
Dn Slope=0.005
Boundary for River Rch & Prof#=UNT 035 in RCW,Reach-1,3
Up Type=0
Dn Type=3
Dn Slope=0.005
Boundary for River Rch & Prof#=UNT 035 in RCW,Reach-1,4
Up Type=0
Dn Type=3
Dn Slope=0.005
Boundary for River Rch & Prof#=UNT 035 in RCW,Reach-1,5
Up Type=0
Dn Type=3
Dn Slope=0.005
Boundary for River Rch & Prof#=UNT 035 in RCW,Reach-1,6
Up Type=0
Dn Type=3
Dn Slope=0.005
Boundary for River Rch & Prof#=UNT 035 in RCW,Reach-1,7
Up Type=0
Dn Type=3
Dn Slope=0.005

--- UNT 035 in RCW.g01 (geometry) ---

Geom Title=Existing Conditions

River Reach=UNT 035 in RCW,Reach-1
Reach XY= 30
      2016626.58     13438665.69      2017096.72     13438474.02
      2017570.80     13437854.54      2017890.80     13437614.54
      2018520.80     13437434.54      2018690.80     13437484.54
      2019012.28     13437402.45      2019334.68     13437108.70
      2019501.87     13437161.30      2019404.99     13437247.24
      2019452.91     13437328.49      2019820.80     13437304.54
      2019960.80     13437444.54      2020230.80     13437364.54
      2020650.80     13437534.54      2020720.80     13437344.54
      2020520.80     13437294.54      2020700.80     13437134.54
      2020840.80     13437064.54      2020890.80     13437184.54
      2021050.80     13437224.54      2021250.80     13437104.54
      2021300.80     13437234.54      2021530.80     13437244.54
      2021530.80     13437474.54      2021670.80     13437574.54
      2021780.80     13437454.54      2022140.80     13437644.54
      2022210.80     13437494.54      2022420.80     13437604.54

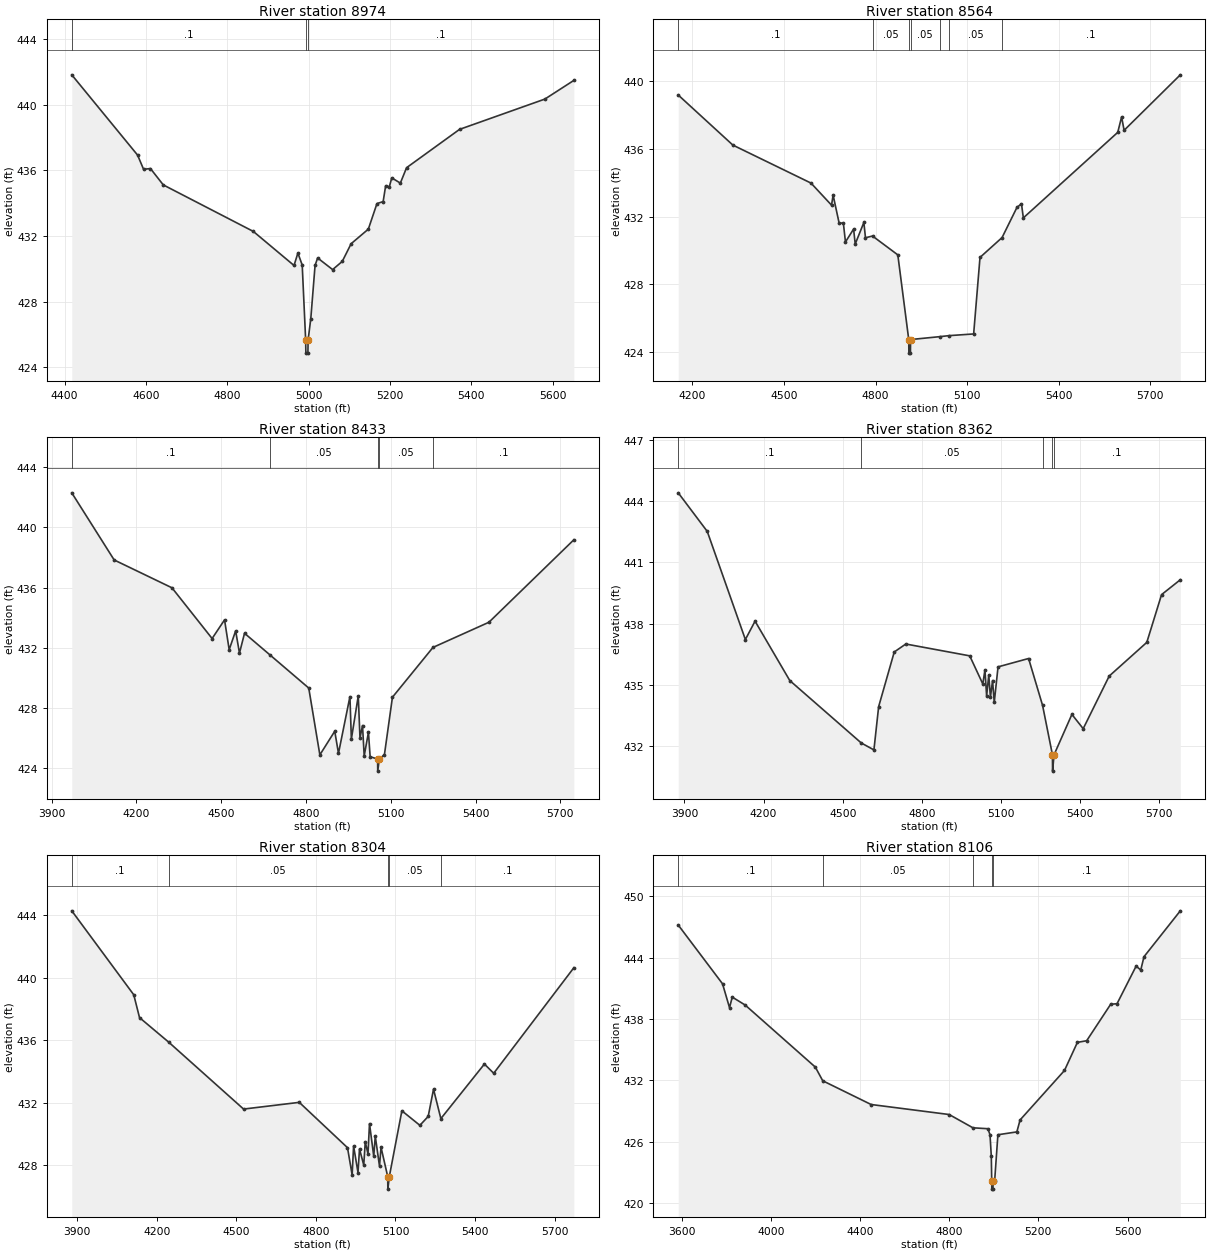
Type RM Length L Ch R = 1,8974,410,410,410
BEGIN DESCRIPTION:
UNT 035 in RCW 7.0
END DESCRIPTION:
XS GIS Cut Line= 3
      2016861.46     13439212.51      2016661.46     13438612.50
      2016337.66     13438104.96
#Sta/Elev= 30
  4417.6  441.84  4579.4  436.94  4594.2  436.07  4611.0  436.12  4642.6  435.12
  4864.0  432.28  4964.1  430.20  4973.6  430.96  4984.2  430.23  4992.7  425.65
  4993.2  424.85  4998.2  424.85  4998.7  425.65  5005.3  426.95  5015.8  430.20
  5022.1  430.66  5059.0  429.95  5082.7  430.45  5104.5  431.53  5146.8  432.42
  5168.0  433.98  5183.2  434.10  5189.4  435.07  5198.4  435.00  5204.4  435.55
  5225.5  435.23  5240.8  436.17  5371.1  438.51  5580.9  440.36  5652.1  441.50
#Mann=3,-1,0
  4417.6     0.1       0  4992.7    0.07       0  4998.7     0.1       0
Bank Sta=4992.7,4998.7
Exp/Cntr=0.3,0.1

Type RM Length L Ch R = 1,8564,131,131,131
BEGIN DESCRIPTION:
UNT 035 in RCW 6.0
END DESCRIPTION:
XS GIS Cut Line= 3
      2017269.95     13439321.10      2017025.00     13438475.00
      2016572.04     13437860.18
#Sta/Elev= 30
  4153.5  439.16  4332.4  436.21  4588.4  433.97  4655.6  432.67  4660.8  433.26
  4680.4  431.62  4694.4  431.61  4701.2  430.50  4727.9  431.26  4733.2  430.38
  4761.5  431.65  4766.8  430.75  4789.9  430.85  4872.7  429.74  4908.5  424.75
  4909.0  423.95  4914.0  423.95  4914.5  424.75  5009.7  424.92  5040.0  424.98
  5121.1  425.08  5141.9  429.59  5214.2  430.76  5263.0  432.54  5277.7  432.75
  5283.9  431.92  5593.1  436.96  5605.7  437.87  5613.9  437.08  5798.0  440.35
#Mann=7,-1,0
  4153.5     0.1       0  4789.9    0.05       0  4908.5    0.03       0
  4914.5    0.05       0  5009.7     0.1       0  5040.0    0.05       0
  5214.2     0.1       0
Bank Sta=4908.5,4914.5
Exp/Cntr=0.3,0.1

Type RM Length L Ch R = 1,8433,71,71,71
BEGIN DESCRIPTION:
Mapping XS 36c7ea5e
END DESCRIPTION:
XS GIS Cut Line= 6
      2017452.25     13439368.44      2017186.62     13438865.81
      2017129.32     13438678.31      2017147.55     13438446.54
      2016952.24     13438303.31      2016617.35     13437908.72
#Sta/Elev= 30
  3971.6  442.29  4121.6  437.83  4326.1  435.98  4468.1  432.61  4512.1  433.85
  4528.5  431.87  4551.4  433.12  4564.9  431.64  4582.8  432.96  4671.6  431.54
  4810.0  429.32  4849.3  424.88  4902.0  426.45  4915.2  424.98  4955.7  428.75
  4960.8  425.93  4985.2  428.80  4991.3  426.00  5000.2  426.83  5006.2  424.81
  5021.2  426.38  5027.2  424.76  5053.6  424.60  5054.1  423.80  5059.6  424.60
  5077.8  424.90  5106.1  428.71  5249.6  432.02  5447.4  433.69  5747.9  439.17
#Mann=5,-1,0
  3971.6     0.1       0  4671.6    0.05       0  5053.6    0.03       0
  5059.6    0.05       0  5249.6     0.1       0
Bank Sta=5053.6,5059.6
Exp/Cntr=0.3,0.1

Type RM Length L Ch R = 1,8362,58,58,58
BEGIN DESCRIPTION:
Mapping XS 4b6a90c7
END DESCRIPTION:
XS GIS Cut Line= 6
      2017561.64     13439378.87      2017215.26     13438811.13
      2017241.30     13438535.08      2017173.59     13438365.81
      2016957.45     13438240.81      2016619.48     13437850.85
#Sta/Elev= 30
  3876.3  444.41  3986.3  442.52  4130.9  437.22  4167.6  438.12  4299.3  435.21
  4570.4  432.15  4618.4  431.81  4636.3  433.93  4695.5  436.61  4739.3  437.00
  4981.7  436.42  5031.4  435.04  5039.4  435.74  5045.8  434.45  5053.9  435.48
  5060.2  434.39  5068.3  435.21  5074.7  434.14  5089.1  435.88  5204.9  436.29
  5258.0  433.99  5295.4  431.57  5295.9  430.77  5301.4  431.57  5369.2  433.55
  5412.0  432.85  5510.7  435.43  5653.2  437.08  5709.2  439.42  5780.3  440.15
#Mann=5,-1,0
  3876.3     0.1       0  4570.4    0.05       0  5258.0     0.1       0
  5295.4    0.03       0  5301.4     0.1       0
Bank Sta=5295.4,5301.4
Exp/Cntr=0.3,0.1

Type RM Length L Ch R = 1,8304,198,198,198
BEGIN DESCRIPTION:
Mapping XS fa1b9304
END DESCRIPTION:
XS GIS Cut Line= 6
      2017592.85     13439344.95      2017290.78     13438798.10
      2017298.59     13438503.83      2017173.59     13438256.44
      2016991.30     13438193.94      2016658.97     13437814.87
#Sta/Elev= 30
  3879.4  444.28  4113.2  438.91  4134.9  437.45  4244.3  435.89  4527.3  431.60
  4737.4  432.03  4919.2  429.13  4936.7  427.39  4942.2  429.24  4958.8  427.54
  4964.5  429.05  4980.5  428.02  4986.2  429.50  4996.5  428.74  5002.2  430.67
  5018.2  428.58  5023.9  429.87  5039.9  427.95  5045.6  429.16  5070.9  427.28
  5071.4  426.48  5076.9  427.28  5124.3  431.49  5192.2  430.56  5223.5  431.13
  5243.6  432.87  5271.3  430.99  5435.5  434.48  5470.6  433.89  5772.8  440.64
#Mann=5,-1,0
  3879.4     0.1       0  4244.3    0.05       0  5070.9    0.03       0
  5076.9    0.05       0  5271.3     0.1       0
Bank Sta=5070.9,5076.9
Exp/Cntr=0.3,0.1

Type RM Length L Ch R = 1,8106,386,386,386
BEGIN DESCRIPTION:
UNT 035 in RCW 5.0
END DESCRIPTION:
XS GIS Cut Line= 3
      2018039.06     13439394.04      2017325.00     13438175.00
      2016810.78     13437510.38
#Sta/Elev= 30
  3583.9  447.18  3782.7  441.43  3814.1  439.09  3826.2  440.13  3884.4  439.35
  4199.1  433.28  4232.4  431.94  4449.4  429.62  4799.7  428.64  4906.4  427.34
  4973.5  427.25  4983.0  426.66  4988.8  424.57  4990.7  422.14  4991.2  421.34
  4996.3  421.34  4996.8  422.14  5003.9  422.17  5018.4  426.66  5103.5  426.94
  5118.0  428.11  5317.2  432.95  5375.2  435.70  5416.8  435.86  5524.6  439.43
  5553.0  439.48  5638.7  443.16  5659.5  442.78  5674.0  444.08  5837.0  448.57
#Mann=5,-1,0
  3583.9     0.1       0  4232.4    0.05       0  4906.4     0.1       0
  4990.7    0.07       0  4996.8     0.1       0
Bank Sta=4990.7,4996.8
Exp/Cntr=0.3,0.1

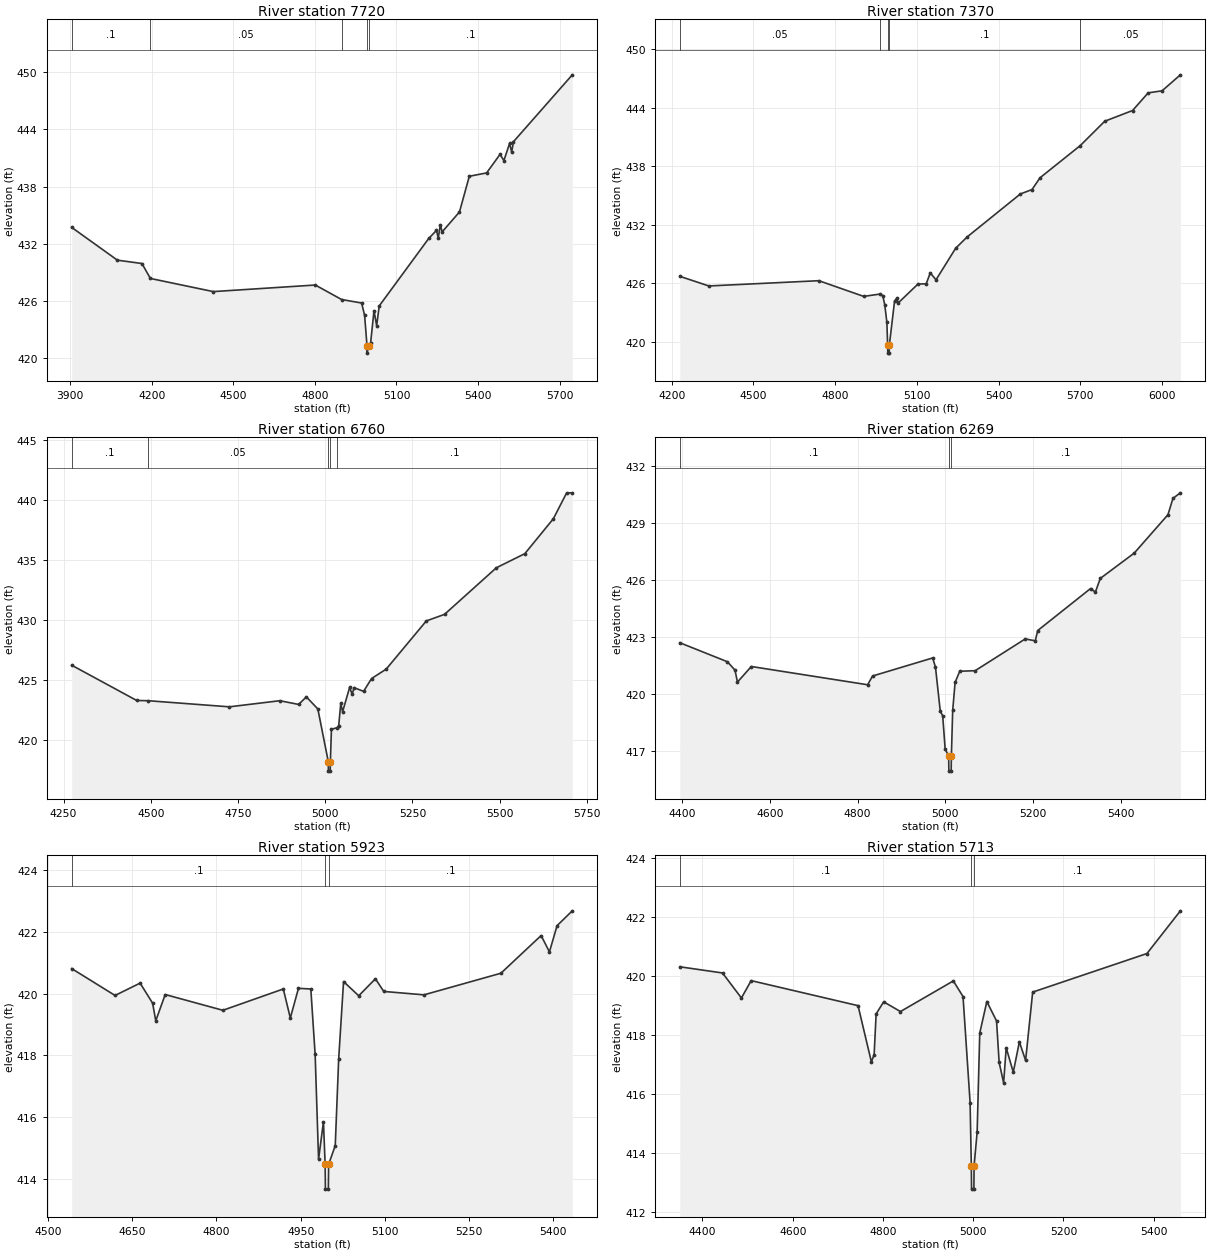
Type RM Length L Ch R = 1,7720,350,350,350
BEGIN DESCRIPTION:
UNT 035 in RCW 4.0
END DESCRIPTION:
XS GIS Cut Line= 3
      2018023.56     13438888.43      2017539.91     13437866.25
      2017076.35     13437329.03
#Sta/Elev= 30
  3906.1  433.72  4074.2  430.28  4164.3  429.93  4195.4  428.36  4426.6  426.98
  4801.7  427.67  4898.3  426.15  4972.0  425.78  4983.0  424.49  4991.7  421.32
  4992.2  420.52  4997.8  421.32  5005.1  421.60  5017.5  424.98  5027.2  423.41
  5036.8  425.48  5218.7  432.56  5247.2  433.41  5253.8  432.62  5261.5  433.98
  5268.1  433.25  5331.7  435.34  5367.9  439.09  5431.5  439.44  5480.9  441.39
  5495.1  440.74  5516.0  442.54  5523.6  441.63  5530.3  442.72  5746.5  449.74
#Mann=5,-1,0
  3906.1     0.1       0  4195.4    0.05       0  4898.3     0.1       0
  4991.7    0.07       0  4997.8     0.1       0
Bank Sta=4991.7,4997.8
Exp/Cntr=0.3,0.1

Type RM Length L Ch R = 1,7370,610,610,610
BEGIN DESCRIPTION:
UNT 035 in RCW 3.0
END DESCRIPTION:
XS GIS Cut Line= 3
      2018006.18     13438440.49      2017835.05     13437744.72
      2017214.41     13436811.58
#Sta/Elev= 30
  4229.8  426.69  4336.4  425.70  4740.1  426.24  4904.8  424.63  4964.7  424.87
  4974.7  424.71  4982.0  423.78  4989.8  421.97  4992.7  419.61  4993.2  418.81
  4998.3  418.81  4998.8  419.61  5018.0  424.15  5025.9  424.43  5031.9  423.97
  5104.0  425.90  5134.1  425.92  5149.1  427.04  5170.1  426.33  5242.3  429.57
  5284.4  430.73  5479.8  435.14  5522.5  435.59  5551.9  436.80  5699.5  440.10
  5789.4  442.60  5891.6  443.70  5948.7  445.51  5999.8  445.72  6067.0  447.36
#Mann=5,-1,0
  4229.8    0.05       0  4964.7     0.1       0  4992.7    0.07       0
  4998.8     0.1       0  5699.5    0.05       0
Bank Sta=4992.7,4998.8
Exp/Cntr=0.3,0.1

Type RM Length L Ch R = 1,6760,491,491,491
BEGIN DESCRIPTION:
UNT 035 in RCW 2.0
END DESCRIPTION:
XS GIS Cut Line= 3
      2018544.38     13438197.45      2018325.00     13437475.00
      2018125.00     13436825.00
#Sta/Elev= 30
  4273.3  426.26  4459.6  423.32  4492.5  423.30  4725.3  422.79  4869.9  423.30
  4923.8  422.99  4946.1  423.62  4979.0  422.61  5008.8  418.23  5009.3  417.43
  5014.4  417.43  5014.9  418.23  5017.9  420.91  5034.5  421.06  5038.8  421.23
  5044.7  423.09  5049.9  422.38  5070.2  424.42  5077.4  423.82  5082.6  424.39
  5110.1  424.08  5133.0  425.15  5174.8  425.93  5289.9  429.95  5342.2  430.50
  5490.6  434.38  5572.4  435.56  5654.1  438.47  5692.1  440.62  5708.4  440.63
#Mann=5,-1,0
  4273.3     0.1       0  4492.5    0.05       0  5008.8   0.035       0
  5014.9    0.05       0  5034.5     0.1       0
Bank Sta=5008.8,5014.9
Exp/Cntr=0.3,0.1

Type RM Length L Ch R = 1,6269,346,346,346
BEGIN DESCRIPTION:
Mapping XS e5c407b0
END DESCRIPTION:
XS GIS Cut Line= 2
      2018984.04     13437972.58      2018500.15     13436939.71
#Sta/Elev= 30
  4394.8  422.71  4503.3  421.71  4520.6  421.27  4526.2  420.64  4557.8  421.46
  4822.8  420.50  4834.0  420.96  4971.0  421.91  4977.4  421.42  4988.3  419.11
  4993.8  418.87  4999.5  417.11  5007.4  416.76  5007.9  415.96  5013.1  415.96
  5013.6  416.76  5016.6  419.15  5022.1  420.62  5032.6  421.21  5067.8  421.24
  5181.9  422.91  5204.8  422.81  5210.3  423.35  5330.8  425.56  5341.7  425.37
  5352.9  426.09  5430.2  427.42  5507.1  429.44  5518.5  430.30  5535.4  430.59
#Mann=3,-1,0
  4394.8     0.1       0  5007.4    0.07       0  5013.6     0.1       0
Bank Sta=5007.4,5013.6
Exp/Cntr=0.3,0.1

Type RM Length L Ch R = 1,5923,210,210,210
BEGIN DESCRIPTION:
Mapping XS 76443882
END DESCRIPTION:
XS GIS Cut Line= 3
      2019003.60     13437765.52      2019133.42     13437507.46
      2018789.47     13437012.76
#Sta/Elev= 30
  4542.2  420.81  4619.4  419.94  4664.0  420.34  4686.3  419.69  4691.9  419.12
  4708.7  419.97  4811.4  419.46  4919.0  420.15  4931.5  419.21  4946.0  420.17
  4968.0  420.15  4975.7  418.03  4981.8  414.64  4990.5  415.85  4993.5  414.47
  4994.0  413.67  4999.2  413.67  4999.7  414.47  5011.5  415.08  5017.6  417.88
  5026.3  420.39  5053.3  419.93  5083.0  420.48  5097.9  420.07  5169.5  419.96
  5306.5  420.66  5378.1  421.88  5392.9  421.35  5406.5  422.20  5433.6  422.68
#Mann=3,-1,0
  4542.2     0.1       0  4993.5    0.07       0  4999.7     0.1       0
Bank Sta=4993.5,4999.7
Exp/Cntr=0.3,0.1

Type RM Length L Ch R = 1,5713,209,209,209
BEGIN DESCRIPTION:
Mapping XS 5d41f0e6
END DESCRIPTION:
XS GIS Cut Line= 4
      2019023.12     13437764.24      2019275.07     13437407.33
      2019079.74     13437074.60      2018811.13     13436973.79
#Sta/Elev= 30
  4349.7  420.31  4444.4  420.10  4486.3  419.25  4507.9  419.84  4744.8  418.99
  4774.4  417.08  4780.5  417.33  4784.9  418.71  4801.6  419.12  4838.8  418.79
  4956.0  419.83  4977.5  419.30  4993.2  415.70  4995.9  413.56  4996.4  412.76
  5001.6  412.76  5002.1  413.56  5008.8  414.70  5014.6  418.06  5030.3  419.13
  5051.8  418.47  5057.6  417.06  5067.5  416.37  5073.2  417.56  5088.9  416.73
  5102.4  417.76  5116.2  417.13  5131.9  419.45  5385.2  420.76  5459.3  422.21
#Mann=3,-1,0
  4349.7     0.1       0  4995.9    0.07       0  5002.1     0.1       0
Bank Sta=4995.9,5002.1
Exp/Cntr=0.3,0.1

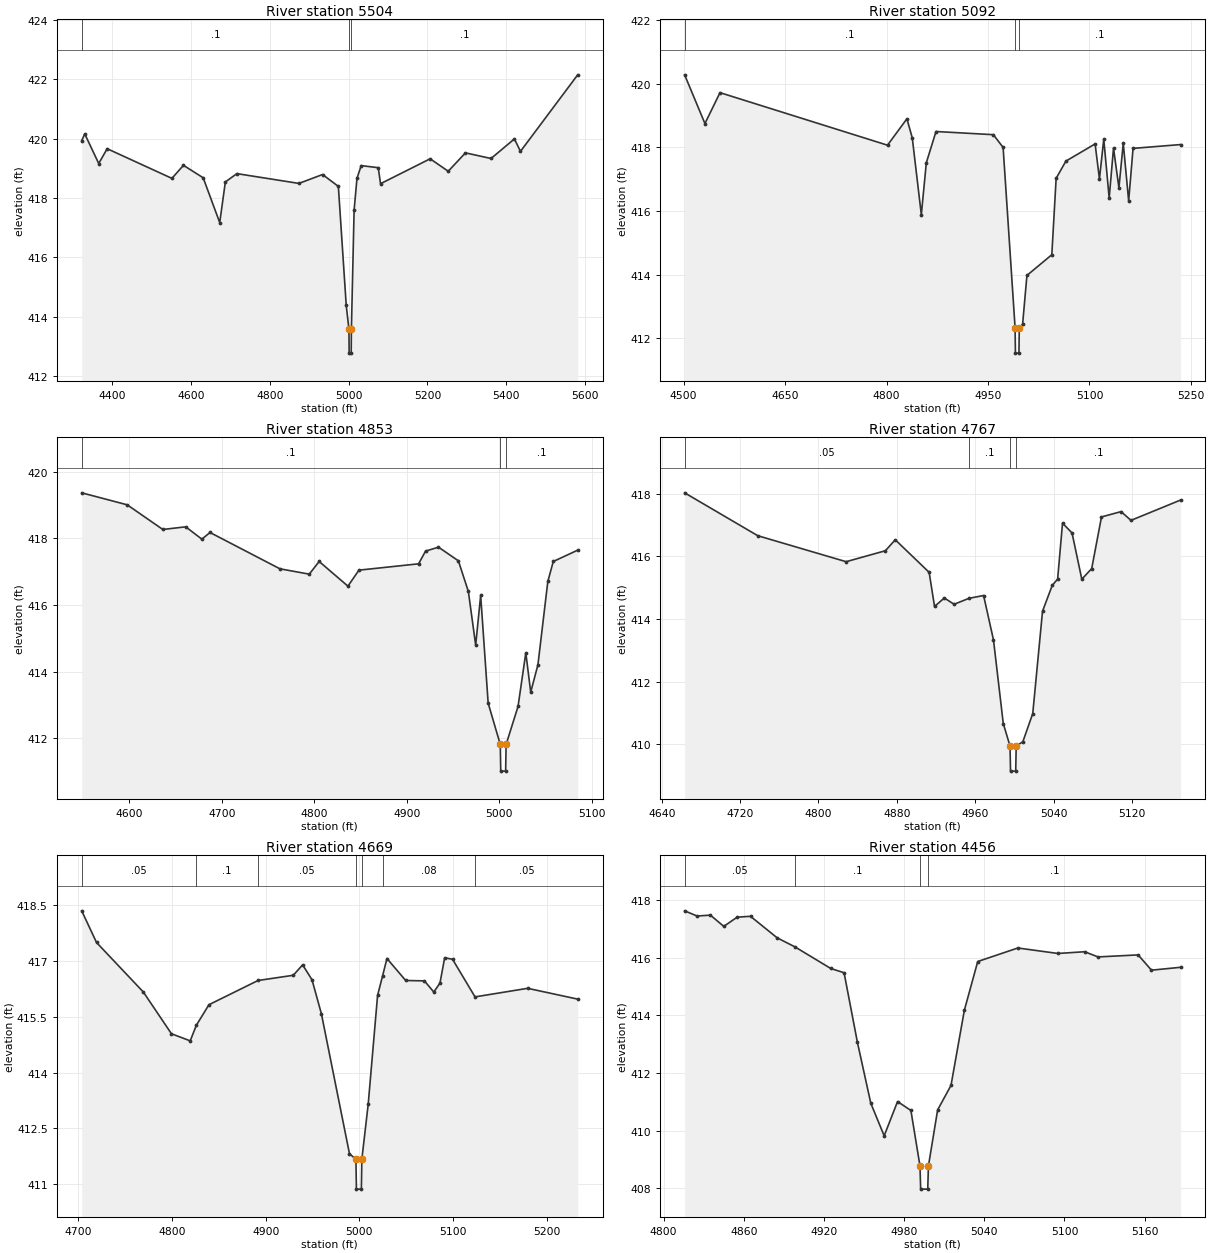
Type RM Length L Ch R = 1,5504,412,412,412
BEGIN DESCRIPTION:
Mapping XS a90e82fe
END DESCRIPTION:
XS GIS Cut Line= 4
      2019096.03     13437706.97      2019337.86     13437379.28
      2019335.03     13437085.35      2018848.30     13436812.27
#Sta/Elev= 30
  4322.2  419.93  4329.9  420.16  4365.4  419.16  4386.8  419.66  4551.2  418.66
  4580.5  419.10  4630.6  418.68  4672.6  417.17  4686.9  418.54  4716.2  418.82
  4873.7  418.49  4933.7  418.79  4973.8  418.39  4993.8  414.38  5000.7  413.57
  5001.2  412.77  5006.4  412.77  5006.9  413.57  5013.8  417.59  5021.1  418.66
  5031.8  419.09  5075.1  419.02  5080.9  418.48  5206.9  419.32  5252.8  418.90
  5296.5  419.52  5361.5  419.33  5420.8  419.99  5436.2  419.57  5581.5  422.15
#Mann=3,-1,0
  4322.2     0.1       0  5000.7    0.07       0  5006.9     0.1       0
Bank Sta=5000.7,5006.9
Exp/Cntr=0.3,0.1

Type RM Length L Ch R = 1,5092,239,239,239
BEGIN DESCRIPTION:
Mapping XS 6d82a6f0
END DESCRIPTION:
XS GIS Cut Line= 3
      2019112.97     13437705.65      2019384.82     13437373.87
      2019574.96     13437136.33
#Sta/Elev= 30
  4501.5  420.28  4531.5  418.75  4553.8  419.72  4801.4  418.07  4830.1  418.90
  4838.0  418.30  4851.4  415.89  4858.8  417.52  4873.1  418.50  4957.9  418.40
  4972.3  418.00  4990.0  412.34  4990.5  411.54  4995.7  411.54  4996.2  412.34
  5001.1  412.44  5007.5  413.98  5044.3  414.63  5050.7  417.03  5065.1  417.57
  5108.3  418.11  5114.7  417.01  5121.1  418.26  5129.1  416.41  5135.5  417.98
  5143.5  416.73  5149.9  418.13  5157.9  416.32  5164.4  417.97  5234.7  418.09
#Mann=3,-1,0
  4501.5     0.1       0  4990.0    0.07       0  4996.2     0.1       0
Bank Sta=4990,4996.2
Exp/Cntr=0.3,0.1

Type RM Length L Ch R = 1,4853,86,86,86
BEGIN DESCRIPTION:
Mapping XS 8c1e9a24
END DESCRIPTION:
XS GIS Cut Line= 3
      2019474.94     13437708.23      2019550.98     13437480.52
      2019659.46     13437204.98
#Sta/Elev= 30
  4548.5  419.37  4597.7  419.01  4636.2  418.27  4660.9  418.35  4678.4  417.98
  4687.2  418.18  4762.8  417.09  4794.5  416.93  4805.2  417.31  4836.3  416.57
  4848.2  417.05  4912.7  417.24  4920.2  417.62  4934.2  417.74  4955.7  417.33
  4966.5  416.41  4974.4  414.80  4979.8  416.29  4987.9  413.06  5001.0  411.82
  5001.5  411.02  5006.8  411.02  5007.3  411.82  5020.2  412.96  5028.6  414.57
  5033.9  413.39  5041.7  414.21  5052.4  416.71  5058.3  417.31  5084.7  417.65
#Mann=3,-1,0
  4548.5     0.1       0  5001.0    0.07       0  5007.3     0.1       0
Bank Sta=5001,5007.3
Exp/Cntr=0.3,0.1

Type RM Length L Ch R = 1,4767,98,98,98
BEGIN DESCRIPTION:
Mapping XS 8d0a90eb
END DESCRIPTION:
XS GIS Cut Line= 2
      2019738.87     13437629.46      2019700.52     13437124.41
#Sta/Elev= 30
  4663.3  418.03  4738.0  416.66  4828.2  415.83  4868.3  416.18  4878.4  416.53
  4913.0  415.49  4918.5  414.40  4928.5  414.67  4938.5  414.47  4953.7  414.66
  4968.6  414.75  4978.7  413.33  4988.7  410.66  4995.6  409.94  4996.1  409.14
  5001.4  409.14  5001.9  409.94  5008.7  410.08  5018.8  410.98  5028.8  414.25
  5038.8  415.08  5044.2  415.27  5049.2  417.06  5058.9  416.75  5068.9  415.27
  5079.0  415.61  5089.0  417.26  5109.0  417.43  5119.1  417.15  5169.8  417.80
#Mann=4,-1,0
  4663.3    0.05       0  4953.7     0.1       0  4995.6    0.07       0
  5001.9     0.1       0
Bank Sta=4995.6,5001.9
Exp/Cntr=0.3,0.1

Type RM Length L Ch R = 1,4669,213,213,213
BEGIN DESCRIPTION:
Mapping XS 14921954
END DESCRIPTION:
XS GIS Cut Line= 3
      2019815.69     13437600.81      2019809.43     13437178.50
      2019801.41     13437071.75
#Sta/Elev= 30
  4703.7  418.34  4719.5  417.49  4769.5  416.16  4799.5  415.04  4819.5  414.85
  4826.1  415.27  4839.5  415.82  4891.9  416.47  4929.5  416.61  4939.5  416.89
  4949.5  416.49  4959.5  415.58  4989.5  411.82  4996.4  411.67  4996.9  410.87
  5002.2  410.87  5002.7  411.67  5009.5  413.15  5019.5  416.07  5024.8  416.59
  5029.5  417.06  5049.5  416.47  5069.5  416.46  5079.5  416.16  5086.1  416.40
  5091.1  417.08  5099.5  417.04  5123.5  416.03  5179.7  416.26  5233.1  415.97
#Mann=7,-1,0
  4703.7    0.05       0  4826.1     0.1       0  4891.9    0.05       0
  4996.4    0.04       0  5002.7    0.05       0  5024.8    0.08       0
  5123.5    0.05       0
Bank Sta=4996.4,5002.7
Exp/Cntr=0.3,0.1

Type RM Length L Ch R = 1,4456,132,132,132
BEGIN DESCRIPTION:
Mapping XS e1628008
END DESCRIPTION:
XS GIS Cut Line= 2
      2019956.32     13437624.26      2019956.32     13437253.16
#Sta/Elev= 30
  4815.8  417.63  4825.1  417.45  4835.1  417.48  4845.1  417.09  4855.1  417.41
  4865.1  417.44  4885.1  416.69  4898.3  416.38  4925.1  415.63  4935.1  415.48
  4945.1  413.06  4955.1  410.95  4965.1  409.82  4975.1  411.01  4985.1  410.70
  4991.9  408.77  4992.4  407.97  4997.7  407.97  4998.2  408.77  5005.1  410.72
  5015.1  411.57  5025.1  414.18  5035.1  415.87  5065.1  416.34  5095.1  416.15
  5115.1  416.21  5125.1  416.03  5155.1  416.10  5165.1  415.57  5186.9  415.67
#Mann=4,-1,0
  4815.8    0.05       0  4898.3     0.1       0  4991.9    0.07       0
  4998.2     0.1       0
Bank Sta=4991.9,4998.2
Exp/Cntr=0.3,0.1

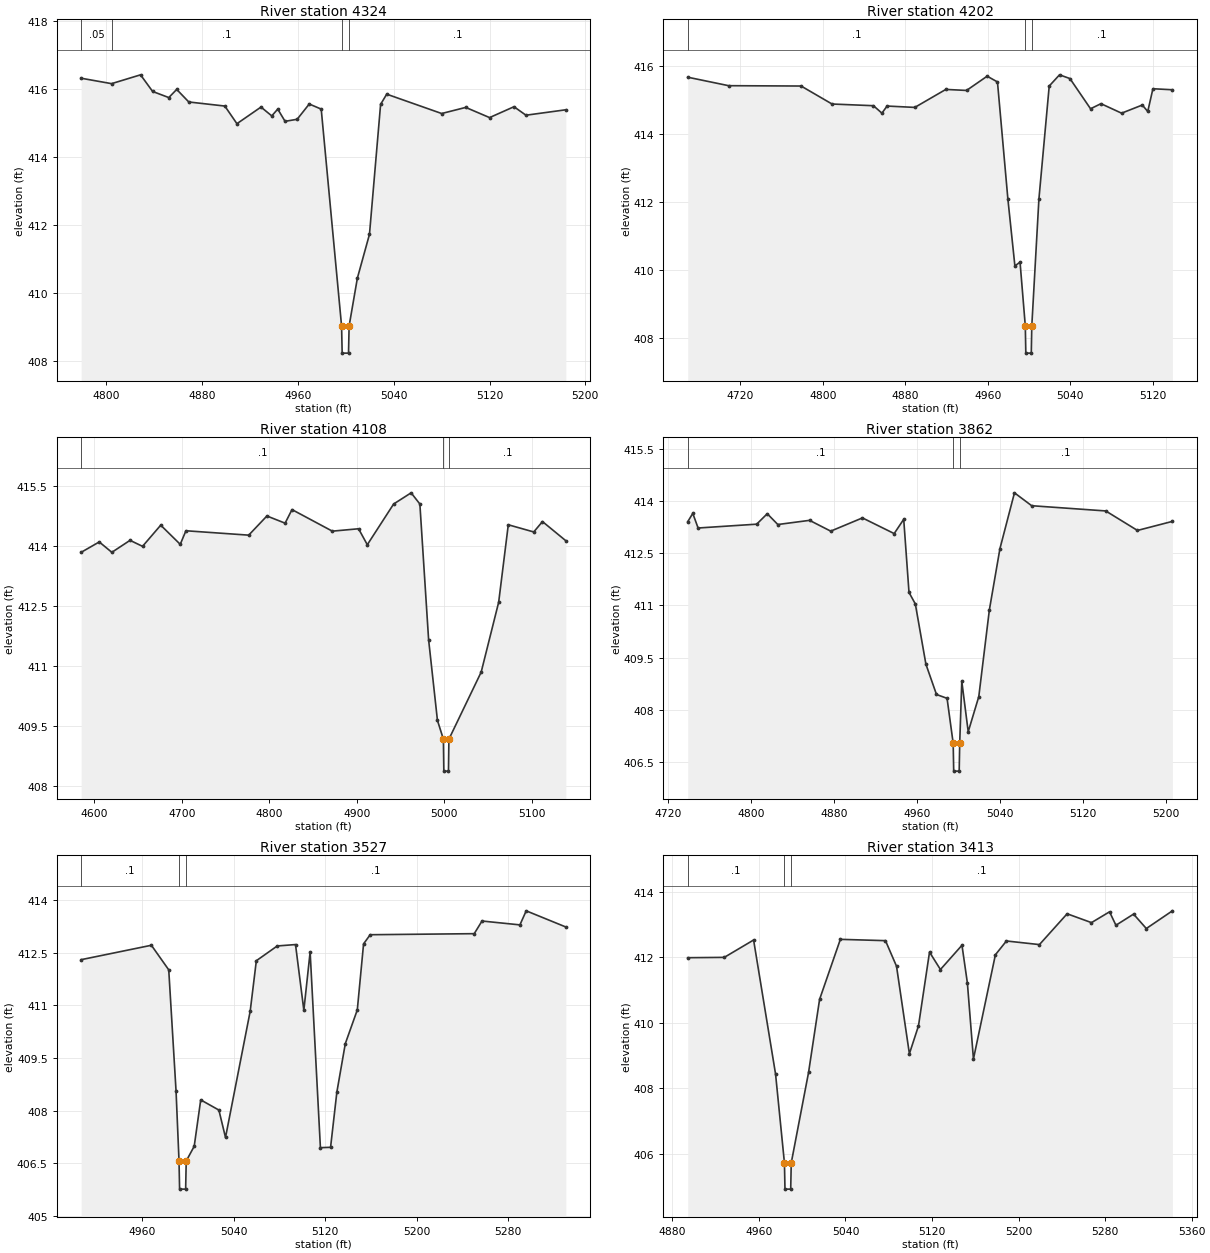
Type RM Length L Ch R = 1,4324,122,122,122
BEGIN DESCRIPTION:
Mapping XS a5a2f68c
END DESCRIPTION:
XS GIS Cut Line= 2
      2020087.83     13437624.31      2020043.56     13437221.94
#Sta/Elev= 30
  4778.9  416.32  4804.3  416.16  4828.5  416.42  4838.6  415.93  4852.1  415.75
  4858.7  415.99  4868.8  415.62  4898.9  415.50  4909.0  414.98  4929.1  415.47
  4938.1  415.21  4943.1  415.41  4949.2  415.05  4959.3  415.11  4969.4  415.56
  4979.4  415.41  4996.4  409.02  4996.9  408.22  5002.2  408.22  5002.7  409.02
  5009.6  410.43  5019.7  411.72  5029.0  415.55  5034.1  415.85  5080.0  415.28
  5100.1  415.46  5120.0  415.16  5140.4  415.48  5150.4  415.23  5183.7  415.39
#Mann=4,-1,0
  4778.9    0.05       0  4804.3     0.1       0  4996.4    0.07       0
  5002.7     0.1       0
Bank Sta=4996.4,5002.7
Exp/Cntr=0.3,0.1

Type RM Length L Ch R = 1,4202,94,94,94
BEGIN DESCRIPTION:
Mapping XS 105d5074
END DESCRIPTION:
XS GIS Cut Line= 2
      2020195.04     13437694.62      2020158.15     13437225.87
#Sta/Elev= 30
  4668.9  415.68  4708.6  415.43  4778.9  415.42  4808.9  414.89  4849.1  414.84
  4857.3  414.62  4862.3  414.83  4889.2  414.79  4919.3  415.32  4939.4  415.29
  4959.4  415.71  4969.4  415.54  4979.5  412.09  4986.3  410.12  4991.3  410.23
  4996.4  408.35  4996.9  407.55  5002.2  407.55  5002.7  408.35  5009.6  412.09
  5019.6  415.42  5029.6  415.75  5039.7  415.64  5059.7  414.75  5069.8  414.90
  5089.8  414.62  5109.9  414.86  5115.2  414.67  5120.2  415.34  5139.1  415.31
#Mann=3,-1,0
  4668.9     0.1       0  4996.4    0.07       0  5002.7     0.1       0
Bank Sta=4996.4,5002.7
Exp/Cntr=0.3,0.1

Type RM Length L Ch R = 1,4108,246,246,246
BEGIN DESCRIPTION:
Mapping XS b0d00218
END DESCRIPTION:
XS GIS Cut Line= 3
      2020424.66     13437744.10      2020261.88     13437544.85
      2020246.34     13437248.35
#Sta/Elev= 30
  4585.0  413.85  4605.7  414.11  4620.1  413.85  4640.9  414.15  4655.2  414.00
  4676.0  414.53  4698.3  414.05  4704.8  414.39  4776.6  414.28  4797.4  414.76
  4818.2  414.58  4826.1  414.92  4872.2  414.38  4902.2  414.44  4912.2  414.04
  4942.3  415.06  4962.3  415.34  4972.3  415.06  4982.3  411.66  4992.4  409.64
  4999.2  409.17  4999.7  408.37  5005.0  408.37  5005.5  409.17  5042.4  410.85
  5062.4  412.60  5073.4  414.54  5102.5  414.36  5112.5  414.62  5139.2  414.14
#Mann=3,-1,0
  4585.0     0.1       0  4999.2    0.07       0  5005.5     0.1       0
Bank Sta=4999.2,5005.5
Exp/Cntr=0.3,0.1

Type RM Length L Ch R = 1,3862,335,335,335
BEGIN DESCRIPTION:
Mapping XS 3b8b36c6
END DESCRIPTION:
XS GIS Cut Line= 2
      2020511.88     13437740.19      2020419.72     13437281.96
#Sta/Elev= 30
  4738.8  413.40  4743.7  413.64  4748.8  413.22  4805.3  413.33  4815.5  413.63
  4825.7  413.32  4856.3  413.44  4876.7  413.13  4907.3  413.51  4937.9  413.06
  4947.1  413.47  4952.2  411.37  4958.3  411.04  4968.5  409.31  4978.7  408.44
  4988.9  408.33  4994.8  407.04  4995.3  406.24  5000.6  406.24  5001.1  407.04
  5003.1  408.82  5009.3  407.37  5019.5  408.38  5029.7  410.87  5039.9  412.63
  5053.9  414.23  5070.5  413.86  5141.9  413.71  5172.5  413.15  5206.2  413.41
#Mann=3,-1,0
  4738.8     0.1       0  4994.8    0.07       0  5001.1     0.1       0
Bank Sta=4994.8,5001.1
Exp/Cntr=0.3,0.1

Type RM Length L Ch R = 1,3527,114,114,114
BEGIN DESCRIPTION:
Mapping XS 1f14ce3a
END DESCRIPTION:
XS GIS Cut Line= 5
      2020721.39     13437601.70      2020644.69     13437466.72
      2020498.86     13437402.92      2020463.70     13437383.39
      2020435.13     13437319.76
#Sta/Elev= 30
  4906.3  412.30  4967.8  412.71  4983.0  412.01  4989.4  408.56  4992.0  406.57
  4992.5  405.77  4997.8  405.77  4998.3  406.57  5005.3  406.99  5011.0  408.31
  5026.9  408.02  5032.7  407.24  5054.3  410.83  5059.7  412.27  5078.0  412.69
  5094.0  412.73  5101.3  410.86  5106.8  412.52  5115.8  406.95  5124.7  406.96
  5130.2  408.53  5137.6  409.91  5148.1  410.87  5153.6  412.75  5159.4  413.01
  5250.5  413.04  5257.3  413.40  5290.5  413.29  5296.0  413.69  5330.7  413.23
#Mann=3,-1,0
  4906.3     0.1       0  4992.0    0.07       0  4998.3     0.1       0
Bank Sta=4992,4998.3
Exp/Cntr=0.3,0.1

Type RM Length L Ch R = 1,3413,304,304,304
BEGIN DESCRIPTION:
Mapping XS 167a7bcf
END DESCRIPTION:
XS GIS Cut Line= 3
      2020804.93     13437435.69      2020478.02     13437376.88
      2020427.26     13437272.75
#Sta/Elev= 30
  4894.2  411.99  4928.0  412.00  4955.1  412.53  4975.4  408.44  4983.6  405.73
  4984.1  404.93  4989.4  404.93  4989.9  405.73  5005.9  408.49  5016.1  410.72
  5035.3  412.55  5077.0  412.51  5087.2  411.73  5099.1  409.06  5107.5  409.91
  5117.7  412.16  5127.8  411.63  5147.7  412.37  5152.7  411.22  5158.3  408.90
  5178.6  412.08  5188.8  412.50  5219.3  412.39  5244.9  413.33  5267.4  413.06
  5284.1  413.39  5290.0  412.98  5306.3  413.32  5318.1  412.88  5342.2  413.42
#Mann=3,-1,0
  4894.2     0.1       0  4983.6    0.07       0  4989.9     0.1       0
Bank Sta=4983.6,4989.9
Exp/Cntr=0.3,0.1

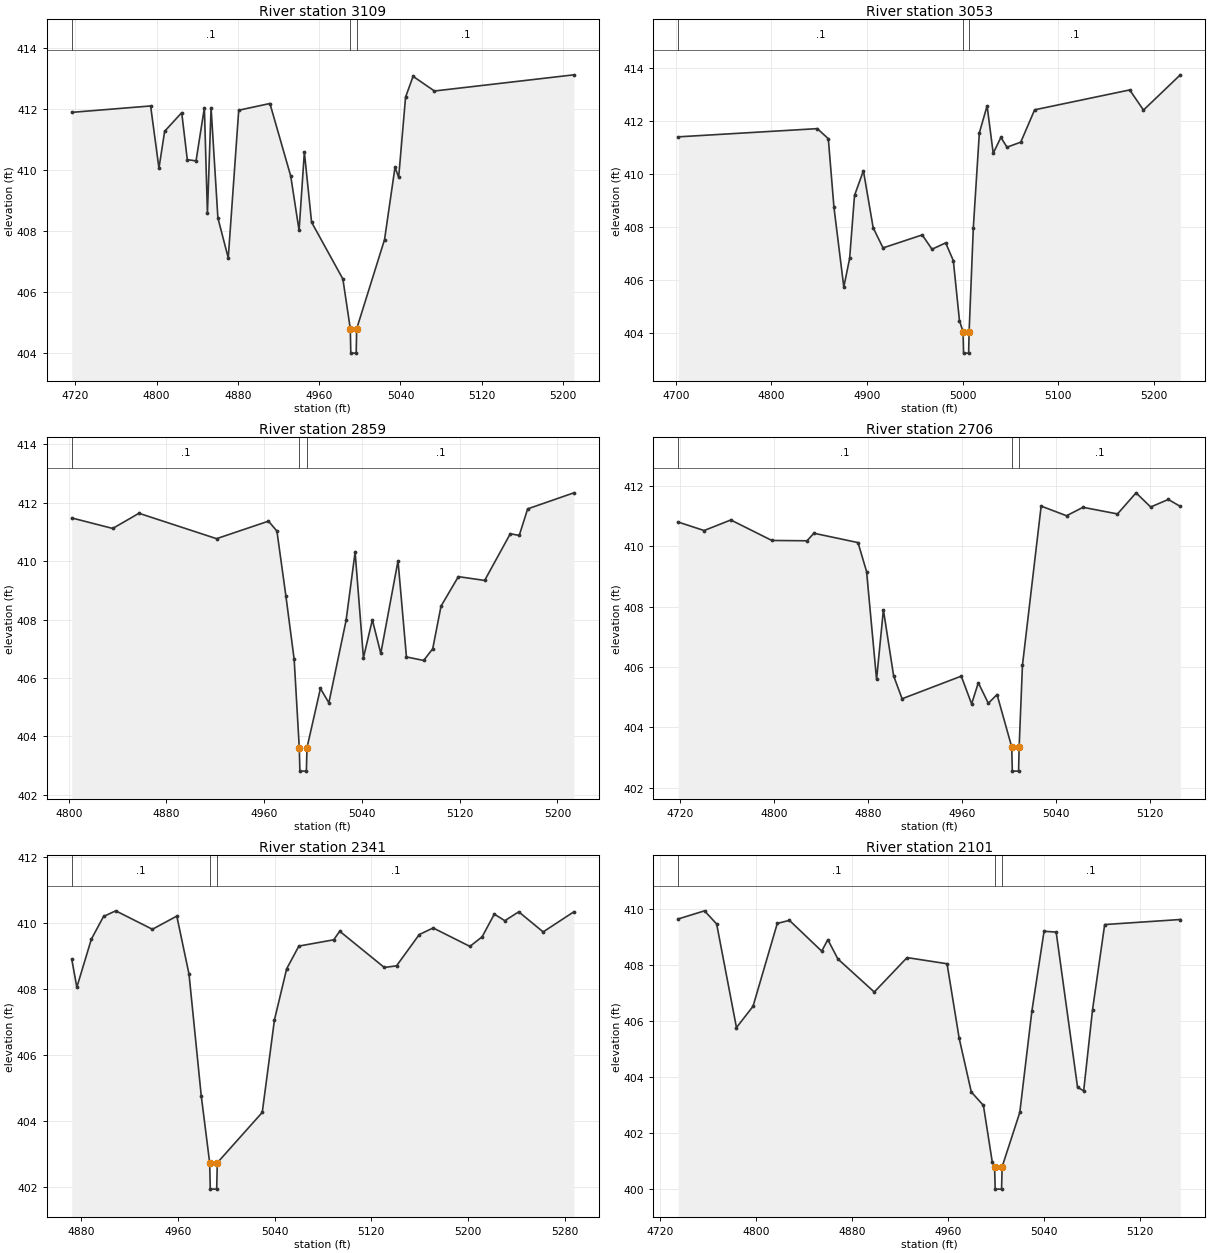
Type RM Length L Ch R = 1,3109,56,56,56
BEGIN DESCRIPTION:
Mapping XS 6c5605f1
END DESCRIPTION:
XS GIS Cut Line= 4
      2020794.41     13437349.53      2020674.64     13437289.64
      2020494.95     13437330.01      2020375.13     13437201.06
#Sta/Elev= 30
  4716.5  411.89  4794.1  412.10  4802.3  410.06  4807.9  411.27  4824.7  411.88
  4830.2  410.34  4838.8  410.30  4847.0  412.04  4850.0  408.58  4853.6  412.04
  4860.3  408.43  4870.5  407.12  4880.8  411.96  4911.5  412.18  4932.0  409.80
  4940.2  408.02  4945.4  410.59  4952.5  408.29  4983.3  406.43  4990.6  404.80
  4991.1  404.00  4996.4  404.00  4996.9  404.80  5024.3  407.72  5034.6  410.09
  5038.2  409.76  5045.0  412.39  5052.4  413.07  5073.4  412.59  5210.6  413.12
#Mann=3,-1,0
  4716.5     0.1       0  4990.6    0.07       0  4996.9     0.1       0
Bank Sta=4990.6,4996.9
Exp/Cntr=0.3,0.1

Type RM Length L Ch R = 1,3053,194,194,194
BEGIN DESCRIPTION:
Mapping XS 6d342e0c
END DESCRIPTION:
XS GIS Cut Line= 4
      2020815.25     13437326.09      2020670.73     13437264.90
      2020554.84     13437290.94      2020359.13     13437136.71
#Sta/Elev= 30
  4702.6  411.40  4848.0  411.71  4859.5  411.33  4865.4  408.74  4875.7  405.73
  4881.8  406.82  4886.9  409.19  4896.2  410.12  4906.4  407.97  4916.7  407.21
  4957.7  407.70  4967.9  407.16  4982.2  407.40  4990.2  406.73  4996.6  404.47
  5000.4  404.04  5000.9  403.24  5006.2  403.24  5006.7  404.04  5011.1  407.97
  5017.4  411.55  5025.5  412.57  5031.9  410.78  5039.9  411.38  5046.3  411.01
  5060.7  411.20  5075.2  412.42  5174.6  413.17  5189.0  412.41  5227.5  413.74
#Mann=3,-1,0
  4702.6     0.1       0  5000.4    0.07       0  5006.7     0.1       0
Bank Sta=5000.4,5006.7
Exp/Cntr=0.3,0.1

Type RM Length L Ch R = 1,2859,153,153,153
BEGIN DESCRIPTION:
Mapping XS 2b668675
END DESCRIPTION:
XS GIS Cut Line= 2
      2020805.37     13437312.04      2020504.59     13437032.09
#Sta/Elev= 30
  4802.5  411.48  4836.0  411.12  4857.5  411.64  4921.0  410.77  4963.5  411.37
  4970.4  411.03  4977.7  408.82  4984.5  406.64  4988.7  403.61  4989.2  402.81
  4994.5  402.81  4995.0  403.61  5006.0  405.64  5012.9  405.15  5027.0  407.97
  5034.4  410.31  5041.2  406.69  5048.5  407.99  5055.4  406.84  5069.5  410.01
  5076.4  406.72  5090.5  406.60  5097.9  407.00  5104.7  408.46  5118.9  409.47
  5140.4  409.34  5161.4  410.94  5168.7  410.88  5175.6  411.79  5213.4  412.34
#Mann=3,-1,0
  4802.5     0.1       0  4988.7    0.07       0  4995.0     0.1       0
Bank Sta=4988.7,4995
Exp/Cntr=0.3,0.1

Type RM Length L Ch R = 1,2706,365,365,365
BEGIN DESCRIPTION:
Mapping XS bf523089
END DESCRIPTION:
XS GIS Cut Line= 2
      2020914.74     13437334.16      2020703.83     13436963.12
#Sta/Elev= 30
  4718.7  410.81  4740.7  410.53  4763.4  410.88  4798.3  410.20  4828.2  410.19
  4834.0  410.44  4871.5  410.13  4878.8  409.17  4887.3  405.59  4893.1  407.90
  4901.8  405.71  4909.0  404.95  4959.3  405.70  4968.1  404.78  4973.8  405.48
  4982.3  404.80  4989.7  405.09  5002.2  403.35  5002.7  402.55  5008.0  402.55
  5008.5  403.35  5011.3  406.06  5027.2  411.34  5048.8  411.02  5062.8  411.30
  5092.1  411.08  5107.9  411.78  5120.3  411.31  5135.3  411.56  5145.5  411.33
#Mann=3,-1,0
  4718.7     0.1       0  5002.2    0.07       0  5008.5     0.1       0
Bank Sta=5002.2,5008.5
Exp/Cntr=0.3,0.1

Type RM Length L Ch R = 1,2341,240,240,240
BEGIN DESCRIPTION:
Mapping XS 4ffd6e54
END DESCRIPTION:
XS GIS Cut Line= 2
      2021041.04     13437351.06      2020982.47     13436939.81
#Sta/Elev= 30
  4872.2  408.91  4876.4  408.06  4888.4  409.52  4898.5  410.21  4908.6  410.38
  4938.9  409.82  4959.1  410.22  4969.2  408.46  4979.3  404.77  4986.3  402.73
  4986.8  401.93  4992.1  401.93  4992.6  402.73  5029.8  404.26  5039.9  407.07
  5050.0  408.62  5060.1  409.31  5088.9  409.50  5093.9  409.76  5130.8  408.66
  5140.9  408.71  5159.7  409.66  5171.2  409.86  5201.6  409.30  5211.7  409.59
  5221.8  410.28  5230.5  410.08  5242.0  410.35  5262.2  409.74  5287.6  410.35
#Mann=3,-1,0
  4872.2     0.1       0  4986.3    0.07       0  4992.6     0.1       0
Bank Sta=4986.3,4992.6
Exp/Cntr=0.3,0.1

Type RM Length L Ch R = 1,2101,341,341,341
BEGIN DESCRIPTION:
Mapping XS d74e456c
END DESCRIPTION:
XS GIS Cut Line= 2
      2021153.02     13437366.73      2021211.62     13436952.65
#Sta/Elev= 30
  4735.2  409.65  4757.1  409.94  4767.2  409.47  4783.7  405.77  4797.5  406.53
  4817.7  409.49  4827.8  409.60  4854.7  408.50  4859.8  408.91  4868.2  408.22
  4898.5  407.04  4925.8  408.27  4959.1  408.05  4969.2  405.39  4979.3  403.47
  4989.4  402.99  4996.8  400.96  4998.7  400.80  4999.2  400.00  5004.5  400.00
  5005.0  400.80  5019.7  402.74  5029.8  406.37  5039.9  409.21  5050.0  409.18
  5067.8  403.64  5072.9  403.51  5080.3  406.41  5090.4  409.45  5153.4  409.63
#Mann=3,-1,0
  4735.2     0.1       0  4998.7    0.07       0  5005.0     0.1       0
Bank Sta=4998.7,5005
Exp/Cntr=0.3,0.1