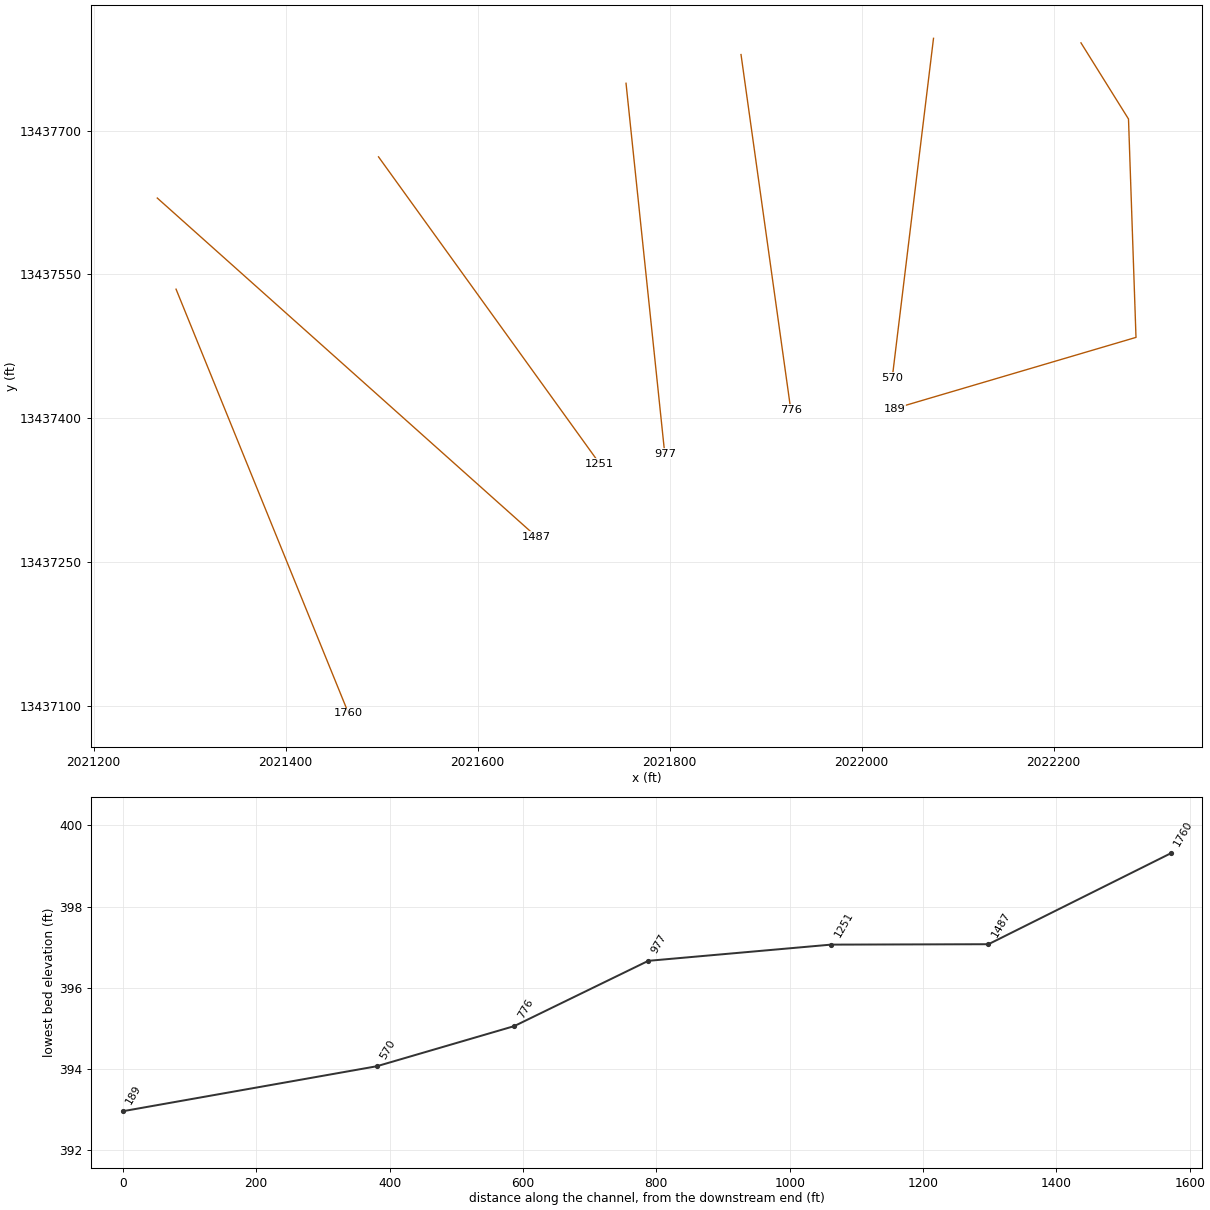
HEC-RAS study UNT 035 in RCW.prj: UNT 035 in RCW Base Level Engineering

--- UNT 035 in RCW.g01 (geometry) --- (continued)

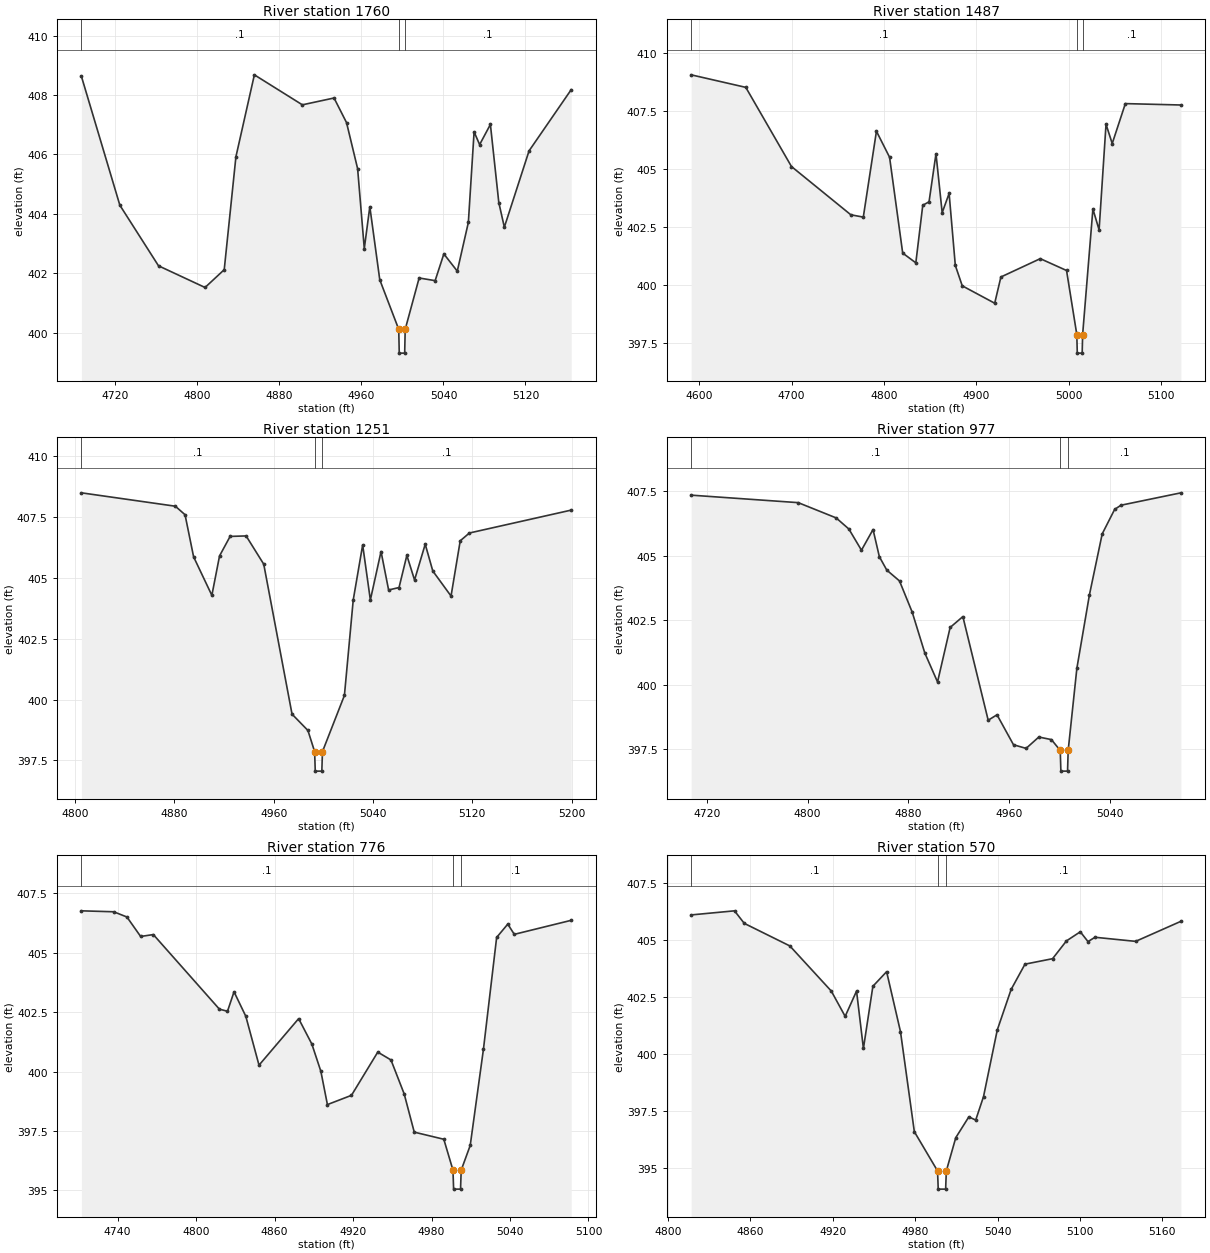
Type RM Length L Ch R = 1,1760,273,273,273
BEGIN DESCRIPTION:
Mapping XS efc81799
END DESCRIPTION:
XS GIS Cut Line= 2
      2021285.85     13437534.65      2021465.51     13437092.02
#Sta/Elev= 30
  4686.9  408.63  4724.4  404.29  4762.1  402.25  4807.5  401.52  4826.2  402.12
  4837.6  405.92  4855.6  408.68  4902.4  407.67  4933.3  407.90  4945.5  407.07
  4956.3  405.52  4962.8  402.83  4968.2  404.24  4977.9  401.78  4996.4  400.11
  4996.9  399.31  5002.2  399.31  5002.7  400.11  5016.3  401.84  5031.9  401.75
  5040.4  402.65  5053.5  402.07  5064.3  403.71  5069.9  406.76  5075.3  406.33
  5085.8  407.01  5094.0  404.38  5099.4  403.55  5123.5  406.12  5164.6  408.18
#Mann=3,-1,0
  4686.9     0.1       0  4996.4    0.07       0  5002.7     0.1       0
Bank Sta=4996.4,5002.7
Exp/Cntr=0.3,0.1

Type RM Length L Ch R = 1,1487,236,236,236
BEGIN DESCRIPTION:
Mapping XS 3c87db68
END DESCRIPTION:
XS GIS Cut Line= 2
      2021266.29     13437629.75      2021661.05     13437276.55
#Sta/Elev= 30
  4591.4  409.06  4650.5  408.52  4699.9  405.11  4764.1  403.03  4777.6  402.93
  4791.8  406.63  4806.0  405.51  4820.2  401.38  4834.4  400.96  4841.9  403.44
  4848.7  403.59  4856.2  405.66  4862.9  403.12  4870.4  403.95  4877.1  400.85
  4884.6  399.97  4919.7  399.22  4926.4  400.35  4969.0  401.14  4997.4  400.63
  5008.5  397.87  5009.0  397.07  5014.3  397.07  5014.8  397.87  5025.9  403.28
  5032.6  402.38  5040.1  406.93  5046.8  406.10  5061.0  407.82  5121.1  407.76
#Mann=3,-1,0
  4591.4     0.1       0  5008.5    0.07       0  5014.8     0.1       0
Bank Sta=5008.5,5014.8
Exp/Cntr=0.3,0.1

Type RM Length L Ch R = 1,1251,274,274,274
BEGIN DESCRIPTION:
Mapping XS be05c704
END DESCRIPTION:
XS GIS Cut Line= 2
      2021496.75     13437672.74      2021727.22     13437352.44
#Sta/Elev= 30
  4805.1  408.49  4880.8  407.94  4888.6  407.59  4895.5  405.86  4910.2  404.28
  4916.4  405.90  4924.9  406.70  4937.8  406.72  4952.0  405.56  4974.8  399.40
  4987.6  398.73  4993.0  397.86  4993.5  397.06  4998.8  397.06  4999.3  397.86
  5017.0  400.17  5024.1  404.09  5031.7  406.35  5037.9  404.09  5046.5  406.08
  5052.6  404.50  5061.0  404.60  5067.3  405.92  5073.5  404.91  5082.1  406.38
  5088.2  405.28  5102.9  404.25  5110.3  406.52  5117.7  406.84  5199.7  407.78
#Mann=3,-1,0
  4805.1     0.1       0  4993.0    0.07       0  4999.3     0.1       0
Bank Sta=4993,4999.3
Exp/Cntr=0.3,0.1

Type RM Length L Ch R = 1,977,201,201,201
BEGIN DESCRIPTION:
Mapping XS e7885cfd
END DESCRIPTION:
XS GIS Cut Line= 2
      2021754.59     13437749.50      2021794.95     13437362.80
#Sta/Elev= 30
  4707.6  407.34  4792.6  407.05  4822.7  406.46  4832.8  406.03  4842.8  405.21
  4852.0  406.01  4857.0  404.96  4862.9  404.44  4873.0  404.02  4883.1  402.81
  4893.1  401.23  4903.2  400.11  4913.2  402.22  4923.3  402.64  4943.4  398.63
  4950.4  398.84  4963.5  397.68  4973.5  397.54  4983.6  397.98  4993.6  397.88
  5000.6  397.46  5001.1  396.66  5006.4  396.66  5006.9  397.46  5013.8  400.64
  5023.8  403.49  5033.9  405.84  5043.8  406.79  5048.8  406.95  5096.4  407.43
#Mann=3,-1,0
  4707.6     0.1       0  5000.6    0.07       0  5006.9     0.1       0
Bank Sta=5000.6,5006.9
Exp/Cntr=0.3,0.1

Type RM Length L Ch R = 1,776,206,206,206
BEGIN DESCRIPTION:
Mapping XS 1781deb4
END DESCRIPTION:
XS GIS Cut Line= 2
      2021874.38     13437779.46      2021926.25     13437408.57
#Sta/Elev= 30
  4712.3  406.77  4737.0  406.73  4747.1  406.51  4757.6  405.69  4767.3  405.77
  4817.8  402.63  4824.0  402.54  4829.0  403.36  4838.0  402.33  4848.1  400.27
  4878.4  402.23  4888.5  401.16  4895.4  400.01  4900.4  398.61  4918.8  399.00
  4938.9  400.82  4949.0  400.49  4959.1  399.06  4966.8  397.45  4989.4  397.15
  4996.4  395.85  4996.9  395.05  5002.2  395.05  5002.7  395.85  5009.6  396.89
  5019.7  400.94  5029.8  405.65  5038.3  406.21  5043.3  405.78  5086.8  406.37
#Mann=3,-1,0
  4712.3     0.1       0  4996.4    0.07       0  5002.7     0.1       0
Bank Sta=4996.4,5002.7
Exp/Cntr=0.3,0.1

Type RM Length L Ch R = 1,570,381,381,381
BEGIN DESCRIPTION:
Mapping XS a162302f
END DESCRIPTION:
XS GIS Cut Line= 2
      2022074.90     13437796.40      2022031.92     13437442.20
#Sta/Elev= 30
  4816.8  406.09  4848.4  406.27  4855.5  405.72  4888.7  404.73  4918.9  402.75
  4929.0  401.64  4937.3  402.75  4942.3  400.23  4949.2  402.96  4959.2  403.60
  4969.3  400.97  4979.4  396.58  4996.3  394.86  4996.8  394.06  5002.2  394.06
  5002.7  394.86  5009.6  396.32  5019.1  397.23  5024.1  397.09  5029.8  398.12
  5039.8  401.04  5049.9  402.82  5060.0  403.93  5080.1  404.17  5090.2  404.95
  5100.3  405.35  5105.9  404.92  5111.0  405.11  5140.6  404.93  5173.6  405.81
#Mann=3,-1,0
  4816.8     0.1       0  4996.3    0.07       0  5002.7     0.1       0
Bank Sta=4996.3,5002.7
Exp/Cntr=0.3,0.1

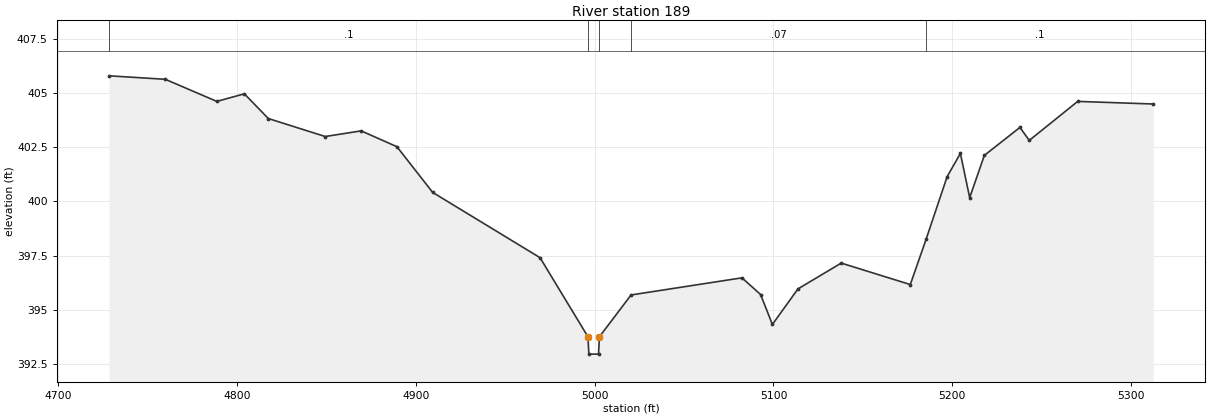
Type RM Length L Ch R = 1,189,0,0,0
BEGIN DESCRIPTION:
UNT 035 in RCW 1.0
END DESCRIPTION:
XS GIS Cut Line= 4
      2022228.52     13437791.68      2022278.02     13437712.21
      2022285.83     13437484.35      2022034.49     13437410.11
#Sta/Elev= 30
  4728.6  405.79  4760.0  405.63  4788.8  404.61  4804.2  404.96  4817.6  403.82
  4849.4  402.99  4869.5  403.25  4889.5  402.52  4909.5  400.41  4969.5  397.40
  4996.3  393.75  4996.8  392.95  5002.2  392.95  5002.7  393.75  5020.4  395.68
  5082.4  396.47  5092.8  395.70  5099.4  394.32  5113.7  395.96  5137.9  397.15
  5176.5  396.16  5185.3  398.24  5197.1  401.14  5204.5  402.21  5209.7  400.17
  5217.9  402.12  5237.8  403.41  5243.0  402.81  5270.1  404.61  5312.3  404.49
#Mann=5,-1,0
  4728.6     0.1       0  4996.3    0.07       0  5002.7     0.1       0
  5020.4    0.07       0  5185.3     0.1       0
Bank Sta=4996.3,5002.7
Exp/Cntr=0.3,0.1

Chan Stop Cuts=-1