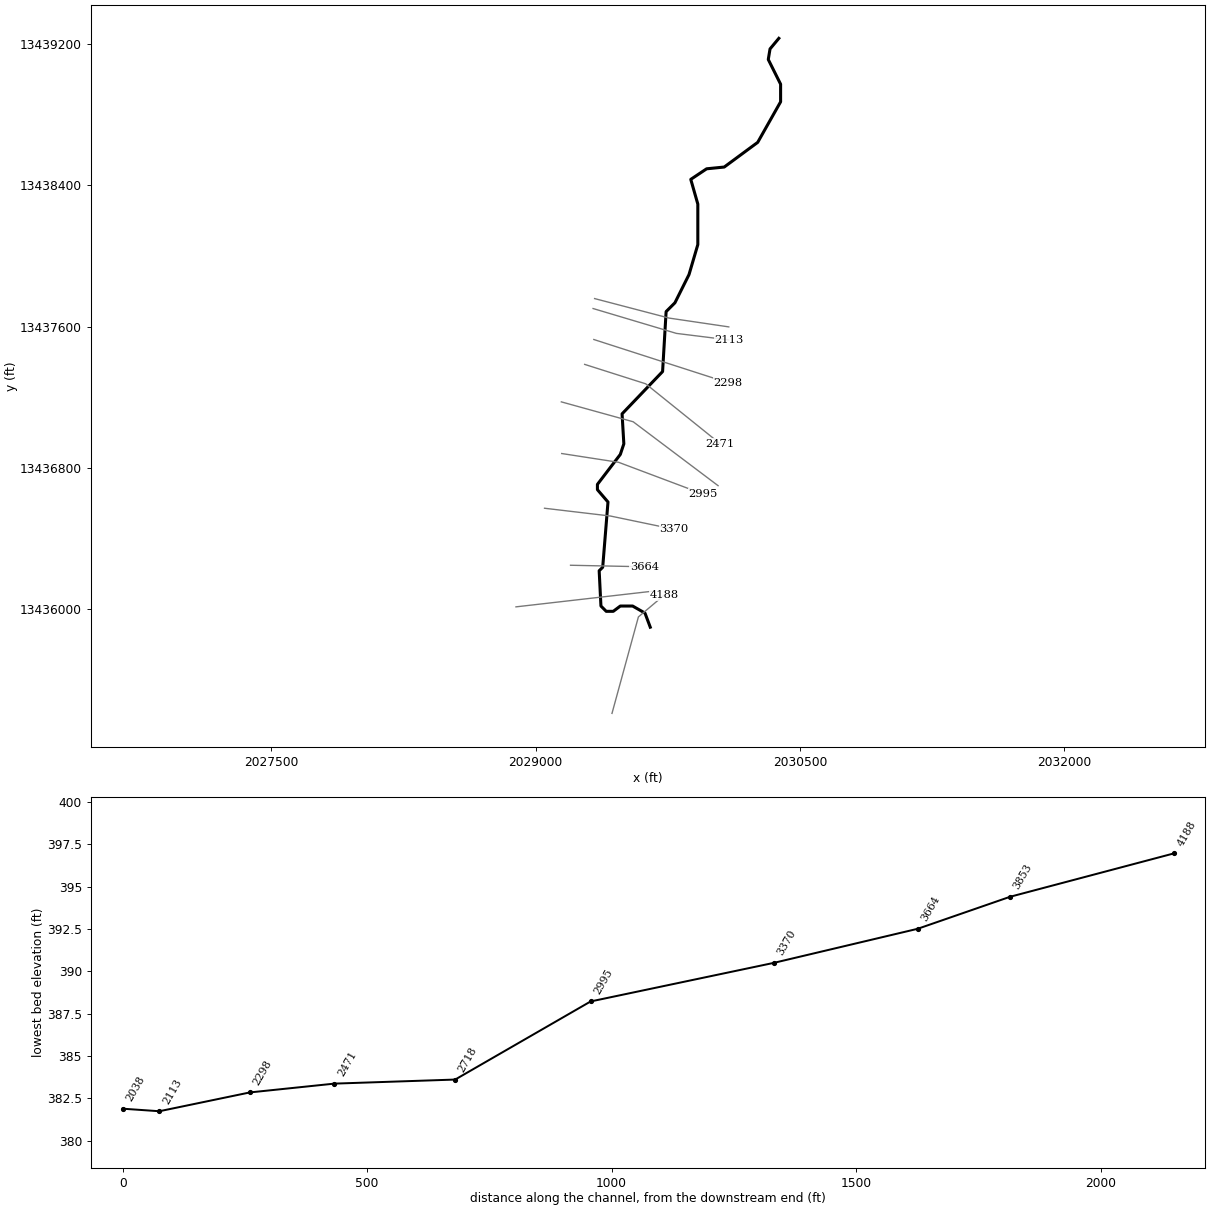
--- UNT 036 in RCW.prj (project) ---

Proj Title=UNT 036 in RCW Base Level Engineering
Current Plan=p01
Default Exp/Contr=0.3,0.1
English Units
Geom File=g01
Flow File=f01
Plan File=p01
BEGIN DESCRIPTION:
UNT 036 in RCW
END DESCRIPTION:

--- UNT 036 in RCW.p01 (plan) ---

Plan Title=Multiple Run
Short Identifier=Multiple
Geom File=g01
Flow File=f01
Subcritical Flow
K Sum by GR= 0
Std Step Tol= 0.01
Critical Tol= 0.01
Num of Std Step Trials= 20
Max Error Tol= 0.3
Flow Tol Ratio= 0.001
Split Flow NTrial= 30
Split Flow Tol= 0.02
Split Flow Ratio= 0.02
Log Output Level= 0
Friction Slope Method= 1
Unsteady Friction Slope Method= 2
Unsteady Bridges Friction Slope Method= 1
Parabolic Critical Depth
Global Vel Dist=  1 , 1 , 1
Global Log Level= 0
CheckData=True
Encroach Param= -1, 0, 0, 0
BEGIN DESCRIPTION:
Multiple Run
END DESCRIPTION:

--- UNT 036 in RCW.f01 (steady flow) ---

Flow Title=Multiple
Number of Profiles=7
Profile Names=10-year,25-year,50-year,1pct_min,100-year,1pct_plu,500-year
River Rch & RM= UNT 036 in RCW,Reach-1,4188
     139     188     228     138     275     549     407
River Rch & RM= UNT 036 in RCW,Reach-1,3853
     255     356     441     272     543    1083     836
Boundary for River Rch & Prof#=UNT 036 in RCW,Reach-1,1
Up Type=0
Dn Type=3
Dn Slope=0.005
Boundary for River Rch & Prof#=UNT 036 in RCW,Reach-1,2
Up Type=0
Dn Type=3
Dn Slope=0.005
Boundary for River Rch & Prof#=UNT 036 in RCW,Reach-1,3
Up Type=0
Dn Type=3
Dn Slope=0.005
Boundary for River Rch & Prof#=UNT 036 in RCW,Reach-1,4
Up Type=0
Dn Type=3
Dn Slope=0.005
Boundary for River Rch & Prof#=UNT 036 in RCW,Reach-1,5
Up Type=0
Dn Type=3
Dn Slope=0.005
Boundary for River Rch & Prof#=UNT 036 in RCW,Reach-1,6
Up Type=0
Dn Type=3
Dn Slope=0.005
Boundary for River Rch & Prof#=UNT 036 in RCW,Reach-1,7
Up Type=0
Dn Type=3
Dn Slope=0.005

--- UNT 036 in RCW.g01 (geometry) ---

Geom Title=Existing Conditions

River Reach=UNT 036 in RCW,Reach-1
Reach XY= 30
      2029650.80     13435894.54      2029620.80     13435974.54
      2029550.80     13436014.54      2029480.80     13436014.54
      2029440.80     13435984.54      2029400.80     13435984.54
      2029370.80     13436014.54      2029360.80     13436214.54
      2029380.80     13436234.54      2029410.80     13436604.54
      2029350.80     13436674.54      2029350.80     13436704.54
      2029480.80     13436874.54      2029500.80     13436934.54
      2029490.80     13437104.54      2029720.80     13437344.54
      2029740.80     13437684.54      2029790.80     13437734.54
      2029870.80     13437894.54      2029920.80     13438064.54
      2029920.80     13438294.54      2029880.80     13438434.54
      2029970.80     13438494.54      2030070.80     13438504.54
      2030260.80     13438644.54      2030390.80     13438874.54
      2030390.80     13438974.54      2030320.80     13439114.54
      2030330.80     13439174.54      2030380.80     13439234.54

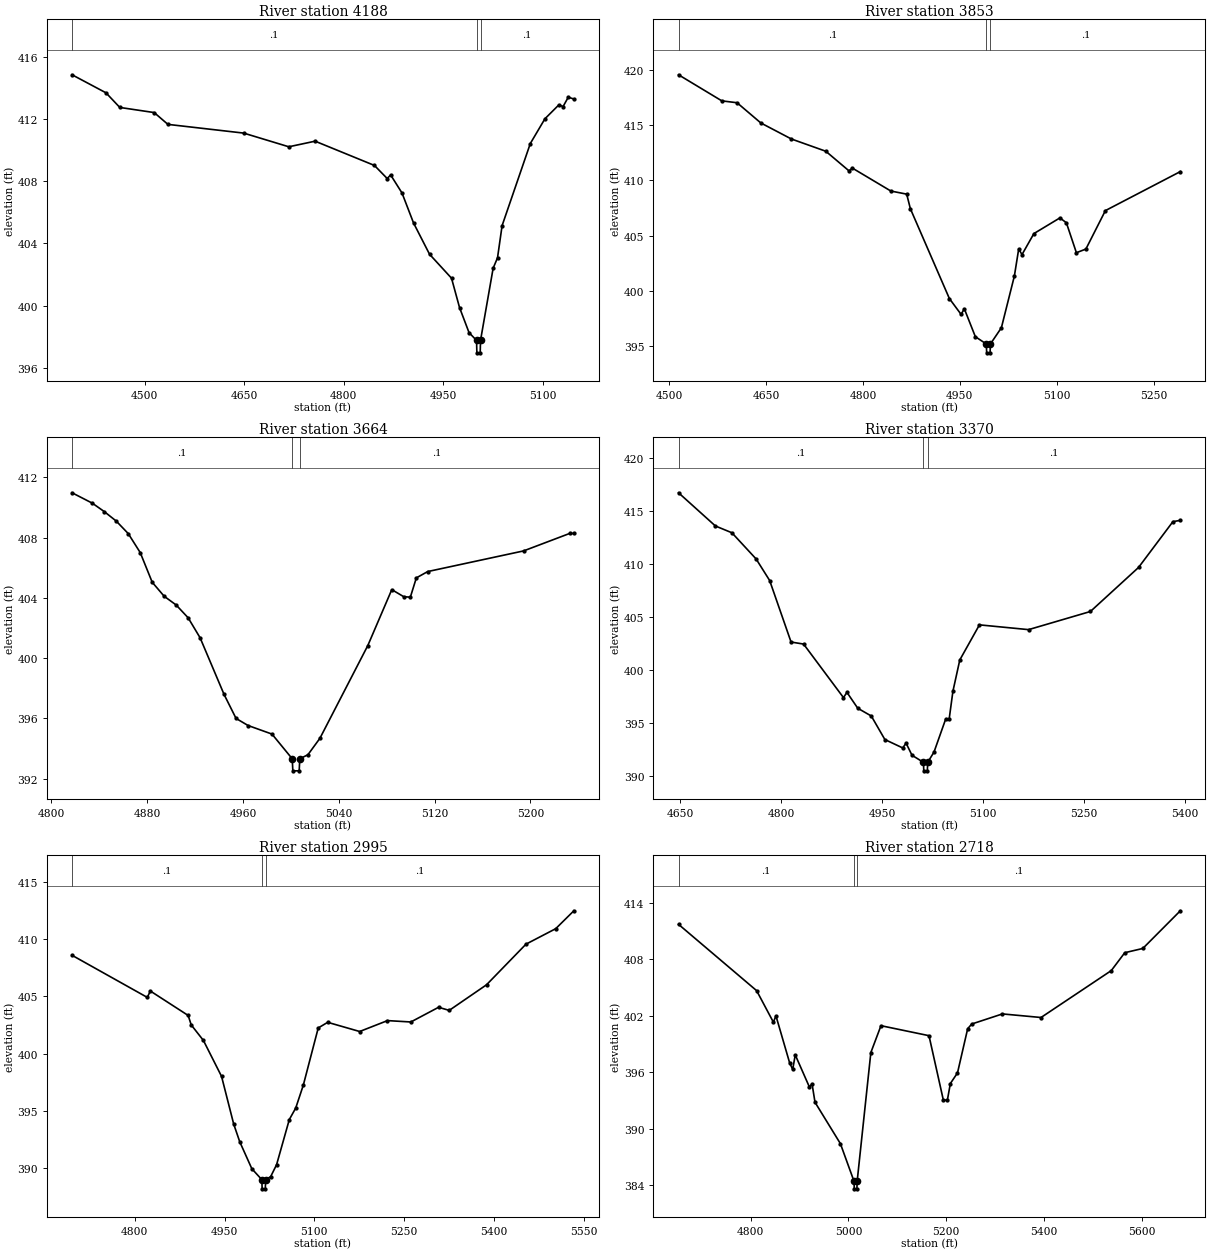
Type RM Length L Ch R = 1,4188,335,335,335
BEGIN DESCRIPTION:
UNT 036 in RCW 8.0
END DESCRIPTION:
XS GIS Cut Line= 3
      2029433.55     13435405.69      2029583.50     13435952.89
      2029727.62     13436074.44
#Sta/Elev= 30
  4390.8  414.84  4441.9  413.68  4462.7  412.74  4514.5  412.41  4535.2  411.65
  4649.3  411.09  4717.3  410.21  4756.9  410.57  4846.3  409.01  4865.5  408.17
  4870.7  408.40  4887.8  407.24  4905.2  405.31  4929.3  403.30  4962.4  401.76
  4974.5  399.87  4988.8  398.26  5000.1  397.76  5000.6  396.96  5005.6  396.96
  5006.1  397.76  5025.1  402.40  5031.7  403.07  5038.6  405.14  5081.1  410.42
  5103.1  412.01  5124.0  412.90  5130.5  412.80  5138.3  413.40  5146.7  413.28
#Mann=3,-1,0
  4390.8     0.1       0  5000.1    0.07       0  5006.1     0.1       0
Bank Sta=5000.1,5006.1
Exp/Cntr=0.3,0.1

Type RM Length L Ch R = 1,3853,189,189,189
BEGIN DESCRIPTION:
Mapping XS f63c4e6d
END DESCRIPTION:
XS GIS Cut Line= 2
      2028888.45     13436009.88      2029660.21     13436098.28
#Sta/Elev= 30
  4514.5  419.56  4581.5  417.20  4605.1  417.03  4641.9  415.20  4689.2  413.75
  4742.5  412.64  4778.5  410.86  4783.5  411.12  4843.2  409.04  4867.7  408.76
  4873.4  407.44  4933.8  399.31  4951.9  397.88  4956.9  398.39  4974.0  395.86
  4991.0  395.20  4991.5  394.40  4996.8  394.40  4997.3  395.20  5014.3  396.67
  5034.4  401.35  5041.1  403.80  5046.2  403.29  5064.6  405.19  5104.9  406.61
  5114.9  406.17  5130.4  403.46  5145.1  403.79  5175.3  407.27  5291.3  410.80
#Mann=3,-1,0
  4514.5     0.1       0  4991.0    0.07       0  4997.3     0.1       0
Bank Sta=4991,4997.3
Exp/Cntr=0.3,0.1

Type RM Length L Ch R = 1,3664,294,294,294
BEGIN DESCRIPTION:
Mapping XS 4f23f545
END DESCRIPTION:
XS GIS Cut Line= 2
      2029198.14     13436245.86      2029616.95     13436237.18
#Sta/Elev= 30
  4817.3  410.97  4834.2  410.28  4844.2  409.72  4854.2  409.09  4864.2  408.26
  4874.2  407.00  4884.2  405.03  4894.2  404.10  4904.2  403.52  4914.2  402.67
  4924.2  401.34  4944.2  397.58  4954.2  395.99  4964.2  395.52  4984.2  394.95
  5001.1  393.31  5001.6  392.51  5006.9  392.51  5007.4  393.31  5014.2  393.58
  5024.2  394.67  5064.2  400.83  5084.2  404.54  5094.2  404.07  5099.7  404.04
  5104.7  405.32  5114.2  405.74  5194.2  407.11  5232.7  408.27  5236.2  408.27
#Mann=3,-1,0
  4817.3     0.1       0  5001.1    0.07       0  5007.4     0.1       0
Bank Sta=5001.1,5007.4
Exp/Cntr=0.3,0.1

Type RM Length L Ch R = 1,3370,375,375,375
BEGIN DESCRIPTION:
UNT 036 in RCW 7.0
END DESCRIPTION:
XS GIS Cut Line= 3
      2029050.53     13436569.21      2029425.00     13436525.00
      2029785.80     13436449.94
#Sta/Elev= 30
  4647.3  416.71  4702.1  413.58  4726.6  412.94  4762.6  410.47  4782.7  408.44
  4814.5  402.64  4833.1  402.45  4892.4  397.40  4897.5  397.90  4913.6  396.40
  4933.7  395.67  4953.9  393.45  4980.4  392.66  4985.4  393.11  4994.2  391.97
  5011.2  391.30  5011.7  390.50  5017.0  390.50  5017.5  391.30  5026.9  392.27
  5044.3  395.39  5049.4  395.37  5055.0  398.00  5065.2  400.95  5094.4  404.26
  5167.4  403.81  5259.3  405.52  5330.8  409.67  5381.9  413.99  5392.9  414.11
#Mann=3,-1,0
  4647.3     0.1       0  5011.2    0.07       0  5017.5     0.1       0
Bank Sta=5011.2,5017.5
Exp/Cntr=0.3,0.1

Type RM Length L Ch R = 1,2995,277,277,277
BEGIN DESCRIPTION:
UNT 036 in RCW 6.0
END DESCRIPTION:
XS GIS Cut Line= 3
      2029148.18     13436879.54      2029471.53     13436829.63
      2029949.93     13436649.96
#Sta/Elev= 30
  4695.3  408.57  4821.0  404.90  4826.0  405.46  4889.2  403.33  4894.4  402.50
  4914.7  401.15  4945.0  398.02  4965.3  393.86  4975.4  392.32  4995.6  389.97
  5012.3  389.02  5012.8  388.22  5018.1  388.22  5018.6  389.02  5027.0  389.28
  5036.9  390.32  5058.2  394.26  5068.9  395.26  5081.6  397.26  5106.5  402.24
  5122.3  402.73  5175.7  401.93  5222.2  402.88  5261.2  402.76  5307.5  404.04
  5325.3  403.77  5387.6  406.00  5453.5  409.54  5503.2  410.89  5533.5  412.45
#Mann=3,-1,0
  4695.3     0.1       0  5012.3    0.07       0  5018.6     0.1       0
Bank Sta=5012.3,5018.6
Exp/Cntr=0.3,0.1

Type RM Length L Ch R = 1,2718,247,247,247
BEGIN DESCRIPTION:
Mapping XS 38e59988
END DESCRIPTION:
XS GIS Cut Line= 3
      2029145.97     13437172.52      2029553.99     13437059.66
      2030035.76     13436697.25
#Sta/Elev= 30
  4652.6  411.69  4812.3  404.65  4846.6  401.30  4851.8  401.98  4879.9  396.97
  4886.1  396.29  4891.3  397.83  4920.4  394.40  4925.6  394.77  4931.7  392.80
  4983.6  388.41  5011.5  384.41  5012.0  383.61  5017.4  383.61  5017.9  384.41
  5045.9  398.08  5066.6  400.93  5164.8  399.87  5194.0  393.07  5202.3  393.00
  5208.5  394.79  5223.1  395.92  5243.9  400.61  5252.3  401.11  5315.0  402.18
  5393.9  401.80  5537.6  406.78  5565.2  408.68  5602.1  409.13  5678.8  413.13
#Mann=3,-1,0
  4652.6     0.1       0  5011.5    0.07       0  5017.9     0.1       0
Bank Sta=5011.5,5017.9
Exp/Cntr=0.3,0.1

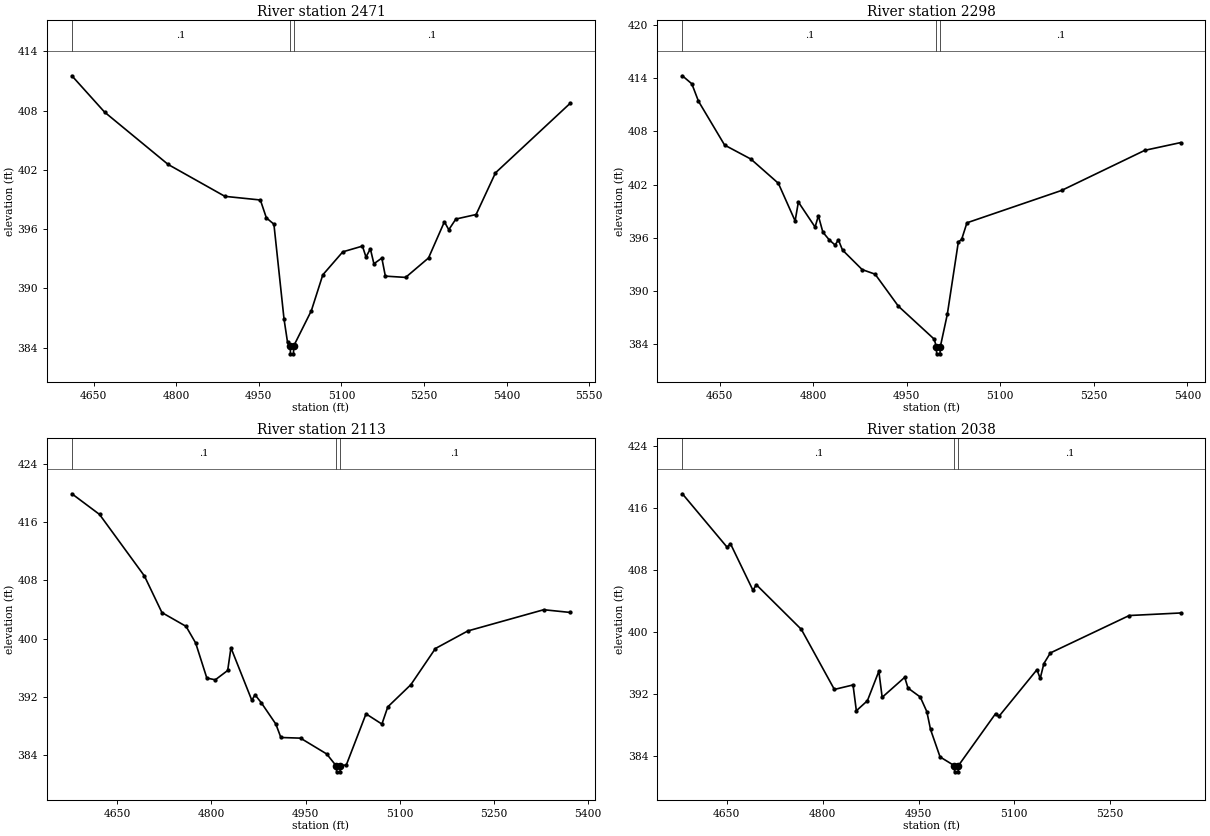
Type RM Length L Ch R = 1,2471,173,173,173
BEGIN DESCRIPTION:
UNT 036 in RCW 5.0
END DESCRIPTION:
XS GIS Cut Line= 3
      2029278.38     13437385.19      2029625.00     13437275.00
      2030046.59     13436935.98
#Sta/Elev= 30
  4610.5  411.53  4669.9  407.85  4785.3  402.55  4888.4  399.32  4952.8  398.95
  4963.7  397.14  4977.4  396.50  4995.8  386.88  5002.2  384.52  5007.0  384.17
  5007.5  383.37  5012.9  383.37  5013.4  384.17  5045.4  387.74  5066.2  391.37
  5102.5  393.70  5138.2  394.28  5144.6  393.18  5152.6  394.00  5159.0  392.49
  5173.4  393.07  5179.8  391.24  5216.6  391.11  5258.2  393.08  5287.0  396.74
  5295.0  395.94  5307.8  397.02  5344.6  397.48  5379.8  401.70  5515.2  408.73
#Mann=3,-1,0
  4610.5     0.1       0  5007.0    0.07       0  5013.4     0.1       0
Bank Sta=5007,5013.4
Exp/Cntr=0.3,0.1

Type RM Length L Ch R = 1,2298,185,185,185
BEGIN DESCRIPTION:
Mapping XS a90d103f
END DESCRIPTION:
XS GIS Cut Line= 2
      2029330.43     13437526.26      2030091.08     13437281.37
#Sta/Elev= 30
  4589.9  414.30  4605.1  413.39  4615.7  411.43  4657.7  406.46  4699.8  404.88
  4743.9  402.14  4770.8  397.88  4776.0  400.02  4802.8  397.19  4808.1  398.46
  4815.3  396.61  4825.8  395.72  4834.9  395.16  4840.2  395.74  4846.8  394.59
  4878.3  392.38  4899.1  391.86  4936.4  388.24  4993.9  384.51  4997.3  383.65
  4997.8  382.85  5003.2  382.85  5003.7  383.65  5014.9  387.31  5032.6  395.50
  5037.9  395.79  5046.4  397.67  5198.2  401.33  5331.8  405.87  5389.0  406.74
#Mann=3,-1,0
  4589.9     0.1       0  4997.3    0.07       0  5003.7     0.1       0
Bank Sta=4997.3,5003.7
Exp/Cntr=0.3,0.1

Type RM Length L Ch R = 1,2113,75,75,75
BEGIN DESCRIPTION:
Mapping XS b98dd1d6
END DESCRIPTION:
XS GIS Cut Line= 3
      2029326.10     13437702.03      2029799.22     13437560.97
      2030096.54     13437524.07
#Sta/Elev= 30
  4577.7  419.87  4621.7  417.04  4693.2  408.60  4721.1  403.58  4759.5  401.69
  4774.8  399.41  4792.6  394.60  4806.1  394.36  4825.8  395.64  4831.0  398.75
  4864.2  391.56  4869.4  392.30  4879.2  391.23  4902.5  388.29  4910.5  386.45
  4941.8  386.36  4983.5  384.19  4998.8  382.54  4999.3  381.74  5004.7  381.74
  5005.2  382.54  5014.8  382.70  5046.1  389.69  5071.4  388.29  5080.8  390.65
  5117.5  393.69  5156.6  398.65  5208.2  401.06  5329.1  403.97  5371.0  403.60
#Mann=3,-1,0
  4577.7     0.1       0  4998.8    0.07       0  5005.2     0.1       0
Bank Sta=4998.8,5005.2
Exp/Cntr=0.3,0.1

Type RM Length L Ch R = 1,2038,0,0,0
BEGIN DESCRIPTION:
UNT 036 in RCW 4.0
END DESCRIPTION:
XS GIS Cut Line= 3
      2029334.85     13437758.44      2029757.98     13437647.77
      2030096.56     13437597.85
#Sta/Elev= 30
  4580.4  417.86  4650.5  410.94  4655.7  411.40  4690.9  405.37  4696.1  406.10
  4766.6  400.32  4818.3  392.55  4847.5  393.13  4852.7  389.79  4870.0  391.09
  4887.9  394.90  4893.1  391.53  4928.4  394.12  4933.5  392.73  4952.7  391.57
  4963.0  389.68  4968.8  387.37  4983.7  383.82  5006.0  382.69  5006.5  381.89
  5011.9  381.89  5012.4  382.69  5070.7  389.43  5075.7  389.05  5135.3  395.10
  5140.4  393.97  5146.2  395.90  5156.3  397.27  5279.7  402.11  5360.0  402.44
#Mann=3,-1,0
  4580.4     0.1       0  5006.0    0.07       0  5012.4     0.1       0
Bank Sta=5006,5012.4
Exp/Cntr=0.3,0.1

Chan Stop Cuts=-1