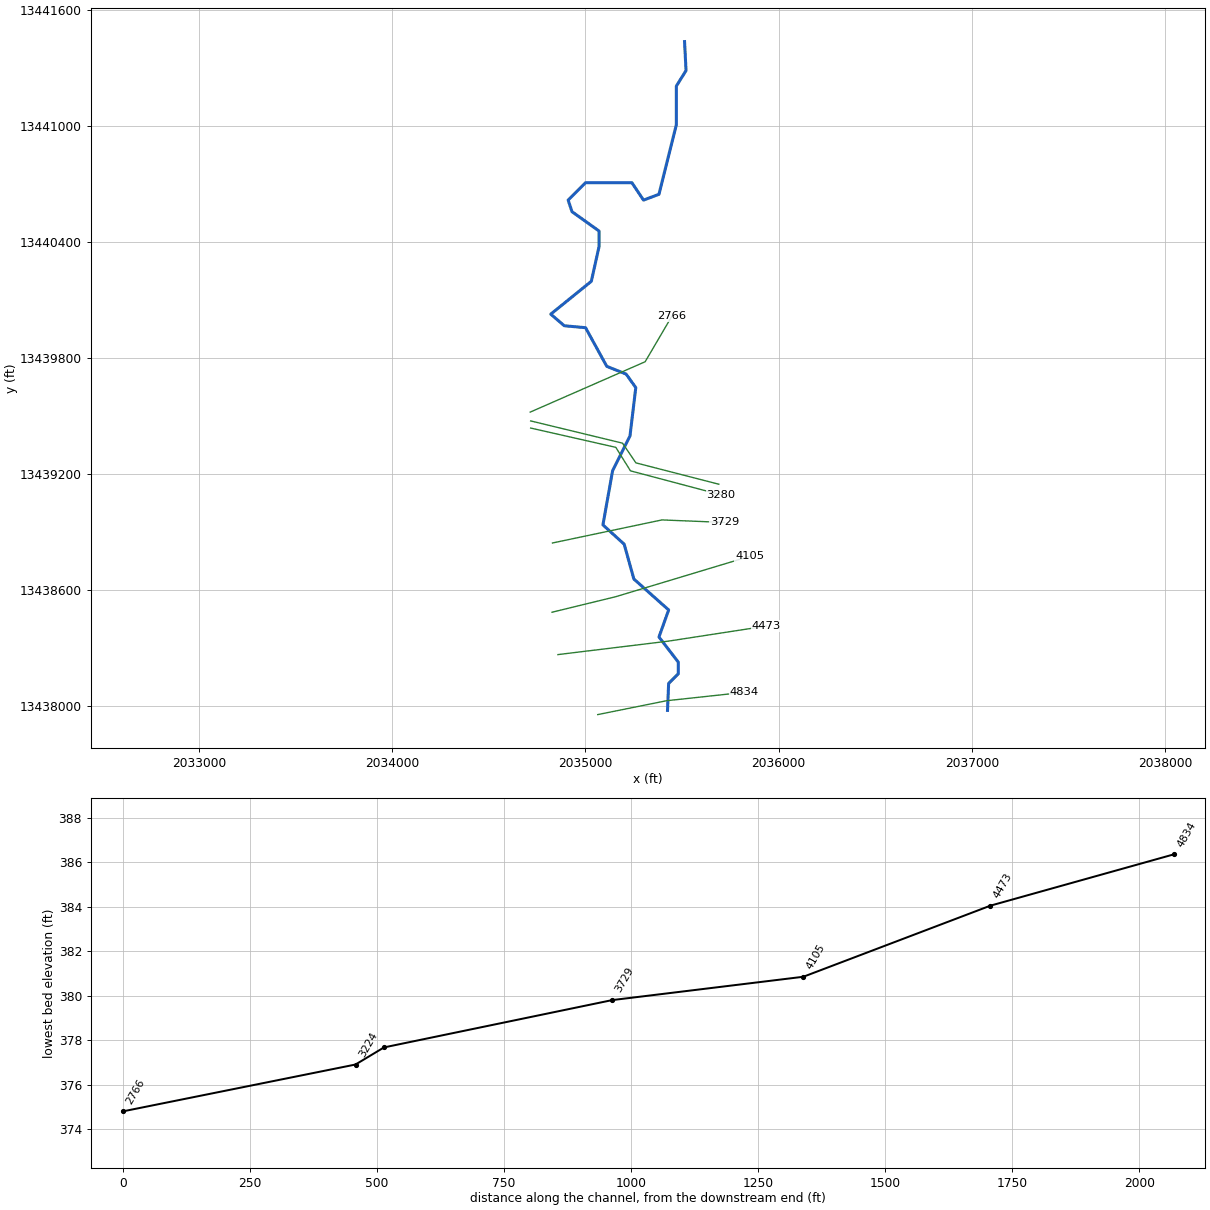
--- UNT 038 in RCW.prj (project) ---

Proj Title=UNT 038 in RCW Base Level Engineering
Current Plan=p01
Default Exp/Contr=0.3,0.1
English Units
Geom File=g01
Flow File=f01
Plan File=p01
BEGIN DESCRIPTION:
UNT 038 in RCW
END DESCRIPTION:

--- UNT 038 in RCW.p01 (plan) ---

Plan Title=Multiple Run
Short Identifier=Multiple
Geom File=g01
Flow File=f01
Subcritical Flow
K Sum by GR= 0
Std Step Tol= 0.01
Critical Tol= 0.01
Num of Std Step Trials= 20
Max Error Tol= 0.3
Flow Tol Ratio= 0.001
Split Flow NTrial= 30
Split Flow Tol= 0.02
Split Flow Ratio= 0.02
Log Output Level= 0
Friction Slope Method= 1
Unsteady Friction Slope Method= 2
Unsteady Bridges Friction Slope Method= 1
Parabolic Critical Depth
Global Vel Dist=  1 , 1 , 1
Global Log Level= 0
CheckData=True
Encroach Param= -1, 0, 0, 0
BEGIN DESCRIPTION:
Multiple Run
END DESCRIPTION:

--- UNT 038 in RCW.f01 (steady flow) ---

Flow Title=Multiple
Number of Profiles=7
Profile Names=10-year,25-year,50-year,1pct_min,100-year,1pct_plu,500-year
River Rch & RM= UNT 038 in RCW,Reach-1,4834
     173     237     290     177     353     705     532
River Rch & RM= UNT 038 in RCW,Reach-1,4473
     197     271     331     202     404     805     609
Boundary for River Rch & Prof#=UNT 038 in RCW,Reach-1,1
Up Type=0
Dn Type=3
Dn Slope=0.005
Boundary for River Rch & Prof#=UNT 038 in RCW,Reach-1,2
Up Type=0
Dn Type=3
Dn Slope=0.005
Boundary for River Rch & Prof#=UNT 038 in RCW,Reach-1,3
Up Type=0
Dn Type=3
Dn Slope=0.005
Boundary for River Rch & Prof#=UNT 038 in RCW,Reach-1,4
Up Type=0
Dn Type=3
Dn Slope=0.005
Boundary for River Rch & Prof#=UNT 038 in RCW,Reach-1,5
Up Type=0
Dn Type=3
Dn Slope=0.005
Boundary for River Rch & Prof#=UNT 038 in RCW,Reach-1,6
Up Type=0
Dn Type=3
Dn Slope=0.005
Boundary for River Rch & Prof#=UNT 038 in RCW,Reach-1,7
Up Type=0
Dn Type=3
Dn Slope=0.005

--- UNT 038 in RCW.g01 (geometry) ---

Geom Title=Existing Conditions

River Reach=UNT 038 in RCW,Reach-1
Reach XY= 30
      2035425.00     13437975.00      2035430.80     13438114.54
      2035480.80     13438164.54      2035480.80     13438224.54
      2035380.80     13438354.54      2035430.80     13438494.54
      2035250.80     13438654.54      2035200.80     13438834.54
      2035090.80     13438934.54      2035140.80     13439214.54
      2035230.80     13439394.54      2035260.80     13439644.54
      2035210.80     13439714.54      2035110.80     13439754.54
      2035000.80     13439954.54      2034890.80     13439964.54
      2034820.80     13440024.54      2035030.80     13440194.54
      2035070.80     13440374.54      2035070.80     13440454.54
      2034930.80     13440554.54      2034910.80     13440614.54
      2035000.80     13440704.54      2035240.80     13440704.54
      2035300.80     13440614.54      2035380.80     13440644.54
      2035470.80     13441004.54      2035470.80     13441204.54
      2035520.80     13441284.54      2035513.15     13441434.54

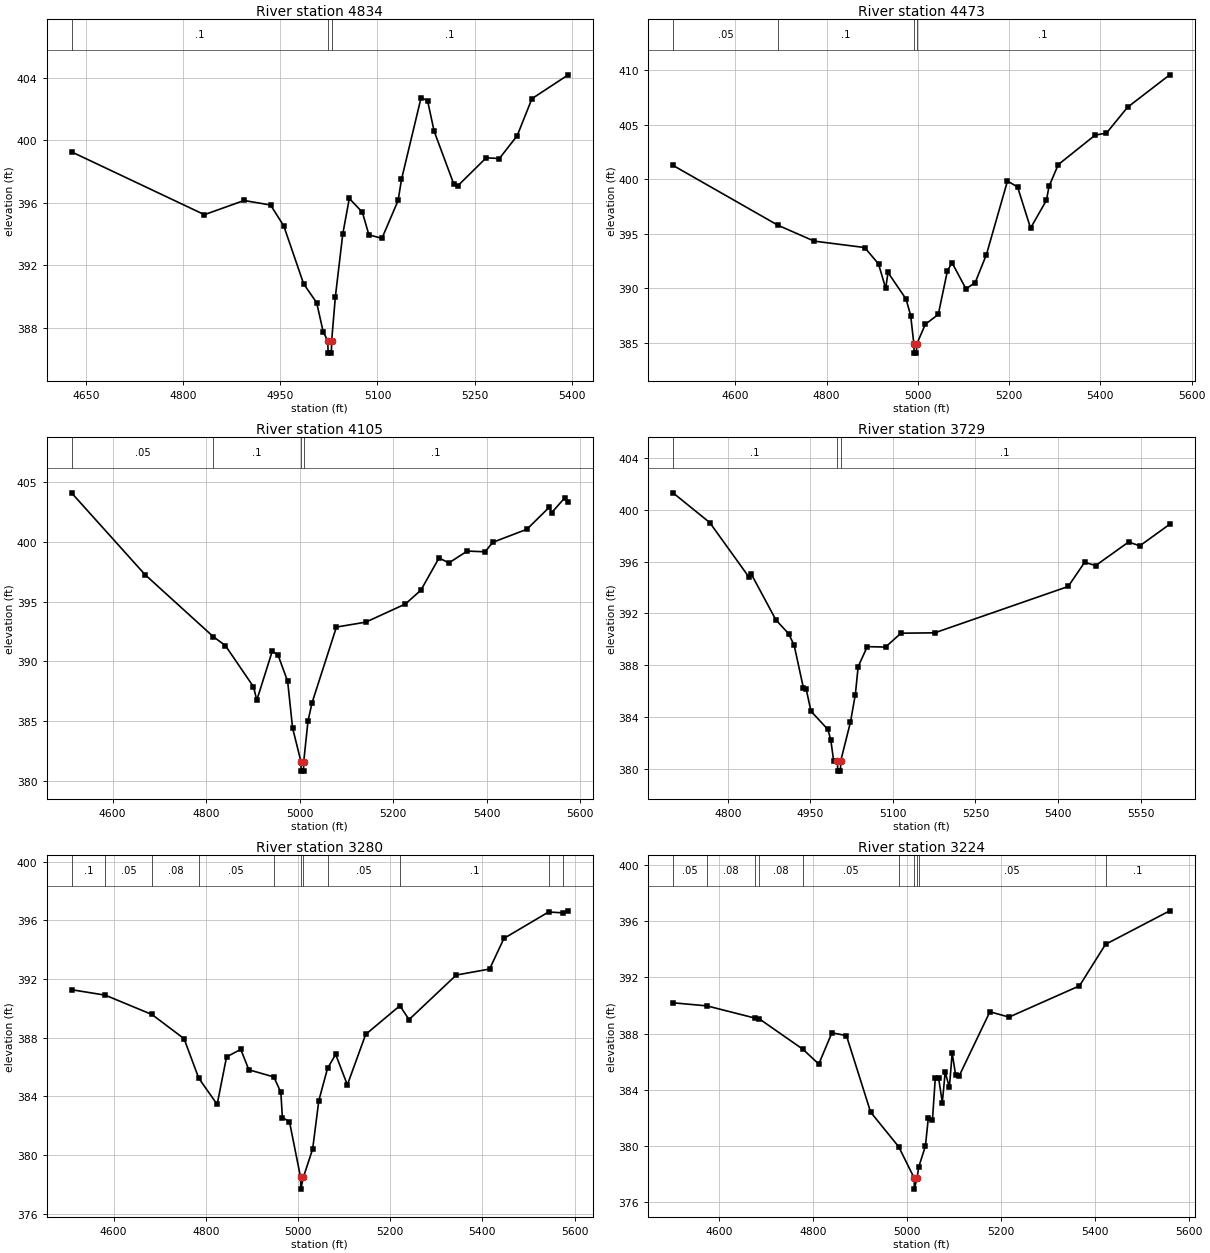
Type RM Length L Ch R = 1,4834,361,361,361
BEGIN DESCRIPTION:
UNT 038 in RCW 10.0
END DESCRIPTION:
XS GIS Cut Line= 3
      2035063.99     13437953.27      2035419.91     13438024.88
      2035820.72     13438068.22
#Sta/Elev= 30
  4628.1  399.27  4833.1  395.24  4894.3  396.15  4935.1  395.86  4955.5  394.52
  4986.1  390.81  5006.3  389.59  5016.4  387.71  5023.4  387.16  5023.9  386.36
  5028.9  386.36  5029.4  387.16  5035.1  389.98  5046.6  394.02  5056.6  396.28
  5076.7  395.40  5086.8  393.95  5106.9  393.72  5131.9  396.15  5137.1  397.50
  5167.3  402.74  5177.3  402.56  5187.4  400.60  5217.6  397.22  5223.7  397.08
  5267.8  398.89  5288.0  398.84  5315.5  400.30  5338.3  402.68  5394.3  404.21
#Mann=3,-1,0
  4628.1     0.1       0  5023.4    0.07       0  5029.4     0.1       0
Bank Sta=5023.4,5029.4
Exp/Cntr=0.3,0.1

Type RM Length L Ch R = 1,4473,368,368,368
BEGIN DESCRIPTION:
UNT 038 in RCW 9.0
END DESCRIPTION:
XS GIS Cut Line= 3
      2034857.83     13438263.60      2035428.59     13438333.04
      2035936.44     13438411.18
#Sta/Elev= 30
  4463.1  401.28  4693.0  395.79  4772.5  394.33  4883.3  393.74  4913.6  392.24
  4929.4  389.99  4934.4  391.45  4974.0  389.01  4984.1  387.50  4991.2  384.85
  4991.7  384.05  4996.7  384.05  4997.2  384.85  5016.1  386.69  5044.6  387.60
  5064.8  391.63  5074.9  392.34  5105.3  389.95  5125.5  390.52  5150.2  393.10
  5196.3  399.85  5218.5  399.29  5246.9  395.52  5281.7  398.08  5287.4  399.36
  5307.6  401.35  5388.6  404.06  5413.2  404.24  5459.4  406.61  5551.9  409.59
#Mann=4,-1,0
  4463.1    0.05       0  4693.0     0.1       0  4991.2    0.07       0
  4997.2     0.1       0
Bank Sta=4991.2,4997.2
Exp/Cntr=0.3,0.1

Type RM Length L Ch R = 1,4105,376,376,376
BEGIN DESCRIPTION:
UNT 038 in RCW 8.0
END DESCRIPTION:
XS GIS Cut Line= 3
      2034827.51     13438482.79      2035157.32     13438563.08
      2035849.61     13438771.42
#Sta/Elev= 30
  4512.1  404.07  4669.2  397.25  4815.0  392.08  4841.3  391.32  4901.3  387.89
  4908.4  386.77  4941.4  390.85  4953.6  390.56  4974.4  388.34  4984.9  384.46
  5002.8  381.65  5003.3  380.85  5008.3  380.85  5008.8  381.65  5017.9  385.03
  5026.7  386.57  5078.7  392.87  5141.5  393.28  5226.4  394.80  5259.4  395.95
  5298.2  398.64  5319.1  398.22  5358.5  399.21  5396.7  399.15  5413.0  399.94
  5486.1  401.03  5534.0  402.87  5539.2  402.42  5567.0  403.65  5574.5  403.32
#Mann=4,-1,0
  4512.1    0.05       0  4815.0     0.1       0  5002.8    0.07       0
  5008.8     0.1       0
Bank Sta=5002.8,5008.8
Exp/Cntr=0.3,0.1

Type RM Length L Ch R = 1,3729,449,449,449
BEGIN DESCRIPTION:
UNT 038 in RCW 7.0
END DESCRIPTION:
XS GIS Cut Line= 3
      2034829.65     13438840.86      2035396.03     13438960.21
      2035719.35     13438947.19
#Sta/Elev= 30
  4700.5  401.31  4767.3  399.01  4837.8  394.84  4842.9  395.02  4887.6  391.48
  4910.4  390.43  4920.6  389.54  4937.4  386.24  4942.5  386.14  4951.2  384.43
  4981.9  383.02  4987.2  382.21  4992.3  380.62  4999.3  380.60  4999.8  379.80
  5004.8  379.80  5005.3  380.60  5022.8  383.57  5031.8  385.72  5036.9  387.87
  5053.4  389.42  5086.7  389.39  5114.7  390.46  5176.1  390.49  5418.4  394.07
  5448.4  395.94  5468.4  395.69  5528.3  397.51  5548.5  397.21  5602.9  398.88
#Mann=3,-1,0
  4700.5     0.1       0  4999.3    0.07       0  5005.3     0.1       0
Bank Sta=4999.3,5005.3
Exp/Cntr=0.3,0.1

Type RM Length L Ch R = 1,3280,56,56,56
BEGIN DESCRIPTION:
Mapping XS effbc46a
END DESCRIPTION:
XS GIS Cut Line= 4
      2034716.80     13439435.47      2035157.32     13439335.65
      2035233.27     13439214.12      2035699.86     13439090.42
#Sta/Elev= 30
  4508.7  391.27  4581.8  390.90  4683.2  389.58  4752.9  387.93  4784.7  385.24
  4824.7  383.45  4845.1  386.69  4876.0  387.20  4893.4  385.81  4947.7  385.32
  4962.9  384.27  4966.2  382.55  4981.6  382.27  5005.7  378.47  5006.2  377.67
  5011.7  378.47  5031.9  380.41  5045.3  383.71  5064.1  385.90  5081.8  386.86
  5107.2  384.78  5146.9  388.22  5221.2  390.18  5241.0  389.23  5343.4  392.27
  5415.8  392.68  5446.9  394.77  5543.8  396.57  5576.0  396.51  5586.4  396.65
#Mann=11,-1,0
  4508.7     0.1       0  4581.8    0.05       0  4683.2    0.08       0
  4784.7    0.05       0  4947.7     0.1       0  5005.7    0.07       0
  5011.7     0.1       0  5064.1    0.05       0  5221.2     0.1       0
  5543.8    0.05       0  5576.0     0.1       0
Bank Sta=5005.7,5011.7
Exp/Cntr=0.3,0.1

Type RM Length L Ch R = 1,3224,458,458,458
BEGIN DESCRIPTION:
Mapping XS 1090ff49
END DESCRIPTION:
XS GIS Cut Line= 4
      2034716.79     13439472.36      2035192.04     13439357.35
      2035261.49     13439255.35      2035690.61     13439144.82
#Sta/Elev= 30
  4502.7  390.19  4574.9  389.97  4676.8  389.10  4685.9  389.05  4778.6  386.88
  4812.5  385.82  4840.4  388.05  4871.3  387.85  4922.7  382.39  4982.4  379.92
  5015.1  377.70  5015.6  376.90  5021.2  377.70  5025.2  378.51  5039.1  379.97
  5045.2  381.95  5054.0  381.80  5060.1  384.83  5067.1  384.84  5075.0  383.07
  5081.1  385.24  5090.0  384.16  5096.0  386.60  5103.4  385.02  5110.9  384.98
  5176.1  389.55  5216.8  389.17  5366.5  391.40  5421.8  394.36  5558.2  396.75
#Mann=10,-1,0
  4502.7    0.05       0  4574.9    0.08       0  4676.8     0.1       0
  4685.9    0.08       0  4778.6    0.05       0  4982.4     0.1       0
  5015.1    0.07       0  5021.2     0.1       0  5025.2    0.05       0
  5421.8     0.1       0
Bank Sta=5015.1,5021.2
Exp/Cntr=0.3,0.1

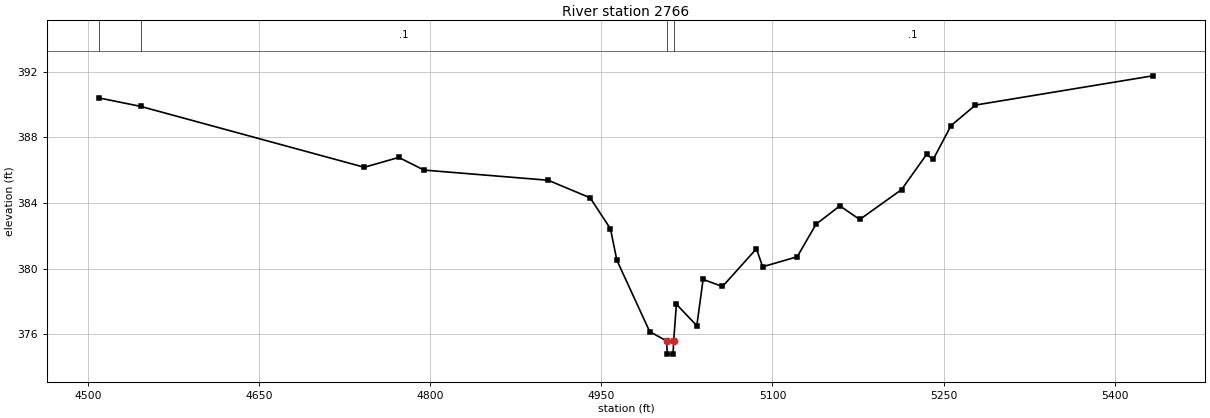
Type RM Length L Ch R = 1,2766,0,0,0
BEGIN DESCRIPTION:
UNT 038 in RCW 6.0
END DESCRIPTION:
XS GIS Cut Line= 3
      2034714.58     13439517.92      2035309.23     13439778.36
      2035448.12     13440014.91
#Sta/Elev= 30
  4509.9  390.39  4546.0  389.88  4742.2  386.17  4772.4  386.77  4794.5  386.00
  4903.4  385.38  4940.2  384.31  4958.0  382.42  4963.6  380.51  4992.4  376.16
  5007.3  375.59  5007.8  374.79  5012.9  374.79  5013.4  375.59  5015.8  377.83
  5033.7  376.52  5039.2  379.34  5056.2  378.91  5086.0  381.21  5091.4  380.11
  5121.7  380.72  5138.2  382.70  5159.1  383.82  5176.5  382.99  5213.2  384.81
  5235.1  386.95  5240.9  386.65  5256.6  388.71  5278.0  389.96  5433.4  391.74
#Mann=4,-1,0
  4509.9    0.05       0  4546.0     0.1       0  5007.3    0.07       0
  5013.4     0.1       0
Bank Sta=5007.3,5013.4
Exp/Cntr=0.3,0.1

Chan Stop Cuts=-1