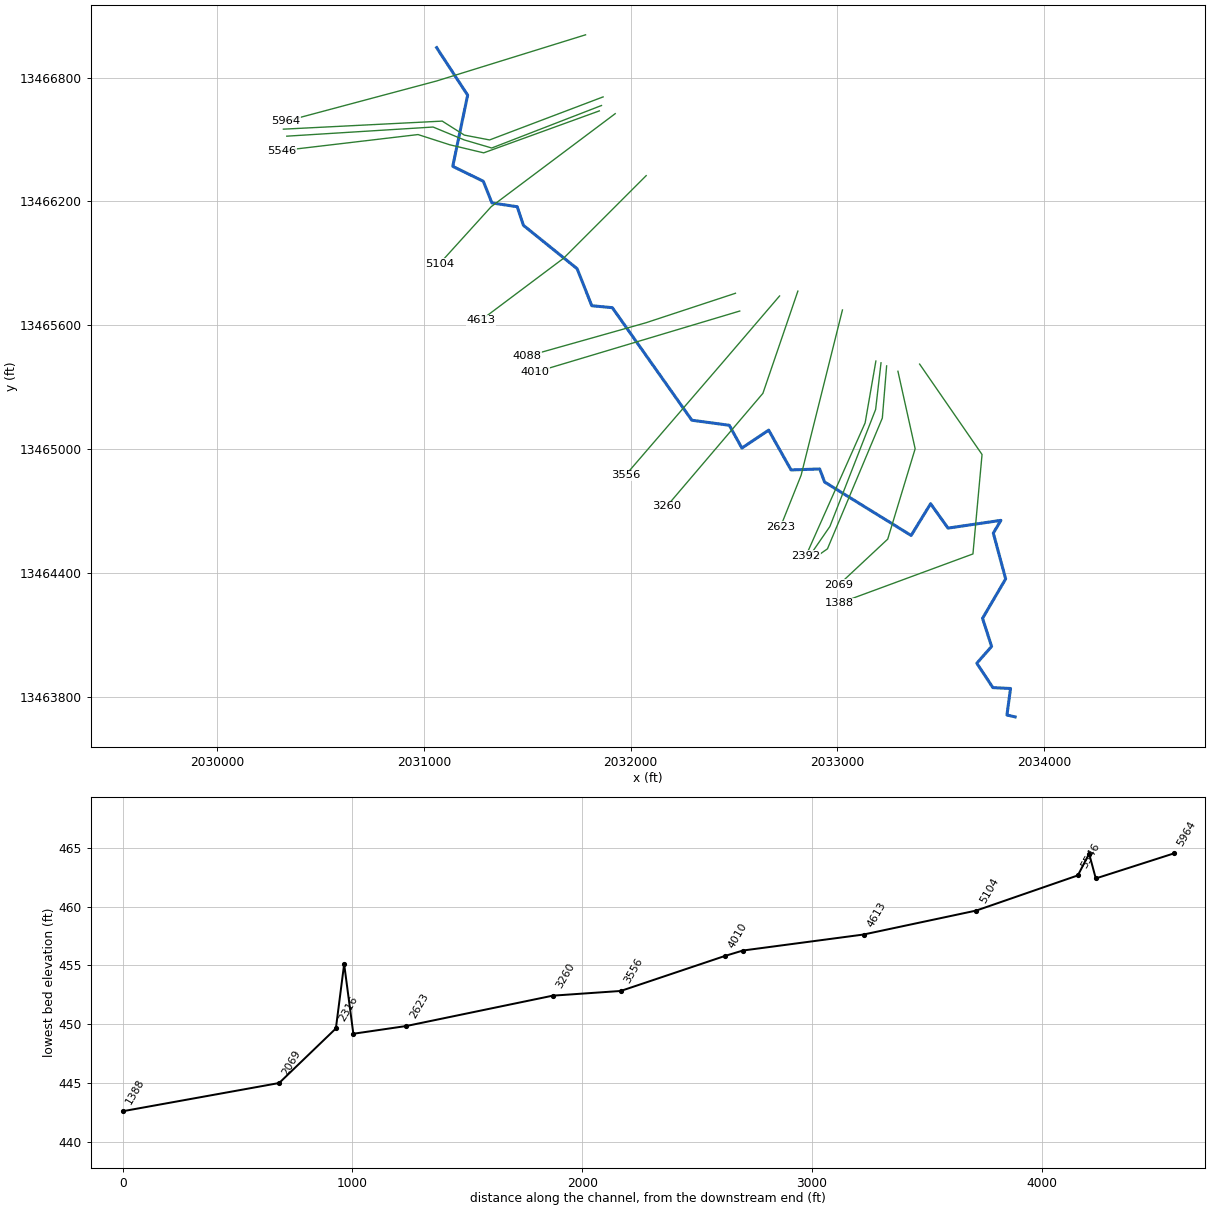
--- UNT 039 in RCW.prj (project) ---

Proj Title=UNT 039 in RCW Base Level Engineering
Current Plan=p01
Default Exp/Contr=0.3,0.1
English Units
Geom File=g01
Flow File=f01
Plan File=p01
BEGIN DESCRIPTION:
UNT 039 in RCW
END DESCRIPTION:

--- UNT 039 in RCW.p01 (plan) ---

Plan Title=Multiple Run
Short Identifier=Multiple
Geom File=g01
Flow File=f01
Subcritical Flow
K Sum by GR= 0
Std Step Tol= 0.01
Critical Tol= 0.01
Num of Std Step Trials= 20
Max Error Tol= 0.3
Flow Tol Ratio= 0.001
Split Flow NTrial= 30
Split Flow Tol= 0.02
Split Flow Ratio= 0.02
Log Output Level= 0
Friction Slope Method= 1
Unsteady Friction Slope Method= 2
Unsteady Bridges Friction Slope Method= 1
Parabolic Critical Depth
Global Vel Dist=  1 , 1 , 1
Global Log Level= 0
CheckData=True
Encroach Param= -1, 0, 0, 0
BEGIN DESCRIPTION:
Multiple Run
END DESCRIPTION:

--- UNT 039 in RCW.f01 (steady flow) ---

Flow Title=Multiple
Number of Profiles=7
Profile Names=10-year,25-year,50-year,1pct_min,100-year,1pct_plu,500-year
River Rch & RM= UNT 039 in RCW,Reach-1,5964
     167     227     276     167     334     666     496
River Rch & RM= UNT 039 in RCW,Reach-1,5624
     196     268     327     199     396     791     592
Boundary for River Rch & Prof#=UNT 039 in RCW,Reach-1,1
Up Type=0
Dn Type=3
Dn Slope=0.005
Boundary for River Rch & Prof#=UNT 039 in RCW,Reach-1,2
Up Type=0
Dn Type=3
Dn Slope=0.005
Boundary for River Rch & Prof#=UNT 039 in RCW,Reach-1,3
Up Type=0
Dn Type=3
Dn Slope=0.005
Boundary for River Rch & Prof#=UNT 039 in RCW,Reach-1,4
Up Type=0
Dn Type=3
Dn Slope=0.005
Boundary for River Rch & Prof#=UNT 039 in RCW,Reach-1,5
Up Type=0
Dn Type=3
Dn Slope=0.005
Boundary for River Rch & Prof#=UNT 039 in RCW,Reach-1,6
Up Type=0
Dn Type=3
Dn Slope=0.005
Boundary for River Rch & Prof#=UNT 039 in RCW,Reach-1,7
Up Type=0
Dn Type=3
Dn Slope=0.005

--- UNT 039 in RCW.g01 (geometry) ---

Geom Title=Existing Conditions

River Reach=UNT 039 in RCW,Reach-1
Reach XY= 30
      2031060.80     13466944.54      2031210.80     13466714.54
      2031138.71     13466370.09      2031286.62     13466297.87
      2031328.29     13466193.01      2031450.80     13466174.54
      2031480.80     13466084.54      2031740.80     13465874.54
      2031811.62     13465695.35      2031911.10     13465685.98
      2032296.00     13465141.18      2032477.25     13465116.71
      2032538.19     13465006.29      2032667.87     13465093.27
      2032776.21     13464900.56      2032914.75     13464905.25
      2032938.71     13464842.05      2033357.54     13464583.37
      2033451.73     13464737.02      2033535.93     13464618.96
      2033792.09     13464656.55      2033755.29     13464594.74
      2033815.01     13464373.22      2033703.20     13464182.24
      2033746.95     13464046.13      2033675.43     13463964.88
      2033753.20     13463846.83      2033838.62     13463842.66
      2033821.26     13463714.19      2033860.80     13463705.16

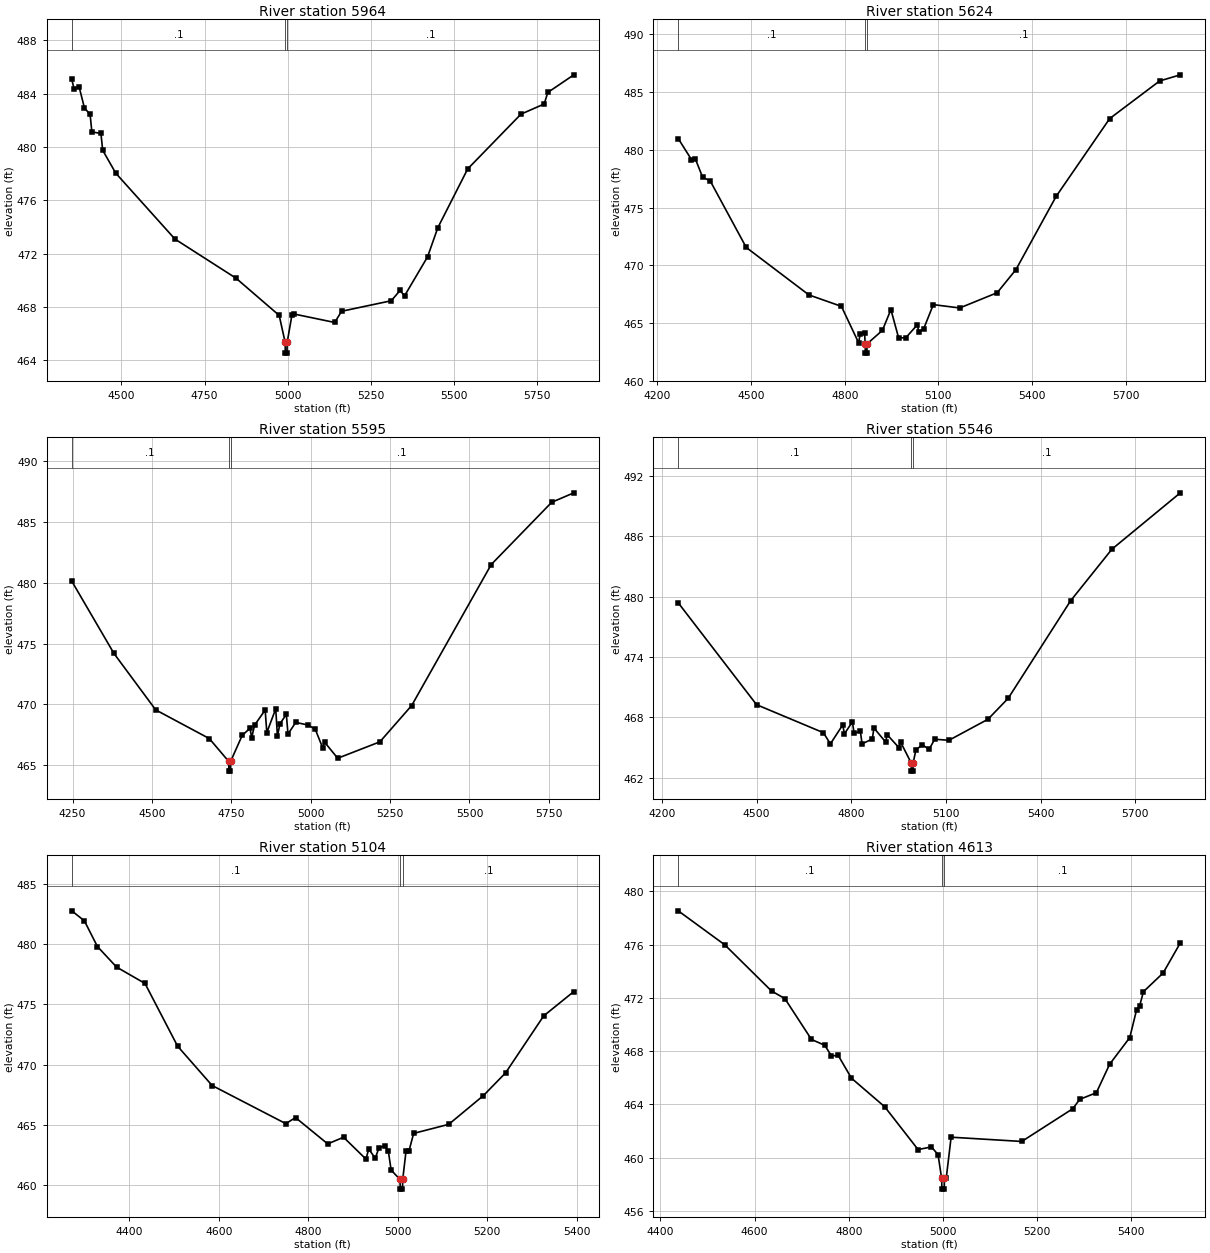
Type RM Length L Ch R = 1,5964,340,340,340
BEGIN DESCRIPTION:
UNT 039 in RCW 8.0
END DESCRIPTION:
XS GIS Cut Line= 3
      2031781.53     13467006.73      2031060.52     13466783.24
      2030329.37     13466588.09
#Sta/Elev= 30
  4350.3  485.06  4357.1  484.38  4372.9  484.46  4388.5  482.92  4405.5  482.44
  4410.8  481.13  4438.1  481.01  4443.4  479.75  4482.8  478.03  4660.8  473.09
  4844.9  470.15  4974.8  467.36  4992.8  465.33  4993.3  464.53  4998.3  464.53
  4998.8  465.33  5013.1  467.38  5018.4  467.47  5141.9  466.83  5162.6  467.67
  5312.2  468.46  5338.6  469.23  5352.2  468.83  5421.4  471.75  5452.4  473.94
  5542.3  478.35  5702.7  482.46  5772.5  483.22  5783.6  484.09  5861.9  485.41
#Mann=3,-1,0
  4350.3     0.1       0  4992.8    0.07       0  4998.8     0.1       0
Bank Sta=4992.8,4998.8
Exp/Cntr=0.3,0.1

Type RM Length L Ch R = 1,5624,29,29,29
BEGIN DESCRIPTION:
Mapping XS 4c77b7e9
END DESCRIPTION:
XS GIS Cut Line= 5
      2031866.53     13466706.21      2031317.03     13466497.87
      2031194.64     13466521.30      2031087.86     13466589.01
      2030318.97     13466550.05
#Sta/Elev= 30
  4266.6  480.98  4309.0  479.16  4321.7  479.20  4344.5  477.65  4369.3  477.30
  4484.5  471.55  4685.3  467.44  4789.4  466.45  4844.3  463.31  4849.7  464.05
  4863.5  464.17  4865.6  463.20  4866.1  462.40  4871.1  462.40  4871.6  463.20
  4920.7  464.37  4948.0  466.17  4972.7  463.72  4995.7  463.73  5032.1  464.84
  5038.0  464.23  5053.3  464.53  5083.8  466.60  5168.3  466.31  5288.4  467.63
  5348.5  469.63  5477.3  475.97  5648.9  482.71  5809.1  485.97  5875.2  486.50
#Mann=3,-1,0
  4266.6     0.1       0  4865.6    0.07       0  4871.6     0.1       0
Bank Sta=4865.6,4871.6
Exp/Cntr=0.3,0.1

Type RM Length L Ch R = 1,5595,49,49,49
BEGIN DESCRIPTION:
Mapping XS f6adbb98
END DESCRIPTION:
XS GIS Cut Line= 5
      2031858.73     13466664.54      2031327.45     13466458.80
      2031194.64     13466497.87      2031043.59     13466560.37
      2030335.30     13466516.10
#Sta/Elev= 30
  4247.5  480.14  4380.2  474.20  4511.8  469.55  4680.6  467.19  4741.8  465.31
  4742.3  464.51  4747.3  464.51  4747.8  465.31  4784.3  467.45  4808.8  468.04
  4814.2  467.26  4823.2  468.29  4856.6  469.54  4861.8  467.68  4889.9  469.64
  4895.2  467.38  4903.2  468.41  4923.3  469.18  4928.5  467.56  4952.9  468.52
  4990.3  468.31  5014.2  467.97  5038.1  466.40  5043.5  466.90  5085.1  465.57
  5217.9  466.92  5318.1  469.91  5568.6  481.51  5759.0  486.63  5828.8  487.41
#Mann=3,-1,0
  4247.5     0.1       0  4741.8    0.07       0  4747.8     0.1       0
Bank Sta=4741.8,4747.8
Exp/Cntr=0.3,0.1

Type RM Length L Ch R = 1,5546,442,442,442
BEGIN DESCRIPTION:
Mapping XS 77ae830c
END DESCRIPTION:
XS GIS Cut Line= 5
      2031848.28     13466638.49      2031288.39     13466435.37
      2031124.32     13466474.43      2030970.68     13466523.91
      2030309.64     13466445.83
#Sta/Elev= 30
  4251.8  479.40  4500.0  469.27  4712.0  466.48  4734.0  465.37  4773.2  467.26
  4778.5  466.36  4803.8  467.57  4809.1  466.43  4829.1  466.61  4834.4  465.37
  4866.9  465.86  4872.0  466.95  4909.0  465.56  4914.1  466.28  4951.2  465.00
  4956.3  465.57  4990.3  463.46  4990.8  462.66  4995.8  462.66  4996.3  463.46
  5005.1  464.79  5025.8  465.27  5046.9  464.83  5064.7  465.83  5109.9  465.73
  5233.5  467.82  5297.5  469.90  5495.3  479.60  5626.2  484.73  5843.1  490.34
#Mann=3,-1,0
  4251.8     0.1       0  4990.3    0.07       0  4996.3     0.1       0
Bank Sta=4990.3,4996.3
Exp/Cntr=0.3,0.1

Type RM Length L Ch R = 1,5104,491,491,491
BEGIN DESCRIPTION:
UNT 039 in RCW 7.0
END DESCRIPTION:
XS GIS Cut Line= 3
      2031925.04     13466625.03      2031325.00     13466175.00
      2031075.32     13465899.44
#Sta/Elev= 30
  4271.7  482.74  4299.9  481.91  4329.0  479.78  4371.7  478.08  4435.3  476.72
  4508.2  471.52  4585.3  468.26  4749.9  465.10  4771.7  465.60  4843.6  463.42
  4879.0  463.97  4929.0  462.16  4935.3  462.99  4949.9  462.23  4958.2  463.11
  4971.7  463.25  4979.0  462.84  4985.3  461.25  5005.2  460.47  5005.7  459.67
  5010.7  459.67  5011.2  460.47  5018.6  462.82  5025.1  462.82  5035.6  464.29
  5114.0  465.04  5191.7  467.43  5241.1  469.31  5326.2  474.03  5393.6  476.05
#Mann=3,-1,0
  4271.7     0.1       0  5005.2    0.07       0  5011.2     0.1       0
Bank Sta=5005.2,5011.2
Exp/Cntr=0.3,0.1

Type RM Length L Ch R = 1,4613,525,525,525
BEGIN DESCRIPTION:
UNT 039 in RCW 6.0
END DESCRIPTION:
XS GIS Cut Line= 3
      2032074.99     13466324.99      2031675.00     13465925.00
      2031274.98     13465624.98
#Sta/Elev= 30
  4438.1  478.53  4537.1  475.97  4636.1  472.51  4664.4  471.94  4720.9  468.87
  4749.2  468.43  4763.4  467.63  4777.5  467.68  4805.8  465.96  4876.5  463.81
  4947.2  460.60  4975.5  460.80  4989.6  460.22  4997.2  458.43  4997.7  457.63
  5002.7  457.63  5003.2  458.43  5006.9  458.43  5017.3  461.53  5167.3  461.21
  5275.6  463.67  5290.2  464.37  5325.6  464.87  5353.8  467.01  5396.5  469.01
  5411.1  471.11  5417.3  471.37  5425.6  472.46  5467.3  473.86  5503.8  476.12
#Mann=3,-1,0
  4438.1     0.1       0  4997.2    0.07       0  5003.2     0.1       0
Bank Sta=4997.2,5003.2
Exp/Cntr=0.3,0.1

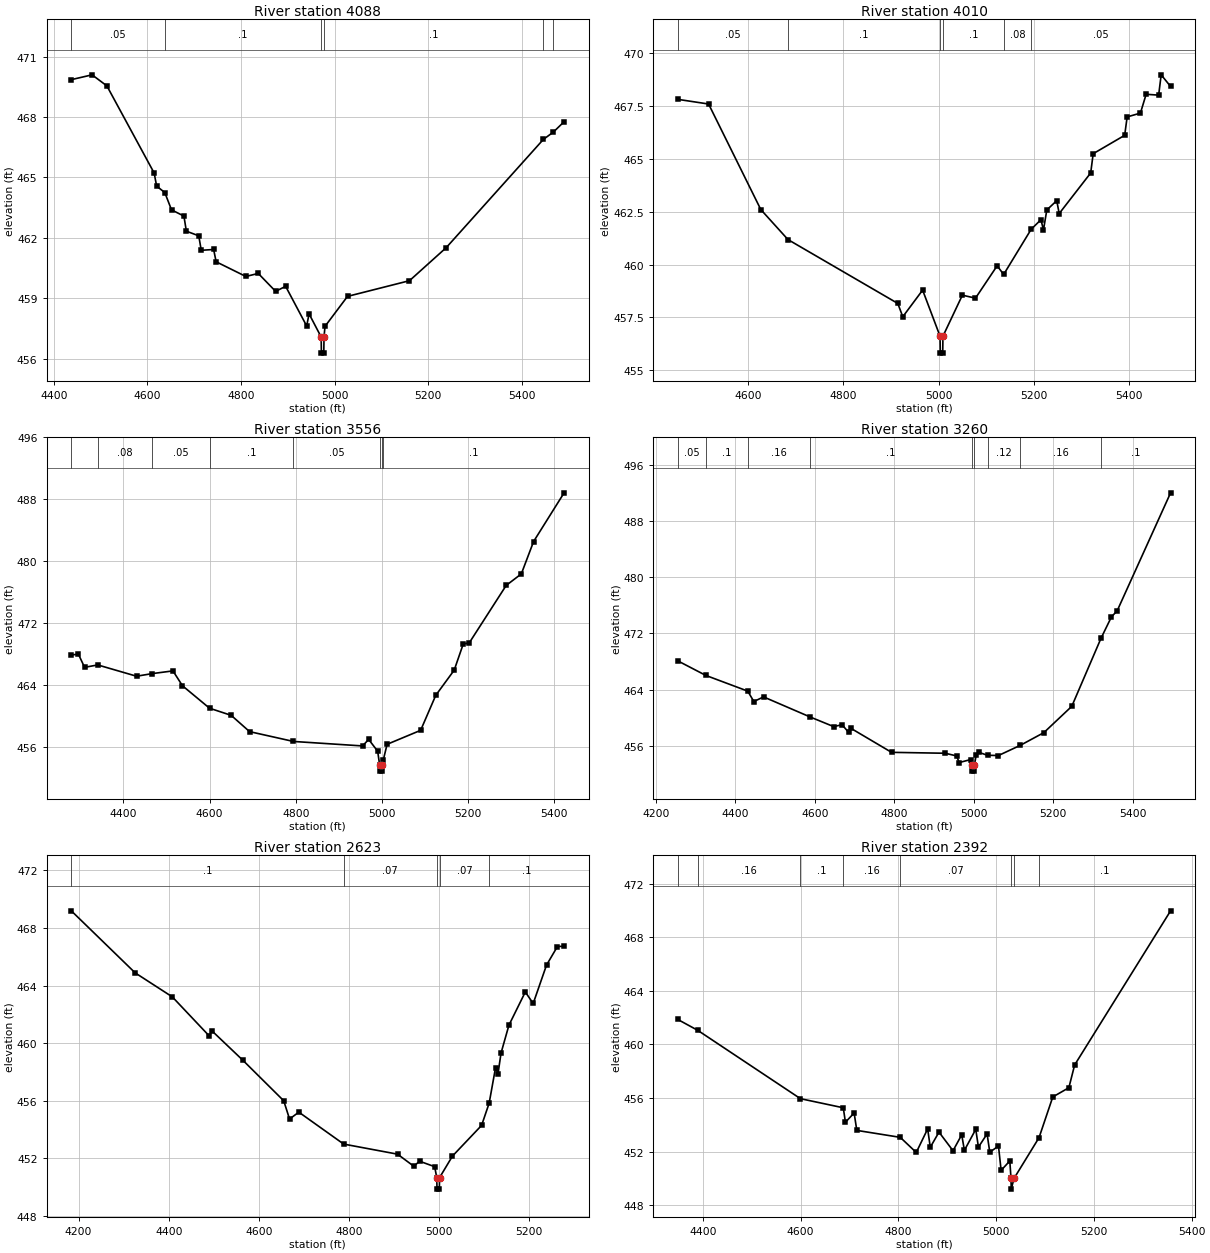
Type RM Length L Ch R = 1,4088,78,78,78
BEGIN DESCRIPTION:
UNT 039 in RCW 5.0
END DESCRIPTION:
XS GIS Cut Line= 3
      2032507.16     13465755.69      2032072.24     13465612.45
      2031499.65     13465451.08
#Sta/Elev= 30
  4437.4  469.86  4481.8  470.10  4513.4  469.55  4614.4  465.22  4619.7  464.57
  4637.1  464.25  4651.5  463.39  4678.0  463.08  4683.2  462.33  4709.7  462.10
  4715.0  461.38  4741.5  461.42  4746.8  460.81  4810.3  460.08  4836.8  460.23
  4873.9  459.34  4895.3  459.59  4940.2  457.62  4945.4  458.22  4971.2  457.07
  4971.7  456.27  4976.8  456.27  4977.3  457.07  4979.4  457.60  5027.5  459.09
  5159.9  459.87  5238.3  461.51  5445.9  466.89  5467.5  467.26  5490.2  467.77
#Mann=6,-1,0
  4437.4    0.05       0  4637.1     0.1       0  4971.2    0.07       0
  4977.3     0.1       0  5445.9    0.05       0  5467.5    0.08       0
Bank Sta=4971.2,4977.3
Exp/Cntr=0.3,0.1

Type RM Length L Ch R = 1,4010,454,454,454
BEGIN DESCRIPTION:
Mapping XS e0d7f93d
END DESCRIPTION:
XS GIS Cut Line= 2
      2032527.94     13465669.73      2031535.80     13465372.87
#Sta/Elev= 30
  4451.8  467.81  4516.5  467.59  4626.2  462.60  4683.3  461.18  4914.1  458.16
  4924.6  457.53  4966.3  458.79  5002.9  456.61  5003.4  455.81  5008.5  455.81
  5009.0  456.61  5049.8  458.55  5077.4  458.41  5122.9  459.94  5136.6  459.53
  5194.5  461.67  5215.0  462.12  5220.2  461.63  5227.3  462.58  5248.1  463.02
  5253.3  462.41  5319.5  464.33  5324.7  465.24  5390.9  466.11  5396.1  466.98
  5424.0  467.16  5436.0  468.05  5462.3  468.01  5467.6  468.97  5487.4  468.42
#Mann=6,-1,0
  4451.8    0.05       0  4683.3     0.1       0  5002.9    0.07       0
  5009.0     0.1       0  5136.6    0.08       0  5194.5    0.05       0
Bank Sta=5002.9,5009
Exp/Cntr=0.3,0.1

Type RM Length L Ch R = 1,3556,296,296,296
BEGIN DESCRIPTION:
UNT 039 in RCW 4.0
END DESCRIPTION:
XS GIS Cut Line= 3
      2032720.65     13465742.63      2032442.03     13465417.14
      2031975.01     13464875.01
#Sta/Elev= 30
  4279.0  467.86  4295.5  467.96  4309.8  466.26  4340.4  466.57  4430.5  465.11
  4467.0  465.45  4515.0  465.80  4537.0  463.88  4599.9  460.97  4650.1  460.05
  4692.9  457.94  4794.7  456.67  4955.1  456.09  4969.3  456.93  4990.2  455.41
  4994.8  453.63  4995.3  452.83  5000.4  452.83  5000.9  453.63  5003.0  454.21
  5012.1  456.30  5090.0  458.11  5125.1  462.64  5167.9  465.90  5188.8  469.27
  5203.0  469.44  5288.6  476.86  5323.7  478.35  5352.2  482.54  5423.0  488.84
#Mann=8,-1,0
  4279.0    0.05       0  4340.4    0.08       0  4467.0    0.05       0
  4599.9     0.1       0  4794.7    0.05       0  4994.8    0.04       0
  5000.9    0.05       0  5003.0     0.1       0
Bank Sta=4994.8,5000.9
Exp/Cntr=0.3,0.1

Type RM Length L Ch R = 1,3260,637,637,637
BEGIN DESCRIPTION:
UNT 039 in RCW 3.0
END DESCRIPTION:
XS GIS Cut Line= 3
      2032809.22     13465766.10      2032639.95     13465271.30
      2032175.02     13464725.02
#Sta/Elev= 30
  4255.4  468.10  4326.0  466.03  4431.4  463.80  4446.8  462.32  4471.2  462.98
  4588.7  460.12  4647.6  458.76  4668.8  459.02  4685.1  457.96  4690.3  458.54
  4793.4  455.10  4928.5  454.97  4957.1  454.59  4963.7  453.65  4992.2  454.07
  4995.7  453.23  4996.2  452.43  5001.3  452.43  5001.8  453.23  5006.5  454.79
  5013.1  455.10  5034.9  454.68  5062.5  454.65  5117.6  456.10  5176.7  457.90
  5247.0  461.64  5320.4  471.29  5346.9  474.36  5361.2  475.21  5495.7  491.98
#Mann=9,-1,0
  4255.4    0.05       0  4326.0     0.1       0  4431.4    0.16       0
  4588.7     0.1       0  4995.7    0.07       0  5001.8     0.1       0
  5034.9    0.12       0  5117.6    0.16       0  5320.4     0.1       0
Bank Sta=4995.7,5001.8
Exp/Cntr=0.3,0.1

Type RM Length L Ch R = 1,2623,231,231,231
BEGIN DESCRIPTION:
UNT 039 in RCW 2.0
END DESCRIPTION:
XS GIS Cut Line= 3
      2033024.99     13465674.96      2032825.00     13464875.00
      2032725.01     13464625.04
#Sta/Elev= 30
  4183.8  469.19  4325.5  464.88  4408.0  463.21  4490.4  460.48  4495.6  460.86
  4565.1  458.79  4655.3  455.99  4668.2  454.72  4688.8  455.20  4788.4  452.98
  4907.9  452.28  4944.0  451.44  4956.8  451.79  4990.3  451.41  4995.0  450.65
  4995.5  449.85  5000.7  449.85  5001.2  450.65  5029.9  452.15  5094.5  454.28
  5111.3  455.83  5125.5  458.30  5130.9  457.86  5137.6  459.30  5155.1  461.24
  5191.5  463.55  5209.0  462.75  5238.6  465.42  5262.8  466.71  5277.6  466.73
#Mann=5,-1,0
  4183.8     0.1       0  4788.4    0.07       0  4995.0    0.07       0
  5001.2    0.07       0  5111.3     0.1       0
Bank Sta=4995,5001.2
Exp/Cntr=0.3,0.1

Type RM Length L Ch R = 1,2392,40,40,40
BEGIN DESCRIPTION:
Mapping XS e054570e
END DESCRIPTION:
XS GIS Cut Line= 3
      2033186.82     13465427.56      2033134.74     13465128.07
      2032848.29     13464484.86
#Sta/Elev= 30
  4348.8  461.87  4389.5  461.06  4599.7  455.95  4687.3  455.27  4691.7  454.19
  4709.5  454.88  4715.0  453.58  4803.9  453.06  4836.6  451.93  4859.9  453.69
  4865.3  452.32  4883.1  453.45  4911.8  452.06  4929.6  453.25  4935.1  452.09
  4958.3  453.66  4963.8  452.33  4981.5  453.32  4987.0  451.95  5004.8  452.41
  5010.2  450.59  5028.0  451.30  5030.4  449.99  5030.9  449.19  5036.6  449.99
  5087.8  453.04  5115.9  456.08  5148.8  456.77  5160.6  458.47  5356.9  469.99
#Mann=8,-1,0
  4348.8     0.1       0  4389.5    0.16       0  4599.7     0.1       0
  4687.3    0.16       0  4803.9    0.07       0  5030.4    0.07       0
  5036.6    0.07       0  5087.8     0.1       0
Bank Sta=5030.4,5036.6
Exp/Cntr=0.3,0.1

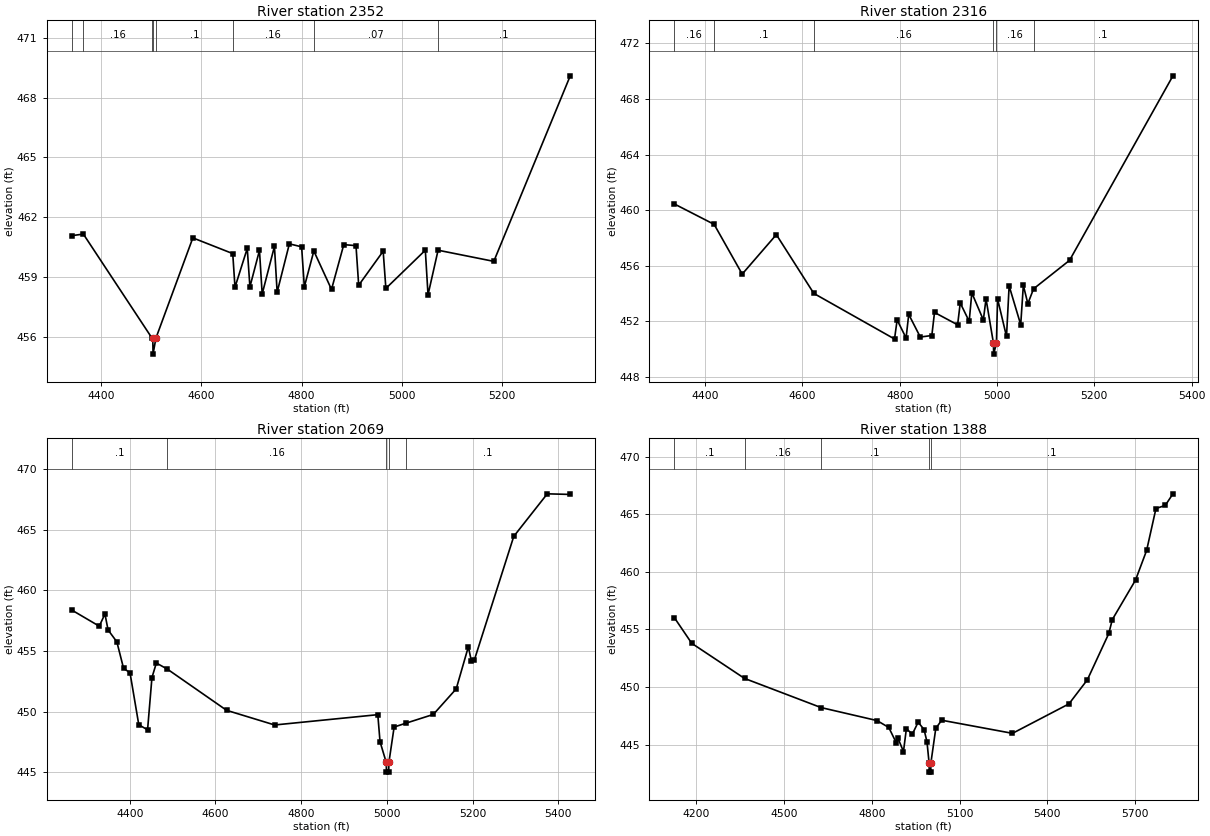
Type RM Length L Ch R = 1,2352,36,36,36
BEGIN DESCRIPTION:
Mapping XS ac2843c6
END DESCRIPTION:
XS GIS Cut Line= 4
      2033211.72     13465419.19      2033185.67     13465193.46
      2032964.32     13464627.05      2032873.16     13464494.65
#Sta/Elev= 30
  4340.7  461.07  4364.2  461.15  4500.9  455.94  4502.9  455.92  4503.4  455.12
  4509.1  455.92  4582.9  460.96  4662.6  460.17  4667.1  458.48  4691.6  460.43
  4696.9  458.50  4716.0  460.33  4721.4  458.14  4745.9  460.53  4751.3  458.23
  4775.7  460.66  4800.2  460.51  4805.6  458.50  4824.6  460.30  4859.9  458.37
  4884.4  460.62  4908.8  460.57  4914.2  458.58  4963.1  460.29  4968.5  458.42
  5047.3  460.34  5052.7  458.10  5072.8  460.34  5184.1  459.78  5336.8  469.10
#Mann=8,-1,0
  4340.7     0.1       0  4364.2    0.16       0  4500.9     0.1       0
  4502.9    0.07       0  4509.1     0.1       0  4662.6    0.16       0
  4824.6    0.07       0  5072.8     0.1       0
Bank Sta=4502.9,4509.1
Exp/Cntr=0.3,0.1

Type RM Length L Ch R = 1,2316,247,247,247
BEGIN DESCRIPTION:
Mapping XS 9d63dc64
END DESCRIPTION:
XS GIS Cut Line= 4
      2033238.90     13465404.09      2033218.07     13465151.51
      2032952.45     13464518.70      2032882.72     13464469.63
#Sta/Elev= 30
  4336.5  460.45  4418.4  458.98  4476.1  455.40  4546.3  458.24  4623.3  454.01
  4789.2  450.73  4794.6  452.10  4813.0  450.80  4818.4  452.50  4842.2  450.87
  4865.9  450.98  4871.4  452.64  4918.9  451.75  4924.3  453.32  4942.7  452.00
  4948.1  454.05  4971.8  452.10  4977.3  453.62  4992.5  450.44  4993.0  449.64
  4998.7  450.44  5001.0  453.62  5019.4  450.91  5024.8  454.55  5048.6  451.76
  5054.0  454.59  5063.3  453.27  5075.0  454.34  5149.0  456.39  5361.5  469.67
#Mann=6,-1,0
  4336.5    0.16       0  4418.4     0.1       0  4623.3    0.16       0
  4992.5    0.07       0  4998.7    0.16       0  5075.0     0.1       0
Bank Sta=4992.5,4998.7
Exp/Cntr=0.3,0.1

Type RM Length L Ch R = 1,2069,681,681,681
BEGIN DESCRIPTION:
Mapping XS 73851a82
END DESCRIPTION:
XS GIS Cut Line= 4
      2033293.60     13465378.05      2033376.93     13465003.07
      2033244.11     13464565.57      2033008.54     13464345.53
#Sta/Elev= 30
  4264.3  458.38  4328.9  457.04  4342.1  458.05  4349.4  456.73  4369.9  455.75
  4385.6  453.56  4400.6  453.20  4421.1  448.91  4441.6  448.49  4451.8  452.80
  4462.1  454.00  4487.7  453.50  4626.0  450.10  4738.2  448.89  4978.9  449.74
  4984.1  447.51  4998.6  445.80  4999.1  445.00  5004.3  445.00  5004.8  445.80
  5017.0  448.72  5043.8  449.03  5108.5  449.76  5161.9  451.87  5190.2  455.34
  5197.5  454.13  5204.4  454.27  5296.2  464.45  5374.4  467.96  5428.0  467.91
#Mann=5,-1,0
  4264.3     0.1       0  4487.7    0.16       0  4998.6    0.07       0
  5004.8    0.16       0  5043.8     0.1       0
Bank Sta=4998.6,5004.8
Exp/Cntr=0.3,0.1

Type RM Length L Ch R = 1,1388,0,0,0
BEGIN DESCRIPTION:
UNT 039 in RCW 1.0
END DESCRIPTION:
XS GIS Cut Line= 4
      2033398.64     13465412.79      2033700.71     13464975.30
      2033656.67     13464493.93      2033010.63     13464255.69
#Sta/Elev= 30
  4125.2  456.03  4184.9  453.79  4365.3  450.74  4626.5  448.21  4817.8  447.08
  4858.0  446.48  4883.6  445.15  4888.7  445.59  4908.2  444.39  4918.2  446.38
  4938.3  445.89  4958.4  446.94  4978.5  446.30  4988.5  445.24  4995.7  443.40
  4996.2  442.60  5001.4  442.60  5001.9  443.40  5018.6  446.40  5038.7  447.11
  5280.6  445.97  5473.6  448.53  5536.4  450.62  5609.8  454.65  5621.6  455.85
  5701.1  459.29  5738.9  461.86  5770.8  465.50  5802.8  465.78  5828.8  466.78
#Mann=5,-1,0
  4125.2     0.1       0  4365.3    0.16       0  4626.5     0.1       0
  4995.7    0.07       0  5001.9     0.1       0
Bank Sta=4995.7,5001.9
Exp/Cntr=0.3,0.1

Chan Stop Cuts=-1