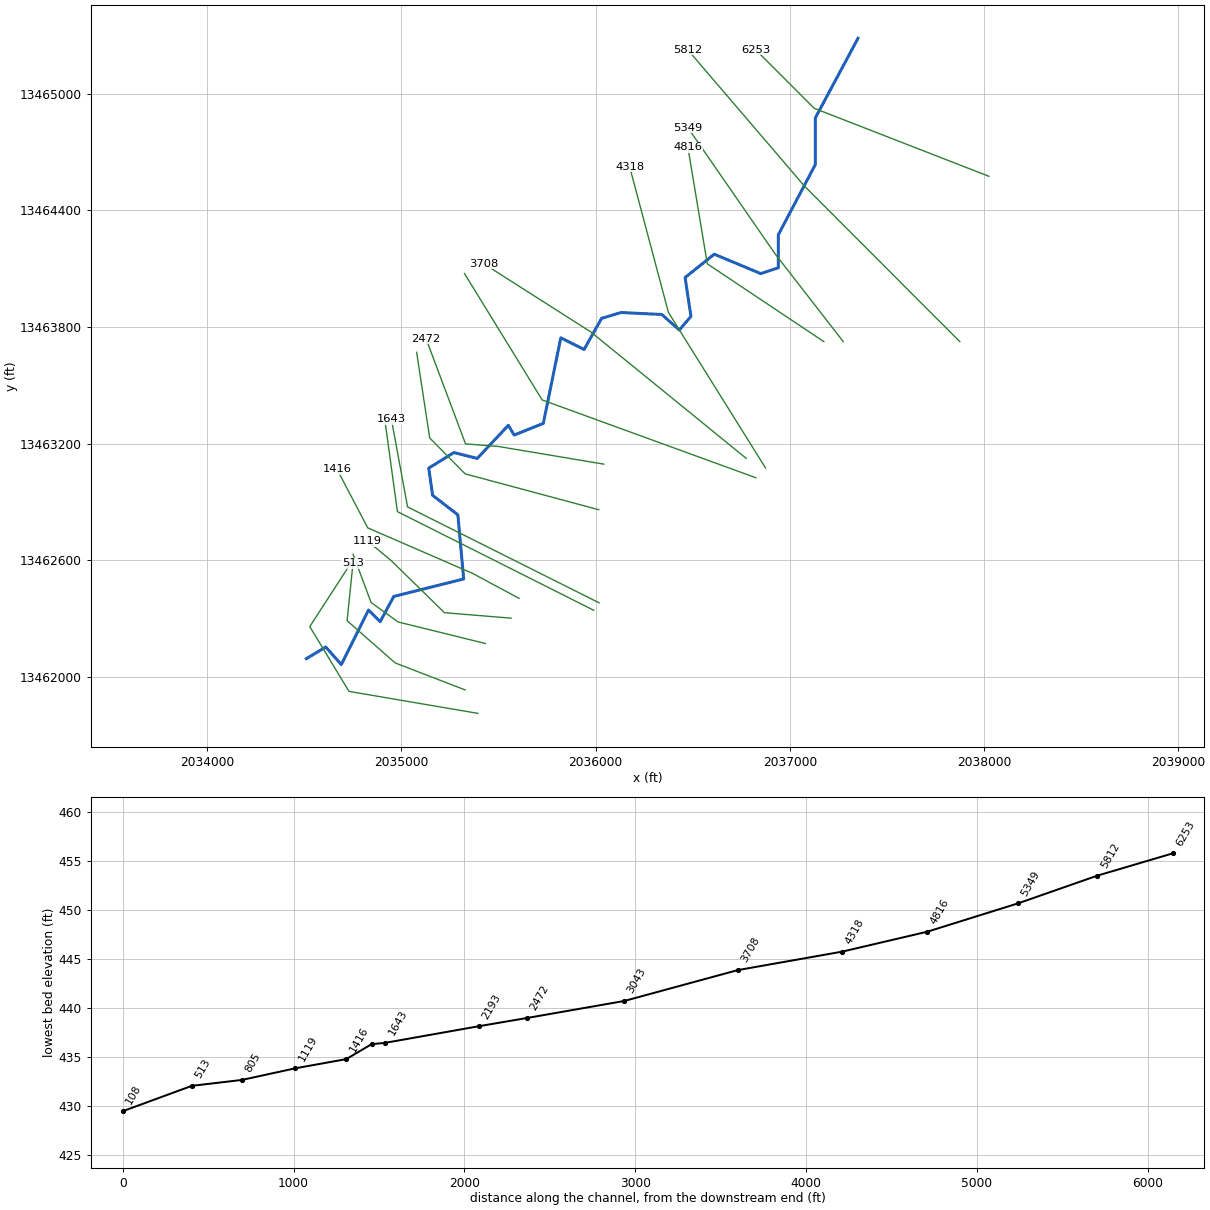
--- UNT 040 in RCW.prj (project) ---

Proj Title=UNT 040 in RCW Base Level Engineering
Current Plan=p01
Default Exp/Contr=0.3,0.1
English Units
Geom File=g01
Flow File=f01
Plan File=p01
Y Axis Title=Elevation
X Axis Title(PF)=Main Channel Distance
X Axis Title(XS)=Station
BEGIN DESCRIPTION:
UNT 040 in RCW
END DESCRIPTION:
DSS Export Rating Curves= 0
DSS Export Rating Curve Sorted= 0
DSS Export Volume Flow Curves= 0
DXF OffsetX= 0
DXF OffsetY= 0
DXF ScaleX= 1
DXF ScaleY= 10

--- UNT 040 in RCW.p01 (plan) ---

Plan Title=Multiple Run
Short Identifier=Multiple
Geom File=g01
Flow File=f01
Subcritical Flow
K Sum by GR= 0
Std Step Tol= 0.01
Critical Tol= 0.01
Num of Std Step Trials= 20
Max Error Tol= 0.3
Flow Tol Ratio= 0.001
Split Flow NTrial= 30
Split Flow Tol= 0.02
Split Flow Ratio= 0.02
Log Output Level= 0
Friction Slope Method= 1
Unsteady Friction Slope Method= 2
Unsteady Bridges Friction Slope Method= 1
Parabolic Critical Depth
Global Vel Dist=  1 , 1 , 1
Global Log Level= 0
CheckData=True
Encroach Param= -1, 0, 0, 0
BEGIN DESCRIPTION:
Multiple Run
END DESCRIPTION:

--- UNT 040 in RCW.f01 (steady flow) ---

Flow Title=Multiple
Program Version=5.05
Number of Profiles= 7
Profile Names=10-year,25-year,50-year,1pct_min,100-year,1pct_plu,500-year
River Rch & RM=UNT 040 in RCW,Reach-1         ,6253
     156     210     254     153     306     611     450
River Rch & RM=UNT 040 in RCW,Reach-1         ,5812
     264     366     451     276     552    1101     839
Boundary for River Rch & Prof#=UNT 040 in RCW,Reach-1         , 1
Up Type= 0
Dn Type= 3
Dn Slope=0.005
Boundary for River Rch & Prof#=UNT 040 in RCW,Reach-1         , 2
Up Type= 0
Dn Type= 3
Dn Slope=0.005
Boundary for River Rch & Prof#=UNT 040 in RCW,Reach-1         , 3
Up Type= 0
Dn Type= 3
Dn Slope=0.005
Boundary for River Rch & Prof#=UNT 040 in RCW,Reach-1         , 4
Up Type= 0
Dn Type= 3
Dn Slope=0.005
Boundary for River Rch & Prof#=UNT 040 in RCW,Reach-1         , 5
Up Type= 0
Dn Type= 3
Dn Slope=0.005
Boundary for River Rch & Prof#=UNT 040 in RCW,Reach-1         , 6
Up Type= 0
Dn Type= 3
Dn Slope=0.005
Boundary for River Rch & Prof#=UNT 040 in RCW,Reach-1         , 7
Up Type= 0
Dn Type= 3
Dn Slope=0.005
DSS Import GetInterval= 0
DSS Import GetPeak= 0
DSS Import FillOption= 0

--- UNT 040 in RCW.g01 (geometry) ---

Geom Title=Existing Conditions
Program Version=5.05

River Reach=UNT 040 in RCW  ,Reach-1
Reach XY= 30
       2037350.8     13465284.54       2037130.8     13464874.54
       2037130.8     13464634.54       2036940.8     13464274.54
       2036940.8     13464104.54       2036850.8     13464074.54
       2036610.8     13464174.54       2036460.8     13464054.54
       2036490.8     13463854.54       2036430.8     13463784.54
       2036340.8     13463864.54       2036130.8     13463874.54
       2036030.8     13463844.54       2035940.8     13463684.54
       2035820.8     13463744.54       2035730.8     13463304.54
       2035580.8     13463244.54       2035550.8     13463294.54
       2035390.8     13463124.54       2035270.8     13463154.54
       2035140.8     13463074.54       2035160.8     13462934.54
       2035290.8     13462834.54       2035320.8     13462504.54
       2034960.8     13462414.54       2034890.8     13462284.54
       2034830.8     13462344.54       2034690.8     13462064.54
       2034610.8     13462154.54       2034510.8     13462094.54

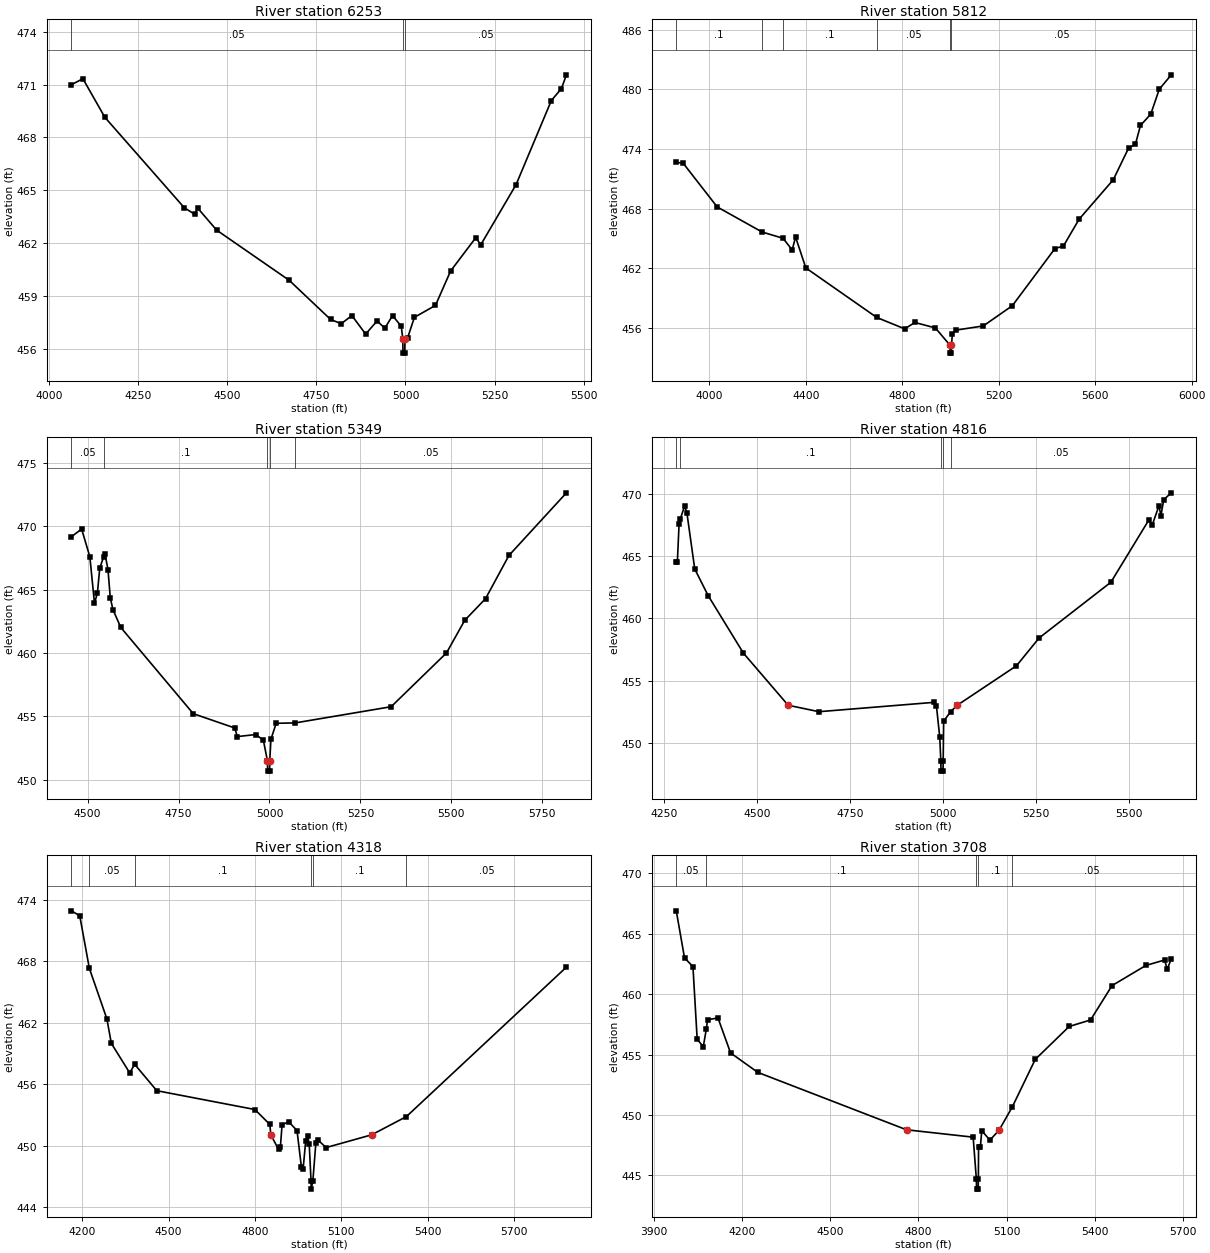
Type RM Length L Ch R = 1 ,6253    ,441,441,441
BEGIN DESCRIPTION:
UNT 040 in RCW 8.0
END DESCRIPTION:
XS GIS Cut Line= 3
      2038025.02     13464574.99        2037125.       13464925.
      2036825.03     13465224.97
#Sta/Elev= 30
    4062  470.99  4094.2  471.33  4155.9  469.14  4378.9  464.01  4408.8  463.63
  4416.1     464  4469.7  462.74  4673.6  459.89  4789.7  457.67  4819.6  457.43
  4849.5  457.89  4888.2  456.84  4920.4  457.59  4941.8  457.17  4963.7  457.89
  4988.2  457.28  4992.5  456.56    4993  455.76    4998  455.76  4998.5  456.56
  5006.2  456.64    5025  457.79  5084.2  458.47  5126.7  460.42  5197.4  462.31
  5211.5  461.91  5310.5  465.32  5409.5  470.09  5437.8  470.77  5451.9  471.55
#Mann= 3 ,-1 , 0
    4062     .05       0  4992.5     .03       0  4998.5     .05       0
Bank Sta=4992.5,4998.5
XS Rating Curve= 0 ,0
Exp/Cntr=0.3,0.1

Type RM Length L Ch R = 1 ,5812    ,463,463,463
BEGIN DESCRIPTION:
UNT 040 in RCW 7.0
END DESCRIPTION:
XS GIS Cut Line= 3
      2037874.98     13463725.02        2037075.       13464525.
        2036475.       13465225.
#Sta/Elev= 30
  3862.2  472.65  3890.5  472.58  4031.9  468.18    4218  465.66  4304.9  465.03
    4343  463.86  4357.1  465.15  4399.6  462.05    4694  457.07  4809.7  455.93
  4852.1  456.57    4937  456.02  4997.5  454.29    4998  453.49  5003.3  453.49
  5003.8  454.29  5007.3  455.37  5021.5   455.8  5135.7  456.22  5256.4  458.26
  5433.1     464  5468.2  464.25    5533  466.94  5674.6   470.9  5738.2  474.08
  5766.8  474.48  5787.6  476.36  5830.4   477.5  5865.6     480  5915.5  481.45
#Mann= 6 ,-1 , 0
  3862.2      .1       0    4218     .08       0  4304.9      .1       0
    4694     .05       0  4997.5     .03       0  5003.8     .05       0
Bank Sta=4997.5,5003.8
XS Rating Curve= 0 ,0
Exp/Cntr=0.3,0.1

Type RM Length L Ch R = 1 ,5349    ,533,533,533
BEGIN DESCRIPTION:
UNT 040 in RCW 6.0
END DESCRIPTION:
XS GIS Cut Line= 3
      2037275.03     13463724.96        2036925.       13464175.
        2036475.       13464825.
#Sta/Elev= 30
  4455.6  469.19  4483.7   469.8  4506.3   467.6    4519  463.93  4527.1  464.76
  4533.5  466.71  4543.8  467.57  4547.9  467.82  4556.1   466.6  4562.4  464.38
  4569.7  463.43  4591.4  462.02  4790.5  455.21  4904.5  454.08  4911.7   453.4
  4962.4  453.56  4983.2  453.12  4994.5  451.47    4995  450.67  5000.3  450.67
  5000.8  451.47    5004  453.19  5018.5  454.45  5070.8  454.48  5334.5  455.76
  5486.6  460.01  5536.6  462.58    5594   464.3  5658.2  467.71  5816.3  472.66
#Mann= 5 ,-1 , 0
  4455.6     .05       0  4543.8      .1       0  4994.5     .07       0
  5000.8      .1       0  5070.8     .05       0
Bank Sta=4994.5,5000.8
XS Rating Curve= 0 ,0
Exp/Cntr=0.3,0.1

Type RM Length L Ch R = 1 ,4816    ,498,498,498
BEGIN DESCRIPTION:
UNT 040 in RCW 5.0
END DESCRIPTION:
XS GIS Cut Line= 3
        2037175.       13463725.        2036575.       13464125.
        2036475.     13464725.01
#Sta/Elev= 30
  4283.4  464.55  4286.4  464.55  4290.9  467.54  4294.4  467.98  4305.9  469.01
  4311.9  468.47    4333  463.96    4369  461.83  4463.7  457.22 4583.91453.0469
  4666.5  452.53    4976  453.28    4982  453.02    4991   450.5  4993.9  448.57
  4994.4  447.77  4999.7  447.77  5000.2  448.57  5001.5  451.77  5020.1  452.53
 5038.04453.0471  5197.1  456.21    5258  458.44  5450.6   462.9    5552  467.86
  5562.1  467.52  5579.8  469.03  5584.9  468.22  5592.5  469.51  5612.8  470.06
#Mann= 5 ,-1 , 0
  4283.4     .05       0  4294.4      .1       0  4993.9     .07       0
  5000.2      .1       0  5020.1     .05       0
Bank Sta=4583.91,5038.04
XS Rating Curve= 0 ,0
Exp/Cntr=0.3,0.1

Type RM Length L Ch R = 1 ,4318    ,610,610,610
BEGIN DESCRIPTION:
UNT 040 in RCW 4.0
END DESCRIPTION:
XS GIS Cut Line= 3
      2036875.02     13463074.96        2036375.       13463875.
      2036175.01     13464624.95
#Sta/Elev= 30
  4162.7  472.94  4191.6  472.46    4225  467.32    4286  462.37  4301.3  459.99
    4365  457.11  4382.6  457.93  4459.3  455.36  4800.1  453.52    4852  452.06
  4855.3451.0497  4882.1  449.63  4888.6  449.85  4894.5  452.03  4917.5  452.33
  4946.4  451.46  4961.7  447.88  4967.6   447.7  4976.4  450.42  4982.9  450.98
  4988.8  450.13  4995.1  446.54  4995.6  445.74  5001.4  446.54  5011.8  450.23
  5019.5  450.54  5047.2   449.8 5205.77451.0485  5326.4  452.83  5882.3  467.44
#Mann= 6 ,-1 , 0
  4162.7      .1       0    4225     .05       0  4382.6      .1       0
  4995.1     .07       0  5001.4      .1       0  5326.4     .05       0
Bank Sta=4855.3,5205.77
XS Rating Curve= 0 ,0
Exp/Cntr=0.3,0.1

Type RM Length L Ch R = 1 ,3708    ,665,665,665
BEGIN DESCRIPTION:
UNT 040 in RCW 3.0
END DESCRIPTION:
XS GIS Cut Line= 3
        2036775.       13463125.        2035975.       13463775.
      2035424.99       13464125.
#Sta/Elev= 30
  3976.7  466.89  4004.7     463  4033.4  462.27  4047.8  456.26  4068.6  455.65
  4078.6  457.07    4083  457.87  4118.4  458.03  4161.3  455.13    4254  453.52
 4759.45448.7707  4985.9  448.16  4996.9  444.66  4997.4  443.86  5003.1  443.86
  5003.6  444.66  5004.3  447.31  5010.4  447.31  5015.1   448.7    5043  447.91
 5074.82448.7707  5118.7  450.65  5197.1   454.6  5312.3  457.32  5385.1  457.86
  5457.9   460.7    5573  462.37  5636.5  462.82  5645.8  462.06  5659.4  462.92
#Mann= 5 ,-1 , 0
  3976.7     .05       0  4078.6      .1       0  4996.9     .07       0
  5003.6      .1       0  5118.7     .05       0
Bank Sta=4759.45,5074.82
XS Rating Curve= 0 ,0
Exp/Cntr=0.3,0.1

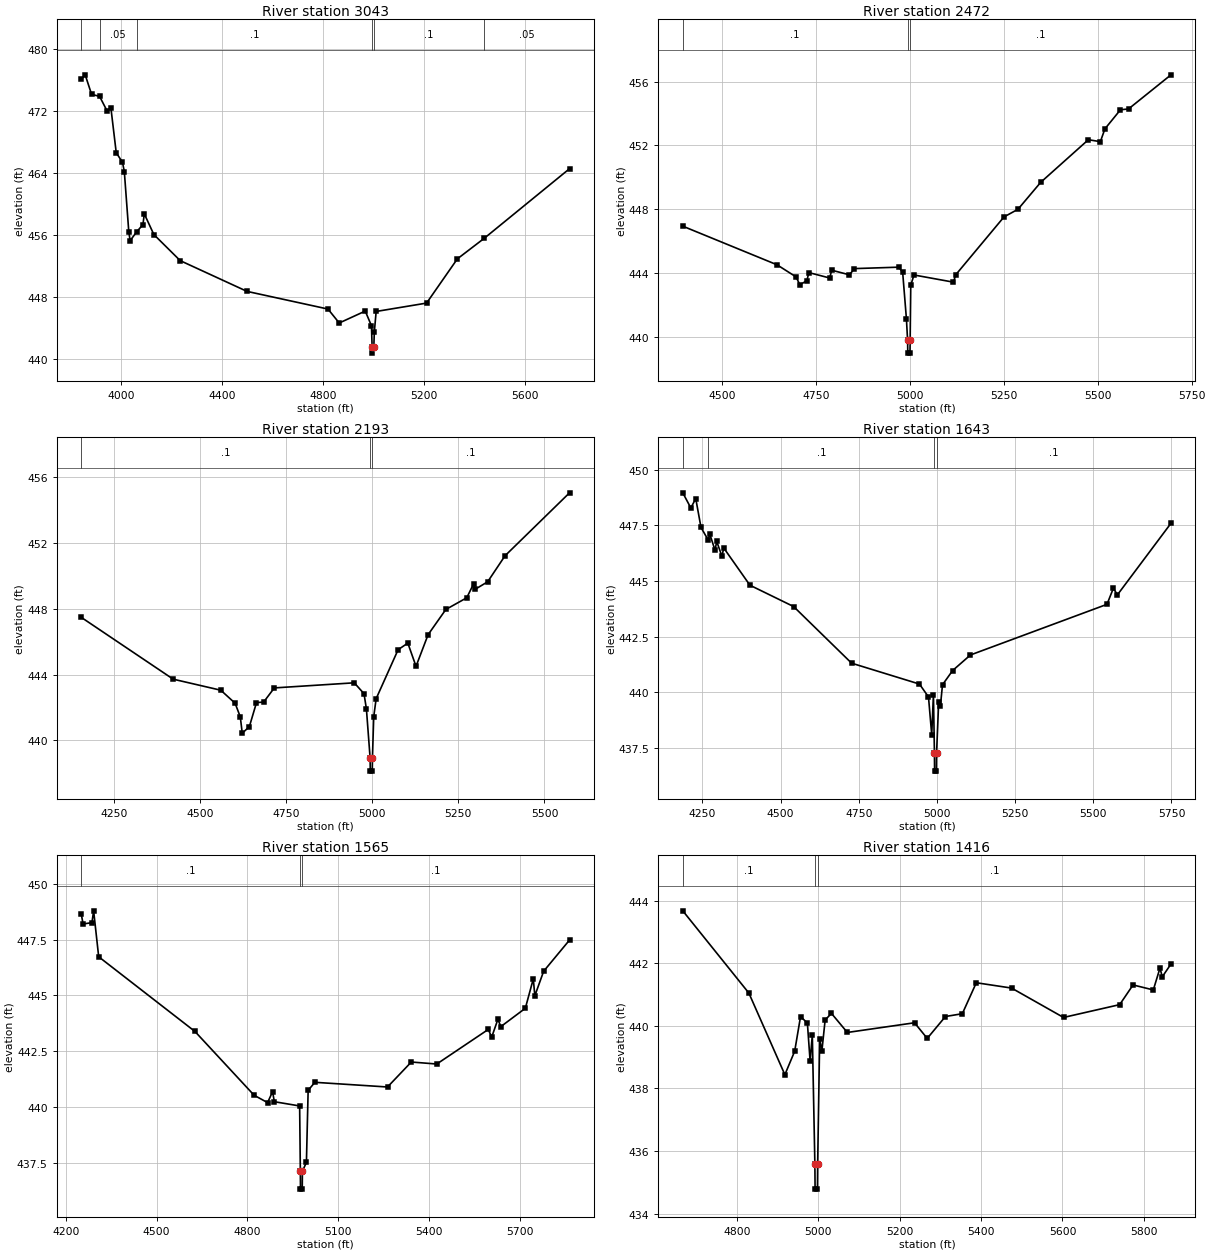
Type RM Length L Ch R = 1 ,3043    ,571,571,571
BEGIN DESCRIPTION:
UNT 040 in RCW 2.0
END DESCRIPTION:
XS GIS Cut Line= 3
      2036825.02     13463024.99        2035725.       13463425.
        2035325.       13464075.
#Sta/Elev= 30
  3842.2  476.05  3857.5  476.64  3882.8  474.12  3914.5  473.86    3944  471.99
  3959.3  472.38  3980.5  466.58  4005.2  465.35  4012.5  464.15  4030.4  456.29
  4035.7  455.24  4061.9  456.39  4086.3  457.31  4091.6  458.69  4129.5  456.02
  4233.9  452.65  4498.6  448.68  4819.2   446.4  4863.7   444.6  4966.8  446.14
  4991.4  444.24    4994  441.51  4994.5  440.71  5000.7  441.51  5002.7  443.43
    5010  446.09  5209.7  447.17  5331.6  452.88  5438.3  455.54  5775.9  464.52
#Mann= 6 ,-1 , 0
  3842.2      .1       0  3914.5     .05       0  4061.9      .1       0
    4994     .07       0  5000.7      .1       0  5438.3     .05       0
Bank Sta=4994,5000.7
XS Rating Curve= 0 ,0
Exp/Cntr=0.3,0.1

Type RM Length L Ch R = 1 ,2472    ,279,279,279
BEGIN DESCRIPTION:
Mapping XS 9e17a47b
END DESCRIPTION:
XS GIS Cut Line= 4
      2036042.19     13463094.93      2035497.48     13463186.07
      2035330.38     13463199.09       2035126.7     13463740.77
#Sta/Elev= 30
  4396.4  446.93    4647  444.51  4697.7  443.75  4707.9  443.25  4726.6  443.52
  4731.7  444.02  4787.3  443.68  4792.4  444.17  4839.7  443.88  4853.1  444.27
  4971.2  444.36  4981.3  444.03  4991.3  441.11  4994.4  439.77  4994.9  438.97
  5000.7  438.97  5001.2  439.77  5002.8  443.23  5011.4  443.87  5116.3  443.42
  5122.7  443.89  5250.8  447.51    5288  447.99  5348.5  449.68  5475.2  452.35
  5507.2  452.23  5519.2  453.03  5560.6  454.23    5582  454.28    5695  456.42
#Mann= 3 ,-1 , 0
  4396.4      .1       0  4994.4     .07       0  5001.2      .1       0
Bank Sta=4994.4,5001.2
XS Rating Curve= 0 ,0
Exp/Cntr=0.3,0.1

Type RM Length L Ch R = 1 ,2193    ,550,550,550
BEGIN DESCRIPTION:
Mapping XS 3fe1a37e
END DESCRIPTION:
XS GIS Cut Line= 4
      2036016.12     13462860.56      2035328.21     13463045.01
      2035145.91     13463229.48      2035078.64     13463670.01
#Sta/Elev= 30
  4155.6  447.47  4422.3  443.72  4560.5  443.05    4602  442.26  4617.1  441.43
  4622.7  440.44  4643.4  440.84  4664.1   442.3  4684.8  442.33  4715.8  443.19
  4947.9   443.5  4976.2  442.84  4983.2  441.91  4993.9  438.94  4994.4  438.14
  5000.2  438.14  5000.7  438.94  5004.4  441.45  5011.5  442.54  5075.2  445.51
  5103.4  445.91  5127.2   444.5  5162.2  446.42  5213.7  447.95  5274.4  448.66
  5294.2   449.5  5299.2  449.18  5335.1  449.63  5385.6  451.21  5572.8  455.03
#Mann= 3 ,-1 , 0
  4155.6      .1       0  4993.9     .07       0  5000.7      .1       0
Bank Sta=4993.9,5000.7
XS Rating Curve= 0 ,0
Exp/Cntr=0.3,0.1

Type RM Length L Ch R = 1 ,1643    ,78,78,78
BEGIN DESCRIPTION:
Mapping XS d96385e3
END DESCRIPTION:
XS GIS Cut Line= 3
      2036017.97     13462381.88      2035031.88     13462874.93
      2034948.54     13463326.31
#Sta/Elev= 30
    4187  448.97  4212.7  448.29  4228.5  448.71  4245.3  447.41  4268.5  446.84
  4273.2  447.12    4290  446.39  4295.6  446.78  4312.3  446.11  4317.9  446.49
  4401.8  444.81  4541.5  443.85    4727   441.3    4944  440.36  4972.9  439.78
  4983.2  438.08  4988.7  439.88  4991.9  437.24  4992.4  436.44  4998.2  436.44
  4998.7  437.24  5005.5  439.57  5011.1  439.39  5017.7  440.33  5050.2  440.97
  5107.1  441.67  5543.8  443.95  5564.1  444.67  5577.3  444.38  5748.5   447.6
#Mann= 4 ,-1 , 0
    4187     .05       0  4268.5      .1       0  4991.9     .07       0
  4998.7      .1       0
Bank Sta=4991.9,4998.7
XS Rating Curve= 0 ,0
Exp/Cntr=0.3,0.1

Type RM Length L Ch R = 1 ,1565    ,149,149,149
BEGIN DESCRIPTION:
Mapping XS 938d6cf2
END DESCRIPTION:
XS GIS Cut Line= 3
      2035990.17     13462343.69      2034979.79     13462850.62
      2034913.82     13463329.78
#Sta/Elev= 30
  4251.1  448.63  4256.9   448.2  4286.2  448.26  4291.8  448.79  4308.5  446.73
  4626.8  443.38  4822.3  440.52  4866.9  440.19  4883.4  440.68  4889.3  440.23
  4972.9  440.04  4975.2  437.11  4975.7  436.31  4981.5  436.31    4982  437.11
  4995.3  437.51    5001  440.74  5023.3   441.1  5263.4  440.89  5342.1  442.01
  5426.3  441.92  5596.4  443.47    5608  443.13  5628.2  443.92  5638.3   443.6
  5719.1  444.42  5745.4  445.74  5750.5  444.98  5779.6  446.08  5865.2  447.48
#Mann= 3 ,-1 , 0
  4251.1      .1       0  4975.2     .07       0    4982      .1       0
Bank Sta=4975.2,4982
XS Rating Curve= 0 ,0
Exp/Cntr=0.3,0.1

Type RM Length L Ch R = 1 ,1416    ,297,297,297
BEGIN DESCRIPTION:
Mapping XS 2c71e9e3
END DESCRIPTION:
XS GIS Cut Line= 4
      2035605.95     13462404.84      2035367.27     13462532.86
       2034826.9     13462767.24      2034669.26     13463067.41
#Sta/Elev= 30
  4667.6  443.68  4829.9  441.05  4918.3  438.44  4942.4  439.19  4956.8   440.3
  4973.6  440.09  4980.3  438.87  4985.7  439.71    4992  435.58  4992.5  434.78
  4998.3  434.78  4998.8  435.58  5003.8  439.59  5009.2   439.2  5017.2  440.19
  5032.7   440.4  5071.7  439.79  5236.7   440.1  5267.9   439.6  5312.6   440.3
  5354.1  440.39  5388.4  441.38    5475  441.21  5602.6  440.27  5740.5  440.68
  5773.3  441.31  5823.1  441.15  5839.5  441.85  5845.1  441.57  5866.5  441.98
#Mann= 3 ,-1 , 0
  4667.6      .1       0    4992     .07       0  4998.8      .1       0
Bank Sta=4992,4998.8
XS Rating Curve= 0 ,0
Exp/Cntr=0.3,0.1

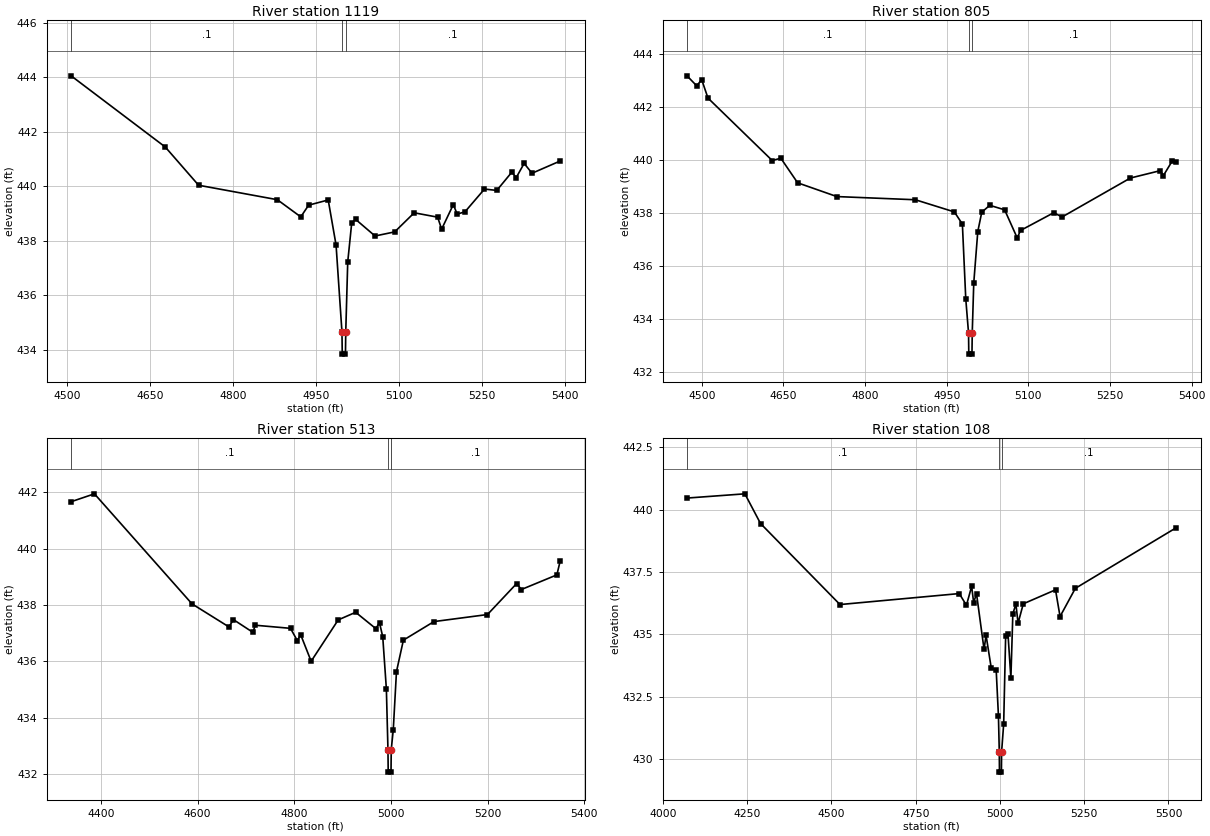
Type RM Length L Ch R = 1 ,1119    ,314,314,314
BEGIN DESCRIPTION:
Mapping XS 091192a5
END DESCRIPTION:
XS GIS Cut Line= 4
      2035564.76     13462302.83      2035221.87     13462331.04
      2034946.26     13462600.14      2034826.49     13462699.08
#Sta/Elev= 30
  4507.8  444.05  4678.1  441.44  4738.3  440.04  4880.7  439.51  4923.1  438.88
  4937.3  439.31  4972.7   439.5  4986.9  437.85  4997.6  434.65  4998.1  433.85
  5003.9  433.85  5004.4  434.65    5008  437.23  5015.2  438.66  5022.2  438.79
  5057.4  438.18  5092.9  438.33  5128.2  439.03  5170.6  438.87  5177.8  438.43
  5198.9  439.33    5206  438.98  5220.2  439.07  5255.3   439.9  5277.5  439.85
  5304.8  440.52  5312.7  440.32    5327  440.84  5341.3  440.48  5392.4  440.93
#Mann= 3 ,-1 , 0
  4507.8      .1       0  4997.6     .07       0  5004.4      .1       0
Bank Sta=4997.6,5004.4
XS Rating Curve= 0 ,0
Exp/Cntr=0.3,0.1

Type RM Length L Ch R = 1 ,805     ,292,292,292
BEGIN DESCRIPTION:
Mapping XS 90d7f387
END DESCRIPTION:
XS GIS Cut Line= 4
      2035432.35     13462172.63      2034983.15      13462283.3
      2034844.27     13462383.12      2034751.44     13462631.37
#Sta/Elev= 30
  4472.9  443.17  4490.8  442.79  4499.8  443.03  4511.4  442.33  4629.5  439.97
  4645.2  440.06  4676.1  439.13  4748.2  438.61  4892.4  438.49  4964.1  438.03
  4978.8  437.57    4985  434.75  4990.1  433.46  4990.6  432.66  4996.4  432.66
  4996.9  433.46  4999.7  435.35  5007.1  437.29  5014.4  438.02  5029.1  438.28
  5056.4  438.11  5079.5  437.05  5085.6  437.33  5146.6     438    5162  437.84
  5287.4  439.31  5342.6  439.59    5348   439.4  5364.8  439.97  5371.6  439.91
#Mann= 3 ,-1 , 0
  4472.9      .1       0  4990.1     .07       0  4996.9      .1       0
Bank Sta=4990.1,4996.9
XS Rating Curve= 0 ,0
Exp/Cntr=0.3,0.1

Type RM Length L Ch R = 1 ,513     ,405,405,405
BEGIN DESCRIPTION:
Mapping XS ed829e29
END DESCRIPTION:
XS GIS Cut Line= 4
      2035328.23      13461933.9      2034967.96     13462072.79
      2034720.57     13462289.81      2034750.95     13462584.95
#Sta/Elev= 30
  4338.3  441.67  4386.5  441.95  4588.3  438.04  4664.8  437.22    4674  437.48
  4714.1  437.03  4719.4  437.28  4792.1  437.17  4806.3  436.73    4813  436.95
  4834.8     436  4890.8  437.47  4926.9  437.74  4968.6  437.16  4976.2  437.37
  4982.9  436.87  4990.4  435.02  4993.7  432.86  4994.2  432.06    5000  432.06
  5000.5  432.86  5004.7  433.57  5011.3  435.63  5025.6  436.75  5088.9  437.41
  5199.5  437.66  5259.8  438.76  5269.8  438.55  5343.1  439.07  5350.2  439.58
#Mann= 3 ,-1 , 0
  4338.3      .1       0  4993.7     .07       0  5000.5      .1       0
Bank Sta=4993.7,5000.5
XS Rating Curve= 0 ,0
Exp/Cntr=0.3,0.1

Type RM Length L Ch R = 1 ,108     ,0,0,0
BEGIN DESCRIPTION:
UNT 040 in RCW 1.0
END DESCRIPTION:
XS GIS Cut Line= 4
      2035394.22     13461813.27      2034730.33     13461926.31
      2034528.51     13462259.42      2034739.78     13462585.54
#Sta/Elev= 30
  4071.4  440.46  4243.1  440.63  4289.5  439.44  4525.3  436.19  4879.2  436.63
  4900.5  436.16    4916  436.92  4921.9  436.27  4930.4  436.63  4952.8  434.39
  4958.7  434.96  4974.2  433.64  4988.8  433.56  4995.5  431.72    4998  430.27
  4998.5  429.47  5004.3  429.47  5004.8  430.27    5011   431.4  5016.9  434.94
  5023.9  434.99  5032.4  433.24  5038.2  435.82  5047.3  436.21  5053.7  435.44
  5069.2  436.22  5164.8  436.78  5178.3  435.71  5223.7  436.84  5522.9  439.27
#Mann= 3 ,-1 , 0
  4071.4      .1       0    4998     .07       0  5004.8      .1       0
Bank Sta=4998,5004.8
XS Rating Curve= 0 ,0
Exp/Cntr=0.3,0.1
LCMann Table=0

Chan Stop Cuts=-1
Use User Specified Reach Order=0
Composite Channel Slope=5