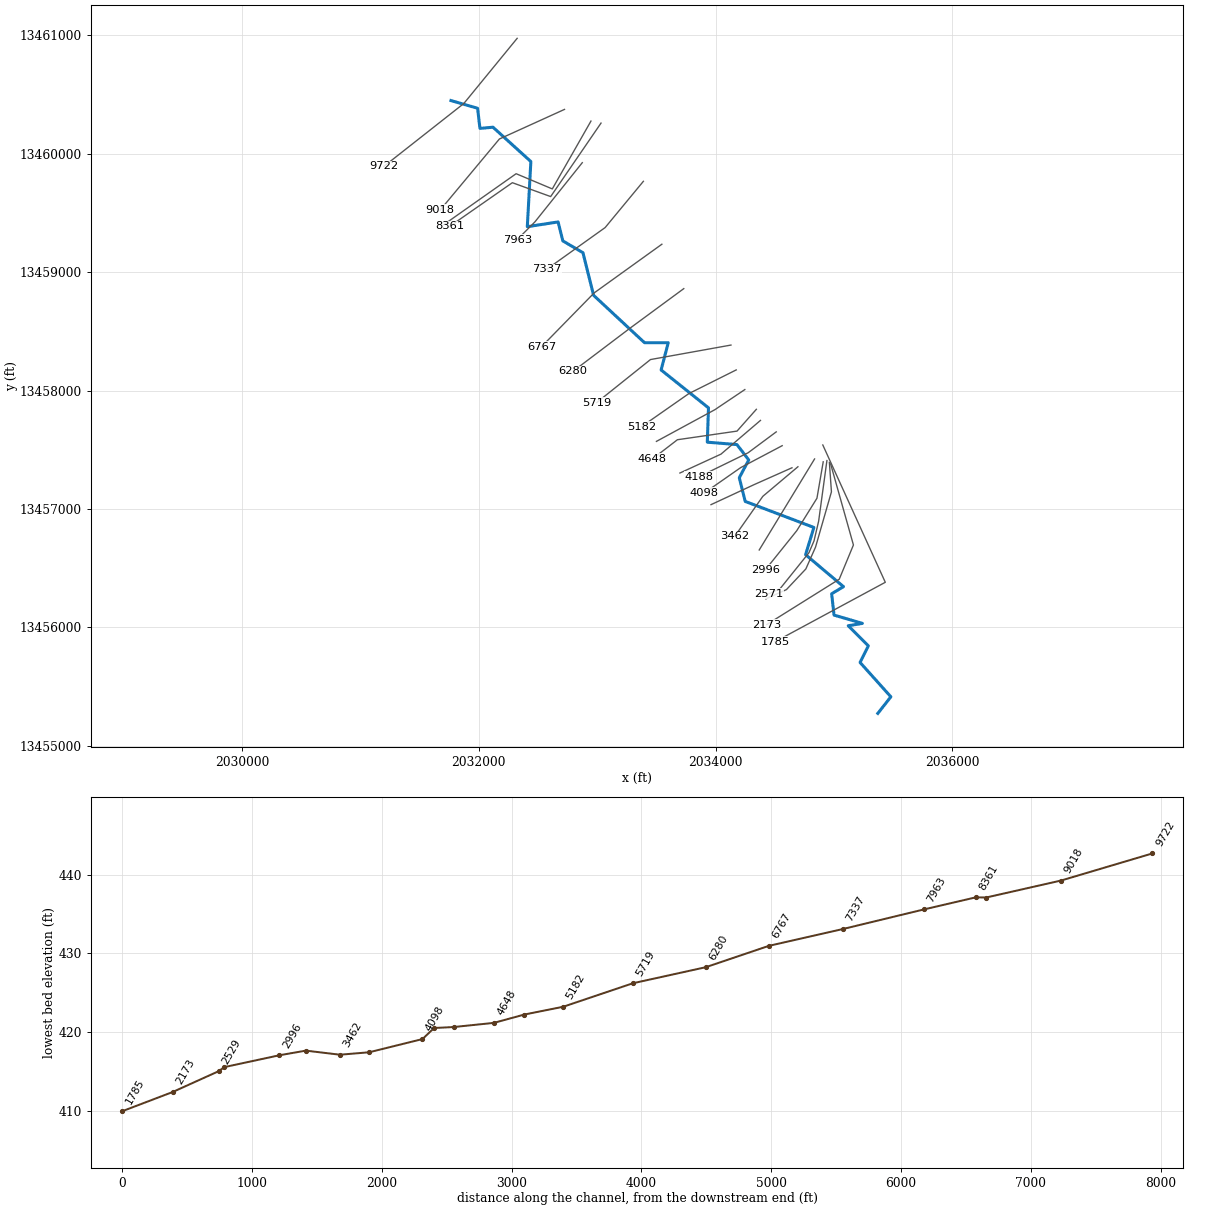
--- UNT 041 in RCW.prj (project) ---

Proj Title=UNT 041 in RCW Base Level Engineering
Current Plan=p01
Default Exp/Contr=0.3,0.1
English Units
Geom File=g01
Flow File=f01
Plan File=p01
BEGIN DESCRIPTION:
UNT 041 in RCW
END DESCRIPTION:

--- UNT 041 in RCW.p01 (plan) ---

Plan Title=Multiple Run
Short Identifier=Multiple
Geom File=g01
Flow File=f01
Subcritical Flow
K Sum by GR= 0
Std Step Tol= 0.01
Critical Tol= 0.01
Num of Std Step Trials= 20
Max Error Tol= 0.3
Flow Tol Ratio= 0.001
Split Flow NTrial= 30
Split Flow Tol= 0.02
Split Flow Ratio= 0.02
Log Output Level= 0
Friction Slope Method= 1
Unsteady Friction Slope Method= 2
Unsteady Bridges Friction Slope Method= 1
Parabolic Critical Depth
Global Vel Dist=  1 , 1 , 1
Global Log Level= 0
CheckData=True
Encroach Param= -1, 0, 0, 0
BEGIN DESCRIPTION:
Multiple Run
END DESCRIPTION:

--- UNT 041 in RCW.f01 (steady flow) ---

Flow Title=Multiple
Number of Profiles=7
Profile Names=10-year,25-year,50-year,1pct_min,100-year,1pct_plu,500-year
River Rch & RM= UNT 041 in RCW,Reach-1,9722
     152     204     245     147     293     585     427
River Rch & RM= UNT 041 in RCW,Reach-1,8441
     229     314     383     233     465     928     695
Boundary for River Rch & Prof#=UNT 041 in RCW,Reach-1,1
Up Type=0
Dn Type=3
Dn Slope=0.005
Boundary for River Rch & Prof#=UNT 041 in RCW,Reach-1,2
Up Type=0
Dn Type=3
Dn Slope=0.005
Boundary for River Rch & Prof#=UNT 041 in RCW,Reach-1,3
Up Type=0
Dn Type=3
Dn Slope=0.005
Boundary for River Rch & Prof#=UNT 041 in RCW,Reach-1,4
Up Type=0
Dn Type=3
Dn Slope=0.005
Boundary for River Rch & Prof#=UNT 041 in RCW,Reach-1,5
Up Type=0
Dn Type=3
Dn Slope=0.005
Boundary for River Rch & Prof#=UNT 041 in RCW,Reach-1,6
Up Type=0
Dn Type=3
Dn Slope=0.005
Boundary for River Rch & Prof#=UNT 041 in RCW,Reach-1,7
Up Type=0
Dn Type=3
Dn Slope=0.005

--- UNT 041 in RCW.g01 (geometry) ---

Geom Title=Existing Conditions

River Reach=UNT 041 in RCW,Reach-1
Reach XY= 30
      2031765.80     13460449.54      2031990.80     13460384.54
      2032010.80     13460214.54      2032120.80     13460224.54
      2032440.80     13459934.54      2032410.80     13459384.54
      2032670.80     13459424.54      2032710.80     13459264.54
      2032880.80     13459164.54      2032970.80     13458804.54
      2033400.80     13458404.54      2033600.80     13458404.54
      2033540.80     13458174.54      2033940.80     13457854.54
      2033930.80     13457564.54      2034180.80     13457544.54
      2034280.80     13457414.54      2034200.80     13457264.54
      2034250.80     13457064.54      2034830.80     13456844.54
      2034760.80     13456614.54      2035080.80     13456344.54
      2034980.80     13456284.54      2035000.80     13456104.54
      2035240.80     13456034.54      2035120.80     13456014.54
      2035290.80     13455844.54      2035220.80     13455704.54
      2035480.80     13455414.54      2035370.80     13455274.54

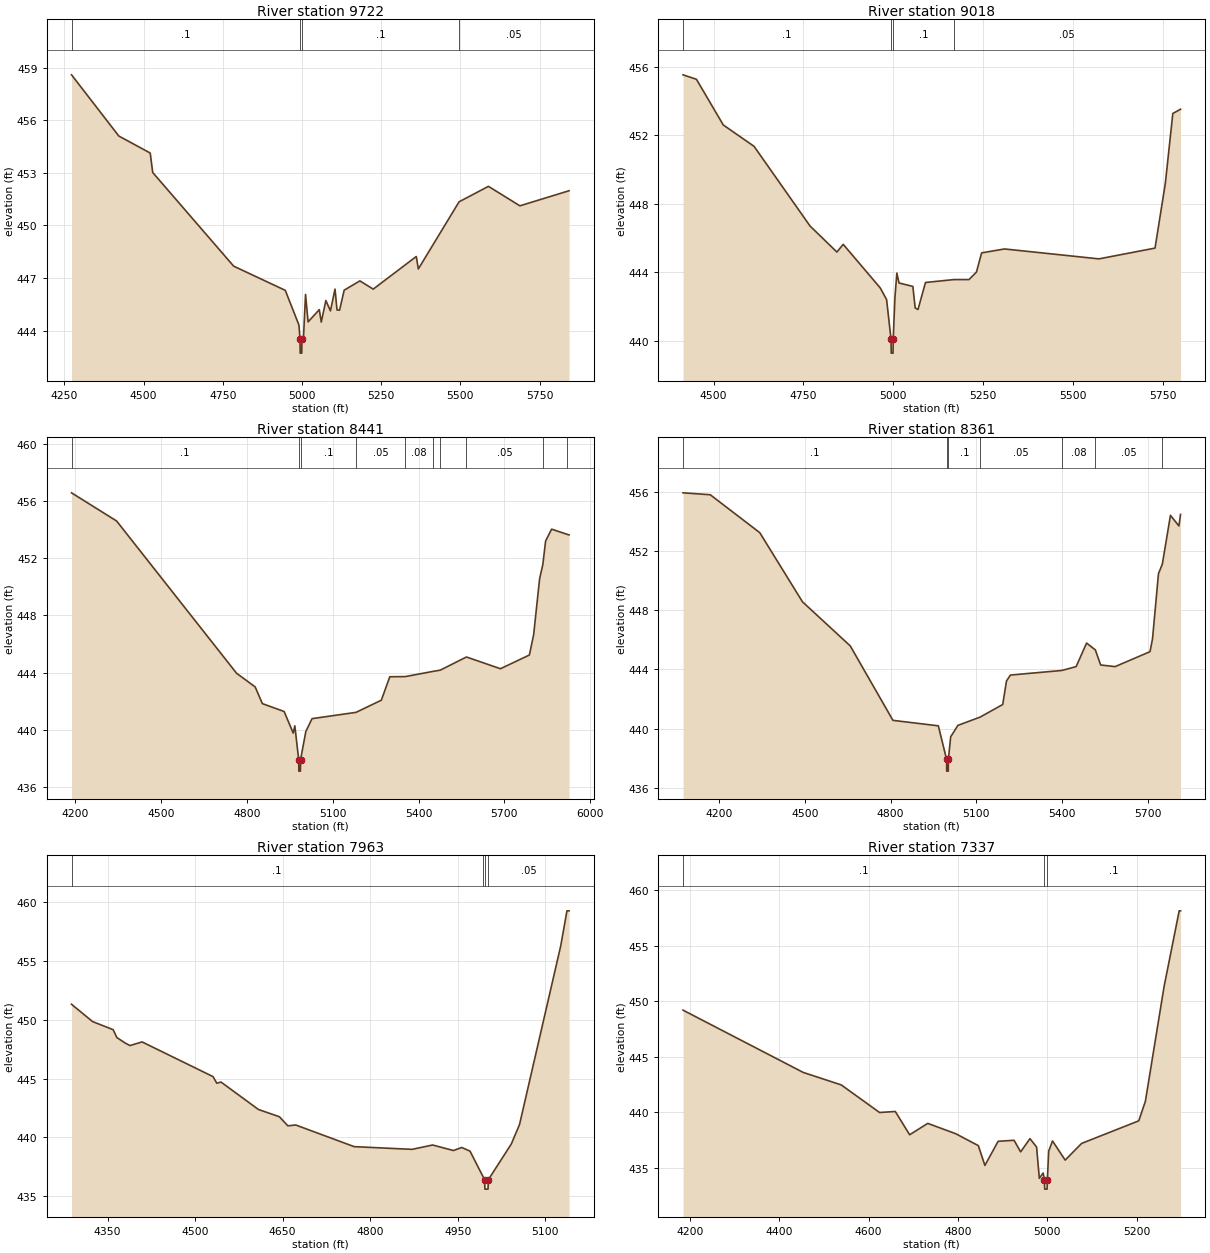
Type RM Length L Ch R = 1,9722,704,704,704
BEGIN DESCRIPTION:
UNT 041 in RCW 11.0
END DESCRIPTION:
XS GIS Cut Line= 3
      2032325.03     13460975.03      2031875.00     13460425.00
      2031199.14     13459893.33
#Sta/Elev= 30
  4272.4  458.59  4421.7  455.10  4520.8  454.13  4528.7  453.02  4784.2  447.68
  4947.2  446.30  4990.3  444.32  4993.7  443.52  4994.2  442.72  4999.2  442.72
  4999.7  443.52  5004.8  443.64  5011.1  446.07  5019.2  444.50  5054.5  445.20
  5060.8  444.49  5075.3  445.72  5089.7  445.13  5104.2  446.37  5110.5  445.18
  5118.6  445.17  5133.1  446.31  5182.8  446.84  5224.8  446.37  5360.8  448.23
  5367.2  447.52  5495.9  451.35  5588.5  452.23  5687.9  451.12  5843.0  451.98
#Mann=4,-1,0
  4272.4     0.1       0  4993.7    0.07       0  4999.7     0.1       0
  5495.9    0.05       0
Bank Sta=4993.7,4999.7
Exp/Cntr=0.3,0.1

Type RM Length L Ch R = 1,9018,577,577,577
BEGIN DESCRIPTION:
UNT 041 in RCW 10.0
END DESCRIPTION:
XS GIS Cut Line= 3
      2032724.98     13460374.99      2032175.00     13460125.00
      2031674.97     13459524.97
#Sta/Elev= 30
  4415.0  455.54  4452.3  455.28  4527.0  452.61  4612.7  451.36  4768.7  446.70
  4843.4  445.18  4861.0  445.63  4964.2  443.08  4981.8  442.40  4994.2  440.07
  4994.7  439.27  4999.7  439.27  5000.2  440.07  5004.9  442.49  5010.3  443.95
  5016.4  443.37  5054.9  443.17  5061.4  441.91  5069.2  441.82  5090.1  443.40
  5169.3  443.57  5211.1  443.57  5232.0  444.01  5246.3  445.13  5310.1  445.36
  5573.0  444.78  5729.2  445.41  5757.9  449.20  5778.7  453.28  5800.2  453.53
#Mann=4,-1,0
  4415.0     0.1       0  4994.2    0.07       0  5000.2     0.1       0
  5169.3    0.05       0
Bank Sta=4994.2,5000.2
Exp/Cntr=0.3,0.1

Type RM Length L Ch R = 1,8441,80,80,80
BEGIN DESCRIPTION:
UNT 041 in RCW 9.0
END DESCRIPTION:
XS GIS Cut Line= 4
      2032948.26     13460276.32      2032621.86     13459703.39
      2032316.31     13459831.86      2031705.19     13459401.30
#Sta/Elev= 30
  4187.6  456.57  4345.1  454.60  4764.4  443.95  4829.2  443.00  4854.4  441.83
  4930.4  441.28  4962.3  439.77  4967.8  440.28  4981.4  437.91  4981.9  437.11
  4987.3  437.11  4987.8  437.91  5006.3  439.88  5028.0  440.78  5181.8  441.22
  5270.1  442.07  5299.7  443.71  5353.7  443.72  5449.8  444.08  5475.8  444.17
  5567.5  445.09  5686.4  444.27  5787.5  445.23  5802.3  446.65  5823.2  450.57
  5834.3  451.54  5844.1  453.20  5865.1  454.03  5920.5  453.66  5926.0  453.63
#Mann=10,-1,0
  4187.6     0.1       0  4981.4    0.07       0  4987.8     0.1       0
  5181.8    0.05       0  5353.7    0.08       0  5449.8    0.05       0
  5475.8    0.08       0  5567.5    0.05       0  5834.3    0.08       0
  5920.5    0.05       0
Bank Sta=4981.4,4987.8
Exp/Cntr=0.3,0.1

Type RM Length L Ch R = 1,8361,398,398,398
BEGIN DESCRIPTION:
Mapping XS 370ea51c
END DESCRIPTION:
XS GIS Cut Line= 4
      2033033.31     13460259.37      2032607.97     13459638.72
      2032284.62     13459755.91      2031755.11     13459386.99
#Sta/Elev= 30
  4073.5  455.93  4168.8  455.80  4342.1  453.24  4491.6  448.57  4658.9  445.59
  4808.4  440.56  4967.3  440.19  4996.1  437.93  4996.6  437.13  5002.0  437.13
  5002.5  437.93  5010.5  439.45  5035.8  440.22  5113.6  440.78  5192.7  441.63
  5205.9  443.22  5219.7  443.62  5399.7  443.93  5449.7  444.19  5486.3  445.78
  5516.9  445.32  5535.6  444.30  5586.2  444.19  5708.4  445.20  5717.1  446.07
  5738.0  450.47  5751.4  451.11  5779.9  454.41  5809.6  453.69  5815.2  454.47
#Mann=7,-1,0
  4073.5     0.1       0  4996.1    0.07       0  5002.5     0.1       0
  5113.6    0.05       0  5399.7    0.08       0  5516.9    0.05       0
  5751.4    0.08       0
Bank Sta=4996.1,5002.5
Exp/Cntr=0.3,0.1

Type RM Length L Ch R = 1,7963,626,626,626
BEGIN DESCRIPTION:
UNT 041 in RCW 8.0
END DESCRIPTION:
XS GIS Cut Line= 3
      2032875.01     13459925.02      2032475.00     13459425.00
      2032324.98     13459274.98
#Sta/Elev= 30
  4288.3  451.31  4324.3  449.84  4359.6  449.15  4366.0  448.48  4380.4  448.01
  4388.4  447.80  4409.2  448.11  4530.8  445.16  4537.2  444.60  4544.4  444.70
  4608.5  442.37  4644.5  441.75  4658.9  440.98  4672.5  441.05  4772.6  439.21
  4871.8  438.98  4907.0  439.35  4942.8  438.88  4956.9  439.14  4971.1  438.83
  4992.9  436.71  4996.1  436.40  4996.6  435.60  5002.0  435.60  5002.5  436.40
  5041.8  439.43  5055.9  441.08  5126.6  456.28  5137.2  459.25  5140.8  459.25
#Mann=4,-1,0
  4288.3     0.1       0  4992.9    0.05       0  4996.1    0.03       0
  5002.5    0.05       0
Bank Sta=4996.1,5002.5
Exp/Cntr=0.3,0.1

Type RM Length L Ch R = 1,7337,570,570,570
BEGIN DESCRIPTION:
UNT 041 in RCW 7.0
END DESCRIPTION:
XS GIS Cut Line= 3
      2033390.98     13459767.65      2033068.04     13459377.00
      2032575.04     13459025.03
#Sta/Elev= 30
  4185.1  449.19  4454.0  443.59  4538.9  442.47  4624.6  439.99  4659.8  440.08
  4691.9  437.99  4732.4  439.01  4795.1  438.08  4845.5  437.01  4860.2  435.23
  4889.7  437.40  4925.4  437.49  4940.1  436.45  4961.0  437.64  4975.8  436.88
  4981.9  434.07  4990.5  434.55  4993.4  433.90  4993.9  433.10  4999.3  433.10
  4999.8  433.90  5002.9  436.52  5011.4  437.43  5039.7  435.71  5076.5  437.21
  5204.3  439.24  5219.1  441.00  5260.9  451.31  5294.7  458.12  5297.7  458.12
#Mann=3,-1,0
  4185.1     0.1       0  4993.4    0.07       0  4999.8     0.1       0
Bank Sta=4993.4,4999.8
Exp/Cntr=0.3,0.1

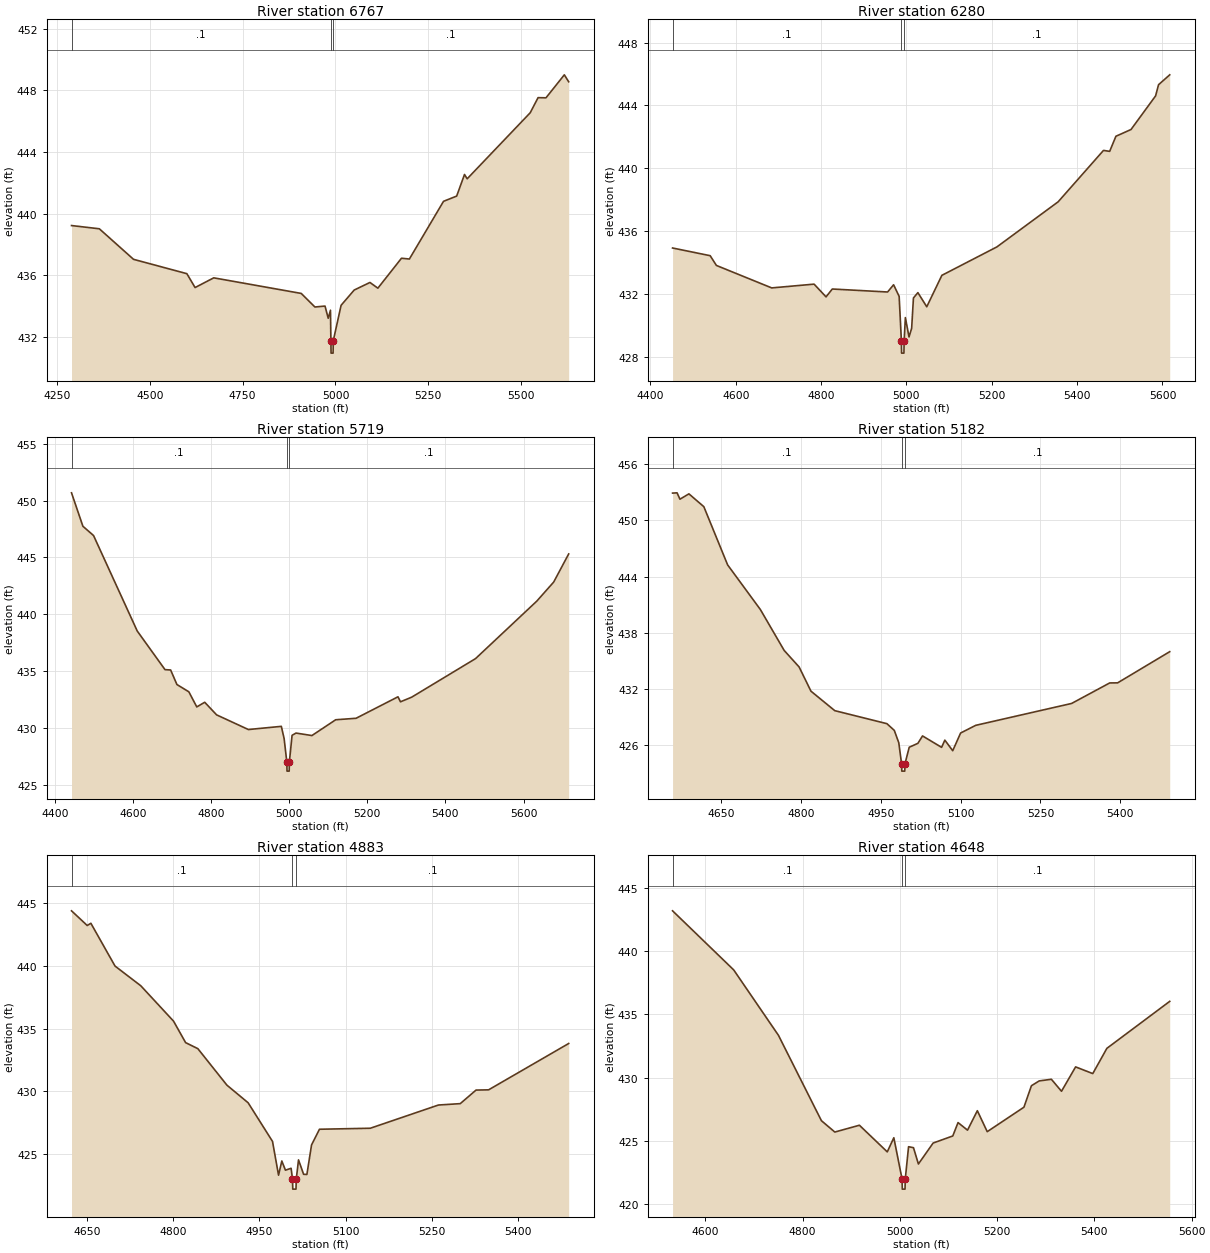
Type RM Length L Ch R = 1,6767,487,487,487
BEGIN DESCRIPTION:
UNT 041 in RCW 6.0
END DESCRIPTION:
XS GIS Cut Line= 3
      2033547.17     13459236.35      2032975.00     13458825.00
      2032531.61     13458371.82
#Sta/Elev= 30
  4289.3  439.23  4364.2  439.02  4456.3  437.04  4599.9  436.11  4622.0  435.21
  4672.3  435.84  4907.8  434.83  4944.7  433.95  4971.9  434.01  4980.5  433.22
  4986.6  433.74  4987.7  431.76  4988.2  430.96  4993.6  430.96  4994.1  431.76
  5015.2  434.06  5050.5  435.05  5092.9  435.54  5114.2  435.17  5177.8  437.11
  5199.1  437.06  5291.0  440.80  5326.4  441.14  5347.5  442.54  5354.7  442.26
  5524.4  446.54  5545.6  447.52  5566.9  447.51  5616.3  449.00  5628.0  448.55
#Mann=3,-1,0
  4289.3     0.1       0  4987.7    0.07       0  4994.1     0.1       0
Bank Sta=4987.7,4994.1
Exp/Cntr=0.3,0.1

Type RM Length L Ch R = 1,6280,561,561,561
BEGIN DESCRIPTION:
UNT 041 in RCW 5.0
END DESCRIPTION:
XS GIS Cut Line= 3
      2033732.09     13458861.37      2033275.00     13458525.00
      2032798.63     13458164.53
#Sta/Elev= 30
  4452.1  434.93  4540.2  434.44  4554.8  433.82  4684.4  432.39  4783.7  432.63
  4811.7  431.82  4826.4  432.32  4955.9  432.13  4970.0  432.59  4983.0  431.85
  4988.2  429.04  4988.7  428.24  4994.2  428.24  4994.7  429.04  4997.6  430.50
  5006.1  429.27  5012.3  429.82  5016.5  431.75  5026.9  432.09  5047.7  431.19
  5083.1  433.19  5212.1  435.00  5355.6  437.87  5461.8  441.14  5476.3  441.08
  5490.9  442.04  5526.3  442.47  5583.9  444.61  5590.8  445.32  5617.0  445.95
#Mann=3,-1,0
  4452.1     0.1       0  4988.2    0.07       0  4994.7     0.1       0
Bank Sta=4988.2,4994.7
Exp/Cntr=0.3,0.1

Type RM Length L Ch R = 1,5719,537,537,537
BEGIN DESCRIPTION:
UNT 041 in RCW 4.0
END DESCRIPTION:
XS GIS Cut Line= 3
      2034130.54     13458384.82      2033450.86     13458262.42
      2032996.49     13457898.92
#Sta/Elev= 30
  4443.0  450.69  4472.1  447.75  4499.4  446.93  4611.2  438.53  4682.3  435.13
  4696.7  435.10  4712.8  433.82  4743.3  433.18  4763.6  431.85  4783.9  432.26
  4814.4  431.15  4895.7  429.86  4980.0  430.14  4987.2  429.06  4994.1  427.00
  4994.6  426.20  5000.1  426.20  5000.6  427.00  5007.5  429.35  5017.6  429.55
  5058.3  429.33  5119.2  430.72  5171.3  430.85  5278.6  432.74  5285.0  432.30
  5313.8  432.71  5477.1  436.10  5633.9  441.16  5677.2  442.84  5715.5  445.31
#Mann=3,-1,0
  4443.0     0.1       0  4994.1    0.07       0  5000.6     0.1       0
Bank Sta=4994.1,5000.6
Exp/Cntr=0.3,0.1

Type RM Length L Ch R = 1,5182,299,299,299
BEGIN DESCRIPTION:
UNT 041 in RCW 3.0
END DESCRIPTION:
XS GIS Cut Line= 3
      2034174.97     13458174.99      2033775.00     13457975.00
      2033376.23     13457696.46
#Sta/Elev= 30
  4559.3  452.91  4567.7  452.94  4573.2  452.26  4590.0  452.83  4618.0  451.46
  4662.7  445.24  4724.2  440.47  4768.9  436.10  4796.9  434.34  4819.2  431.75
  4863.9  429.67  4961.8  428.28  4975.7  427.56  4984.1  426.24  4989.3  424.01
  4989.8  423.21  4995.3  423.21  4995.8  424.01  5003.7  425.76  5020.0  426.18
  5028.7  426.97  5064.5  425.75  5070.6  426.52  5085.4  425.39  5100.2  427.28
  5128.5  428.10  5308.7  430.44  5380.2  432.63  5395.1  432.64  5492.9  435.97
#Mann=3,-1,0
  4559.3     0.1       0  4989.3    0.07       0  4995.8     0.1       0
Bank Sta=4989.3,4995.8
Exp/Cntr=0.3,0.1

Type RM Length L Ch R = 1,4883,235,235,235
BEGIN DESCRIPTION:
Mapping XS 76541e1a
END DESCRIPTION:
XS GIS Cut Line= 3
      2034247.76     13458008.96      2033994.26     13457838.81
      2033501.19     13457571.44
#Sta/Elev= 30
  4622.5  444.39  4649.9  443.22  4656.2  443.40  4698.3  439.99  4743.2  438.42
  4800.3  435.60  4821.3  433.89  4842.6  433.41  4893.3  430.50  4930.2  429.10
  4972.7  426.02  4983.2  423.33  4988.9  424.46  4995.2  423.73  5005.1  423.88
  5007.5  423.02  5008.0  422.22  5013.6  422.22  5014.1  423.02  5018.0  424.55
  5026.9  423.40  5032.6  423.39  5040.7  425.74  5054.5  426.99  5143.1  427.07
  5261.8  428.92  5299.8  429.03  5327.3  430.11  5349.2  430.13  5488.7  433.82
#Mann=3,-1,0
  4622.5     0.1       0  5007.5    0.07       0  5014.1     0.1       0
Bank Sta=5007.5,5014.1
Exp/Cntr=0.3,0.1

Type RM Length L Ch R = 1,4648,310,310,310
BEGIN DESCRIPTION:
Mapping XS 76a3f6f9
END DESCRIPTION:
XS GIS Cut Line= 4
      2034344.95     13457842.28      2034181.76     13457658.25
      2033678.29     13457585.34      2033466.46     13457422.12
#Sta/Elev= 30
  4532.8  443.20  4658.5  438.52  4750.5  433.34  4838.8  426.58  4866.4  425.68
  4916.9  426.22  4974.2  424.11  4987.7  425.23  5004.6  421.96  5005.1  421.16
  5010.7  421.16  5011.2  421.96  5018.0  424.52  5028.1  424.44  5038.2  423.15
  5068.5  424.81  5108.9  425.37  5119.7  426.43  5139.2  425.83  5159.4  427.37
  5179.7  425.71  5255.2  427.65  5270.6  429.35  5286.6  429.73  5311.6  429.86
  5332.4  428.91  5361.4  430.84  5396.7  430.31  5425.7  432.31  5554.9  436.03
#Mann=3,-1,0
  4532.8     0.1       0  5004.6    0.07       0  5011.2     0.1       0
Bank Sta=5004.6,5011.2
Exp/Cntr=0.3,0.1

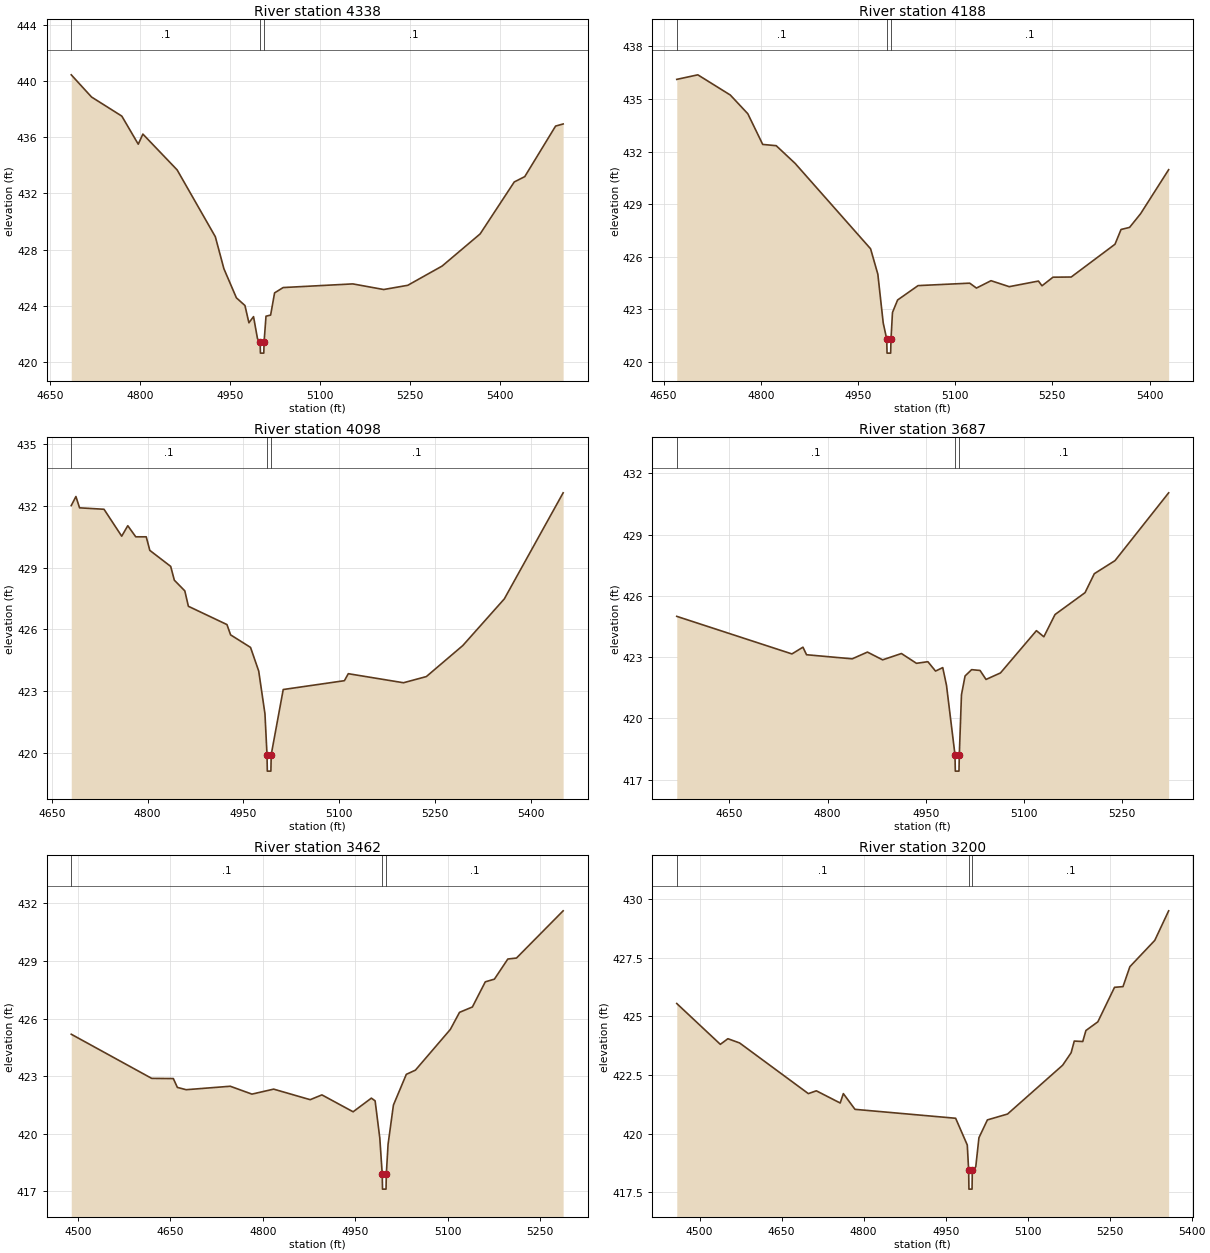
Type RM Length L Ch R = 1,4338,150,150,150
BEGIN DESCRIPTION:
Mapping XS 4686438f
END DESCRIPTION:
XS GIS Cut Line= 3
      2034379.69     13457748.54      2034046.34     13457463.81
      2033699.57     13457304.29
#Sta/Elev= 30
  4685.9  440.45  4719.7  438.87  4770.2  437.51  4797.6  435.51  4805.3  436.23
  4862.4  433.68  4926.1  428.92  4940.4  426.64  4961.2  424.57  4975.5  424.02
  4982.1  422.79  4989.8  423.23  4996.4  421.66  5000.8  421.43  5001.3  420.63
  5006.9  420.63  5007.4  421.43  5010.6  423.26  5018.3  423.34  5024.9  424.92
  5039.2  425.30  5155.3  425.56  5206.8  425.16  5246.9  425.46  5304.2  426.83
  5367.6  429.12  5424.5  432.82  5442.0  433.20  5493.4  436.80  5506.0  436.95
#Mann=3,-1,0
  4685.9     0.1       0  5000.8    0.07       0  5007.4     0.1       0
Bank Sta=5000.8,5007.4
Exp/Cntr=0.3,0.1

Type RM Length L Ch R = 1,4188,90,90,90
BEGIN DESCRIPTION:
UNT 041 in RCW 2.0
END DESCRIPTION:
XS GIS Cut Line= 3
      2034512.93     13457651.75      2034275.00     13457475.00
      2033858.97     13457272.02
#Sta/Elev= 30
  4670.2  436.12  4702.7  436.38  4752.8  435.23  4779.9  434.16  4802.9  432.41
  4823.7  432.34  4852.9  431.33  4969.4  426.46  4980.6  425.01  4988.9  422.23
  4994.3  421.31  4994.8  420.51  5000.4  420.51  5000.9  421.31  5003.2  422.83
  5011.1  423.54  5042.7  424.36  5122.4  424.50  5132.8  424.22  5155.3  424.64
  5183.4  424.30  5228.5  424.62  5234.0  424.35  5251.0  424.84  5279.1  424.85
  5346.7  426.72  5356.0  427.56  5369.2  427.68  5386.2  428.46  5429.5  430.97
#Mann=3,-1,0
  4670.2     0.1       0  4994.3    0.07       0  5000.9     0.1       0
Bank Sta=4994.3,5000.9
Exp/Cntr=0.3,0.1

Type RM Length L Ch R = 1,4098,411,411,411
BEGIN DESCRIPTION:
Mapping XS bb6a328b
END DESCRIPTION:
XS GIS Cut Line= 3
      2034563.21     13457535.12      2034212.14     13457349.66
      2033906.14     13457136.11
#Sta/Elev= 30
  4680.6  432.02  4687.9  432.46  4693.6  431.91  4731.9  431.84  4759.6  430.53
  4769.1  431.04  4781.6  430.50  4798.0  430.50  4803.6  429.84  4836.3  429.06
  4842.0  428.39  4858.4  427.87  4864.0  427.12  4924.4  426.23  4930.1  425.73
  4961.3  425.12  4974.1  423.97  4983.9  421.89  4987.1  419.90  4987.6  419.10
  4993.2  419.10  4993.7  419.90  5012.5  423.07  5108.3  423.50  5114.4  423.84
  5200.8  423.40  5236.6  423.70  5293.7  425.21  5358.7  427.48  5450.8  432.64
#Mann=3,-1,0
  4680.6     0.1       0  4987.1    0.07       0  4993.7     0.1       0
Bank Sta=4987.1,4993.7
Exp/Cntr=0.3,0.1

Type RM Length L Ch R = 1,3687,225,225,225
BEGIN DESCRIPTION:
Mapping XS 7e843015
END DESCRIPTION:
XS GIS Cut Line= 3
      2034645.71     13457348.51      2034329.33     13457207.73
      2033962.10     13457037.14
#Sta/Elev= 30
  4569.6  425.00  4745.5  423.16  4762.3  423.49  4767.8  423.12  4837.5  422.92
  4860.8  423.25  4884.0  422.87  4912.7  423.18  4935.7  422.70  4953.1  422.78
  4964.8  422.32  4975.8  422.49  4981.5  421.63  4994.5  418.22  4995.0  417.42
  5000.6  417.42  5001.1  418.22  5004.4  421.16  5009.9  422.08  5019.9  422.39
  5032.8  422.35  5041.9  421.91  5064.0  422.23  5118.9  424.30  5130.2  424.00
  5147.3  425.09  5193.1  426.16  5207.3  427.09  5238.9  427.73  5320.8  431.05
#Mann=3,-1,0
  4569.6     0.1       0  4994.5    0.07       0  5001.1     0.1       0
Bank Sta=4994.5,5001.1
Exp/Cntr=0.3,0.1

Type RM Length L Ch R = 1,3462,262,262,262
BEGIN DESCRIPTION:
Mapping XS a6fcbfc0
END DESCRIPTION:
XS GIS Cut Line= 3
      2034696.05     13457357.20      2034399.64     13457107.47
      2034163.99     13456771.57
#Sta/Elev= 30
  4489.1  425.18  4619.6  422.88  4654.7  422.87  4661.2  422.41  4675.5  422.29
  4747.0  422.47  4782.2  422.06  4817.4  422.32  4876.7  421.77  4895.7  422.02
  4946.3  421.14  4975.9  421.85  4982.0  421.71  4989.6  419.77  4993.5  417.91
  4994.0  417.11  4999.7  417.11  5000.2  417.91  5003.0  419.44  5011.7  421.49
  5032.6  423.09  5047.4  423.31  5104.0  425.43  5118.9  426.32  5139.8  426.60
  5160.7  427.91  5175.5  428.05  5197.3  429.10  5211.3  429.15  5287.0  431.61
#Mann=3,-1,0
  4489.1     0.1       0  4993.5    0.07       0  5000.2     0.1       0
Bank Sta=4993.5,5000.2
Exp/Cntr=0.3,0.1

Type RM Length L Ch R = 1,3200,204,204,204
BEGIN DESCRIPTION:
Mapping XS d756fc1f
END DESCRIPTION:
XS GIS Cut Line= 2
      2034836.63     13457423.13      2034369.20     13456654.38
#Sta/Elev= 30
  4458.2  425.54  4537.9  423.80  4551.7  424.04  4573.1  423.86  4698.9  421.70
  4713.5  421.82  4757.1  421.30  4762.9  421.70  4784.2  421.03  4968.3  420.65
  4989.6  419.51  4992.1  418.43  4992.6  417.63  4998.3  417.63  4998.8  418.43
  5005.1  418.58  5010.9  419.82  5026.4  420.58  5063.2  420.83  5164.0  422.91
  5179.5  423.44  5185.3  423.94  5200.8  423.92  5206.6  424.39  5228.4  424.76
  5258.9  426.23  5274.4  426.26  5287.0  427.11  5332.5  428.23  5357.9  429.49
#Mann=3,-1,0
  4458.2     0.1       0  4992.1    0.07       0  4998.8     0.1       0
Bank Sta=4992.1,4998.8
Exp/Cntr=0.3,0.1

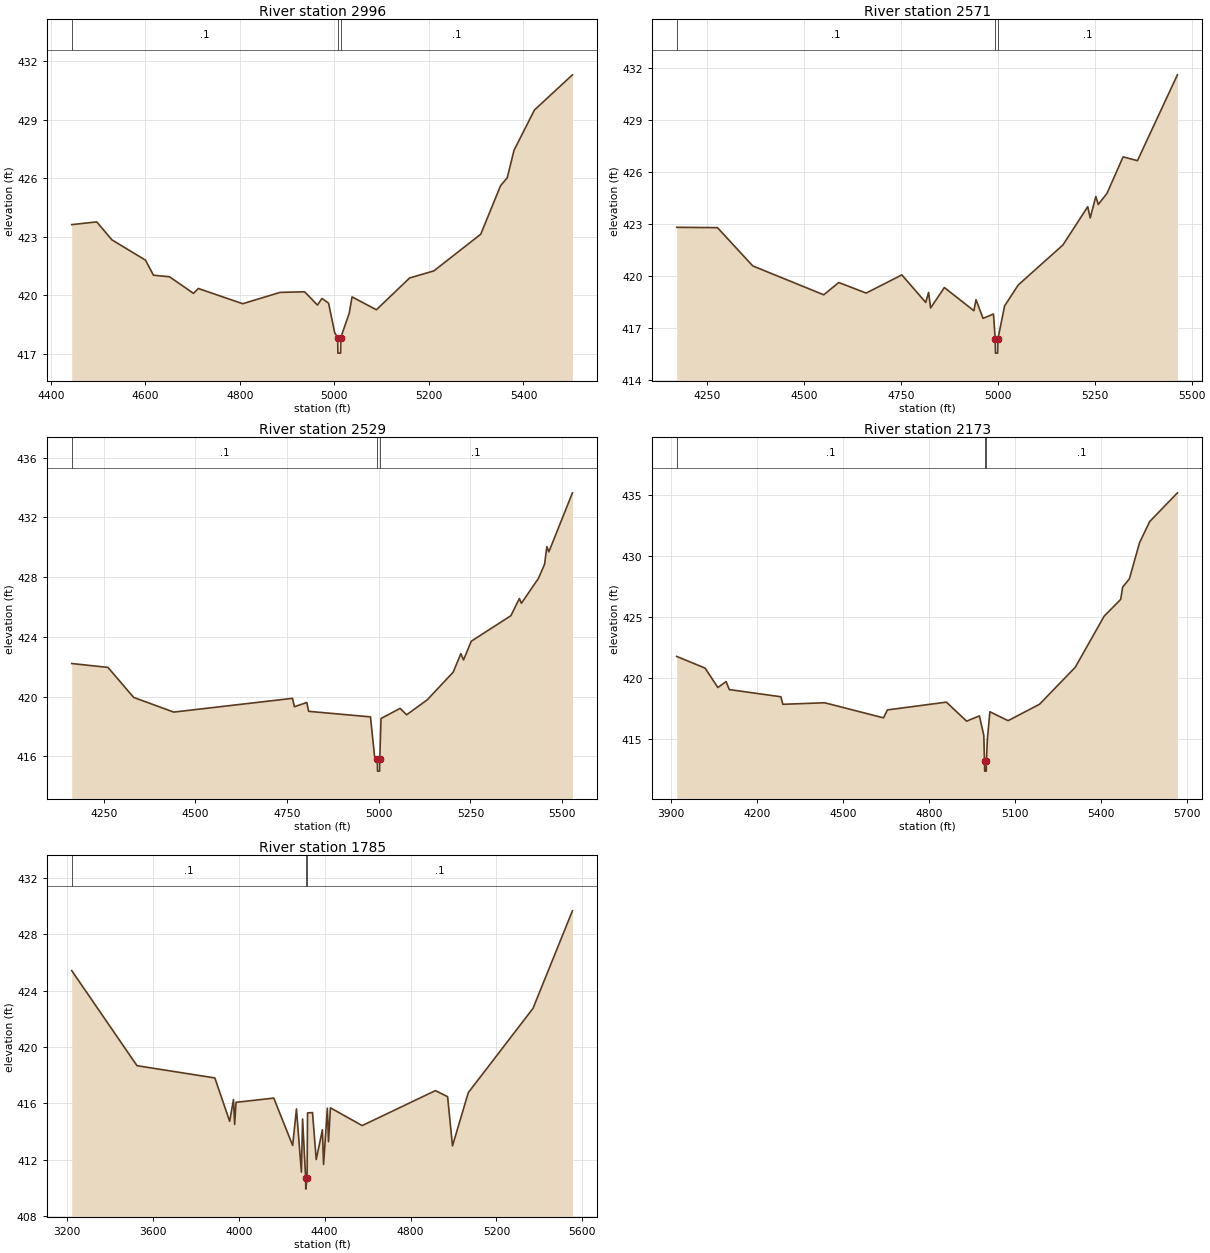
Type RM Length L Ch R = 1,2996,425,425,425
BEGIN DESCRIPTION:
Mapping XS a7ec01bd
END DESCRIPTION:
XS GIS Cut Line= 4
      2034909.56     13457398.88      2034856.60     13457091.00
      2034686.10     13456817.11      2034420.49     13456486.39
#Sta/Elev= 30
  4444.4  423.62  4497.4  423.76  4529.5  422.84  4600.5  421.80  4617.3  421.03
  4651.3  420.95  4702.0  420.10  4712.2  420.35  4806.1  419.57  4885.2  420.15
  4937.1  420.18  4964.3  419.50  4973.7  419.84  4987.7  419.60  5000.9  418.07
  5007.0  417.84  5007.5  417.04  5013.2  417.04  5013.7  417.84  5031.6  419.10
  5037.4  419.92  5088.9  419.26  5159.3  420.89  5210.4  421.25  5309.7  423.13
  5351.5  425.61  5365.7  426.02  5380.1  427.43  5423.3  429.49  5503.6  431.29
#Mann=3,-1,0
  4444.4     0.1       0  5007.0    0.07       0  5013.7     0.1       0
Bank Sta=5007,5013.7
Exp/Cntr=0.3,0.1

Type RM Length L Ch R = 1,2571,42,42,42
BEGIN DESCRIPTION:
Mapping XS 76701d45
END DESCRIPTION:
XS GIS Cut Line= 6
      2034940.80     13457409.25      2034871.00     13456897.84
      2034831.93     13456731.17      2034788.96     13456630.91
      2034545.47     13456327.52      2034448.87     13456283.73
#Sta/Elev= 30
  4171.9  422.80  4277.1  422.78  4368.0  420.57  4551.1  418.90  4590.0  419.61
  4660.6  419.00  4752.6  420.05  4814.2  418.46  4821.6  419.04  4826.8  418.14
  4862.3  419.32  4938.5  417.98  4943.9  418.62  4962.1  417.54  4988.9  417.79
  4993.5  416.33  4994.0  415.53  4999.7  415.53  5000.2  416.33  5017.7  418.26
  5052.9  419.47  5168.1  421.78  5232.1  423.99  5238.5  423.34  5252.9  424.58
  5259.3  424.12  5281.7  424.76  5323.3  426.87  5360.3  426.65  5463.4  431.61
#Mann=3,-1,0
  4171.9     0.1       0  4993.5    0.07       0  5000.2     0.1       0
Bank Sta=4993.5,5000.2
Exp/Cntr=0.3,0.1

Type RM Length L Ch R = 1,2529,356,356,356
BEGIN DESCRIPTION:
Mapping XS acd94b5d
END DESCRIPTION:
XS GIS Cut Line= 6
      2034961.63     13457393.66      2034979.00     13457145.36
      2034844.95     13456679.09      2034762.92     13456494.19
      2034598.86     13456319.71      2034425.70     13456241.60
#Sta/Elev= 30
  4162.5  422.22  4261.4  421.96  4331.6  419.95  4440.8  418.97  4764.7  419.89
  4769.9  419.33  4803.7  419.61  4808.9  419.02  4977.4  418.65  4988.6  416.01
  4996.1  415.82  4996.6  415.02  5002.3  415.02  5002.8  415.82  5006.2  418.54
  5058.2  419.22  5076.0  418.79  5132.2  419.79  5203.0  421.64  5224.0  422.88
  5231.3  422.46  5252.3  423.71  5360.5  425.42  5383.6  426.57  5389.1  426.25
  5435.4  427.91  5452.3  428.86  5458.5  430.04  5464.0  429.69  5528.3  433.64
#Mann=3,-1,0
  4162.5     0.1       0  4996.1    0.07       0  5002.8     0.1       0
Bank Sta=4996.1,5002.8
Exp/Cntr=0.3,0.1

Type RM Length L Ch R = 1,2173,388,388,388
BEGIN DESCRIPTION:
Mapping XS 0c17cc98
END DESCRIPTION:
XS GIS Cut Line= 4
      2034972.05     13457381.50      2035164.76     13456696.58
      2035044.97     13456407.51      2034432.96     13456024.68
#Sta/Elev= 30
  3919.6  421.77  4018.7  420.81  4063.2  419.22  4092.0  419.71  4103.0  419.05
  4283.0  418.46  4289.9  417.84  4435.4  417.97  4640.9  416.73  4654.5  417.38
  4860.1  418.02  4930.7  416.46  4975.3  416.89  4990.6  415.30  4993.1  413.16
  4993.6  412.36  4999.3  412.36  4999.8  413.16  5003.0  414.97  5011.8  417.23
  5075.5  416.50  5185.1  417.85  5309.6  420.88  5410.3  425.07  5468.1  426.45
  5474.8  427.45  5498.4  428.14  5533.7  431.09  5569.1  432.83  5665.9  435.19
#Mann=3,-1,0
  3919.6     0.1       0  4993.1    0.07       0  4999.8     0.1       0
Bank Sta=4993.1,4999.8
Exp/Cntr=0.3,0.1

Type RM Length L Ch R = 1,1785,0,0,0
BEGIN DESCRIPTION:
UNT 041 in RCW 1.0
END DESCRIPTION:
XS GIS Cut Line= 3
      2034906.09     13457541.17      2035433.86     13456381.47
      2034503.52     13455879.85
#Sta/Elev= 30
  3222.5  425.43  3526.5  418.68  3888.9  417.81  3958.0  414.73  3975.6  416.28
  3981.1  414.51  3987.4  416.08  4163.2  416.38  4251.2  413.02  4268.8  415.61
  4291.8  411.13  4297.3  414.90  4311.6  410.72  4312.1  409.92  4318.3  410.72
  4320.4  415.33  4343.5  415.35  4360.9  412.02  4389.6  414.13  4395.1  411.67
  4412.6  415.66  4418.1  413.29  4426.8  415.69  4574.9  414.43  4915.6  416.91
  4972.5  416.48  4995.2  412.99  5068.9  416.77  5370.1  422.75  5553.6  429.67
#Mann=3,-1,0
  3222.5     0.1       0  4311.6    0.07       0  4318.3     0.1       0
Bank Sta=4311.6,4318.3
Exp/Cntr=0.3,0.1

Chan Stop Cuts=-1