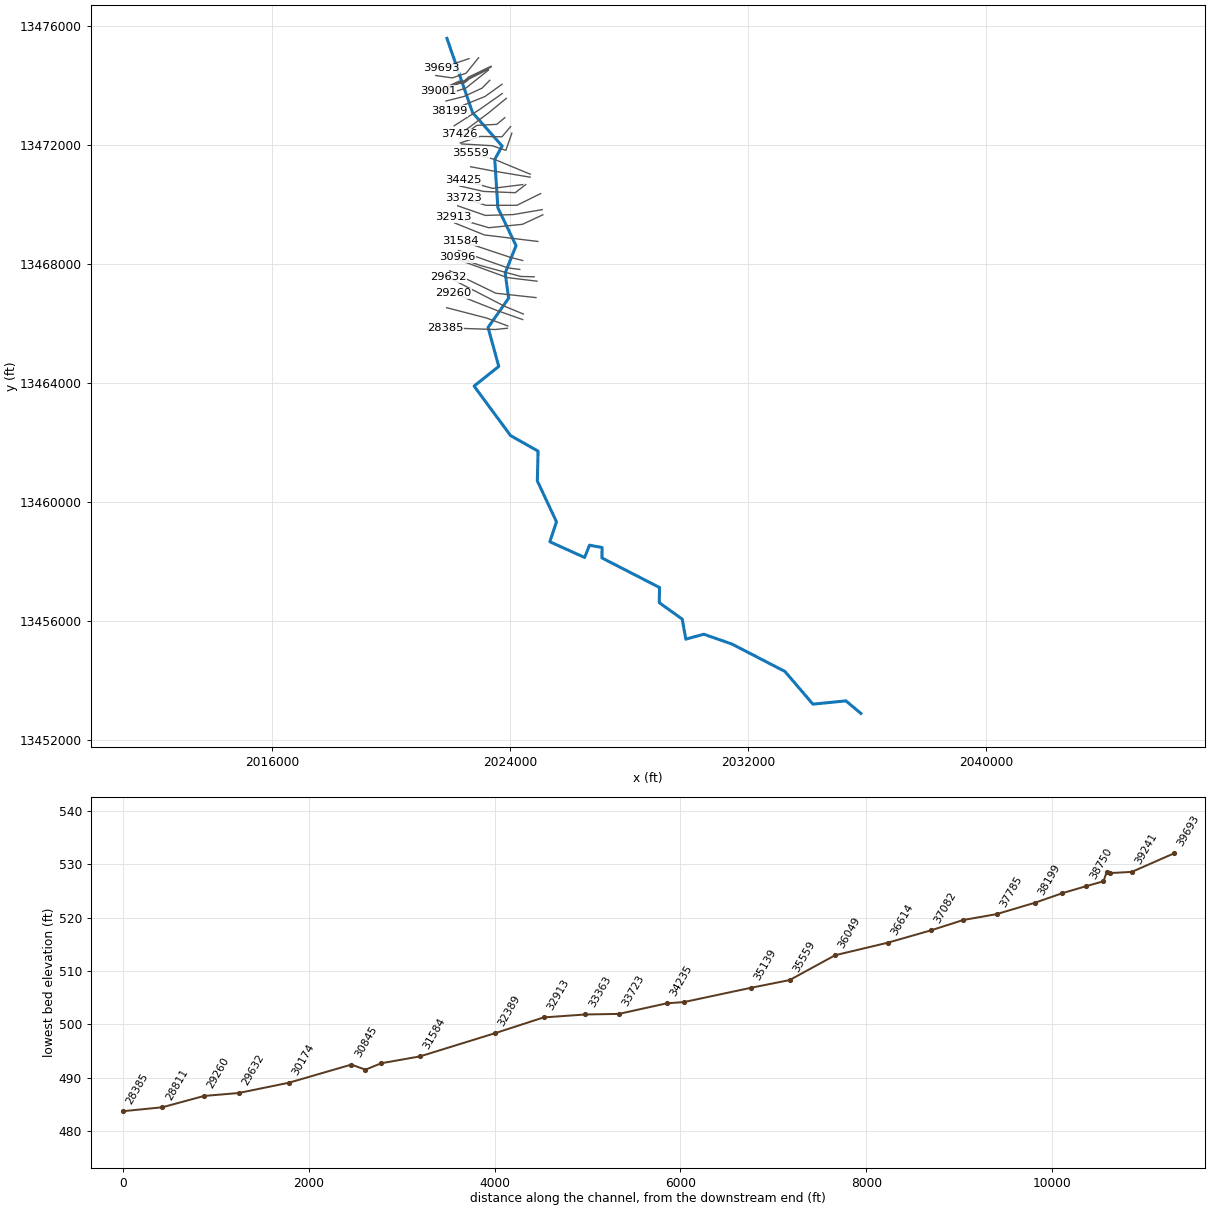
--- UNT 042 in RCW.prj (project) ---

Proj Title=UNT 042 in RCW Base Level Engineering
Current Plan=p01
Default Exp/Contr=0.3,0.1
English Units
Geom File=g01
Flow File=f01
Plan File=p01
Y Axis Title=Elevation
X Axis Title(PF)=Main Channel Distance
X Axis Title(XS)=Station
BEGIN DESCRIPTION:
UNT 042 in RCW
END DESCRIPTION:
DSS Export Rating Curves= 0
DSS Export Rating Curve Sorted= 0
DSS Export Volume Flow Curves= 0
DXF OffsetX= 0
DXF OffsetY= 0
DXF ScaleX= 1
DXF ScaleY= 10

--- UNT 042 in RCW.p01 (plan) ---

Plan Title=Multiple Run
Short Identifier=Multiple
Geom File=g01
Flow File=f01
Subcritical Flow
K Sum by GR= 0
Std Step Tol= 0.01
Critical Tol= 0.01
Num of Std Step Trials= 20
Max Error Tol= 0.3
Flow Tol Ratio= 0.001
Split Flow NTrial= 30
Split Flow Tol= 0.02
Split Flow Ratio= 0.02
Log Output Level= 0
Friction Slope Method= 1
Unsteady Friction Slope Method= 2
Unsteady Bridges Friction Slope Method= 1
Parabolic Critical Depth
Global Vel Dist=  1 , 1 , 1
Global Log Level= 0
CheckData=True
Encroach Param= -1, 0, 0, 0
BEGIN DESCRIPTION:
Multiple Run
END DESCRIPTION:

--- UNT 042 in RCW.f01 (steady flow) ---

Flow Title=Multiple
Program Version=5.05
Number of Profiles= 7
Profile Names=10-year,25-year,50-year,1pct_min,100-year,1pct_plu,500-year
River Rch & RM=UNT 042 in RCW,Reach-1         ,39693
     164     221     267     161     321     640     470
River Rch & RM=UNT 042 in RCW,Reach-1         ,38935
     218     299     364     222     442     882     662
River Rch & RM=UNT 042 in RCW,Reach-1         ,35559
     403     568     706     438     873    1742    1354
River Rch & RM=UNT 042 in RCW,Reach-1         ,34425
     403     568     706     438     873    1742    1354
River Rch & RM=UNT 042 in RCW,Reach-1         ,25859
     474     673     841     523    1044    2083    1634
River Rch & RM=UNT 042 in RCW,Reach-1         ,18431
     540     771     968     604    1205    2403    1896
River Rch & RM=UNT 042 in RCW,Reach-1         ,11519
     601     861    1083     677    1351    2695    2134
River Rch & RM=UNT 042 in RCW,Reach-1         ,2049
     636     914    1151     720    1437    2867    2276
Boundary for River Rch & Prof#=UNT 042 in RCW,Reach-1         , 1
Up Type= 0
Dn Type= 3
Dn Slope=0.005
Boundary for River Rch & Prof#=UNT 042 in RCW,Reach-1         , 2
Up Type= 0
Dn Type= 3
Dn Slope=0.005
Boundary for River Rch & Prof#=UNT 042 in RCW,Reach-1         , 3
Up Type= 0
Dn Type= 3
Dn Slope=0.005
Boundary for River Rch & Prof#=UNT 042 in RCW,Reach-1         , 4
Up Type= 0
Dn Type= 3
Dn Slope=0.005
Boundary for River Rch & Prof#=UNT 042 in RCW,Reach-1         , 5
Up Type= 0
Dn Type= 3
Dn Slope=0.005
Boundary for River Rch & Prof#=UNT 042 in RCW,Reach-1         , 6
Up Type= 0
Dn Type= 3
Dn Slope=0.005
Boundary for River Rch & Prof#=UNT 042 in RCW,Reach-1         , 7
Up Type= 0
Dn Type= 3
Dn Slope=0.005
DSS Import GetInterval= 0
DSS Import GetPeak= 0
DSS Import FillOption= 0

--- UNT 042 in RCW.g01 (geometry) ---

Geom Title=Existing Conditions
Program Version=5.05

River Reach=UNT 042 in RCW  ,Reach-1
Reach XY= 30
      2021879.46     13475591.05       2022740.8     13473094.54
      2023733.21     13471971.77      2023485.82     13471520.38
       2023590.8     13469894.54       2024200.8     13468624.54
      2023837.29     13467704.66       2023950.8     13466854.54
       2023260.8     13465874.54       2023620.8     13464564.54
       2022790.8     13463904.54      2024017.46     13462240.15
      2024940.99     13461718.02      2024915.81     13460716.29
      2025559.04     13459342.16      2025335.56      13458672.8
      2026504.31     13458143.63      2026667.33     13458557.17
      2027090.77     13458478.53      2027087.12     13458128.01
       2029020.8     13457134.54       2029010.8     13456624.54
      2029782.34     13456072.43      2029902.13     13455398.82
      2030507.95     13455564.15       2031450.8     13455234.54
       2033230.8     13454314.54       2034170.8     13453214.54
       2035280.8     13453324.54       2035780.8     13452904.54

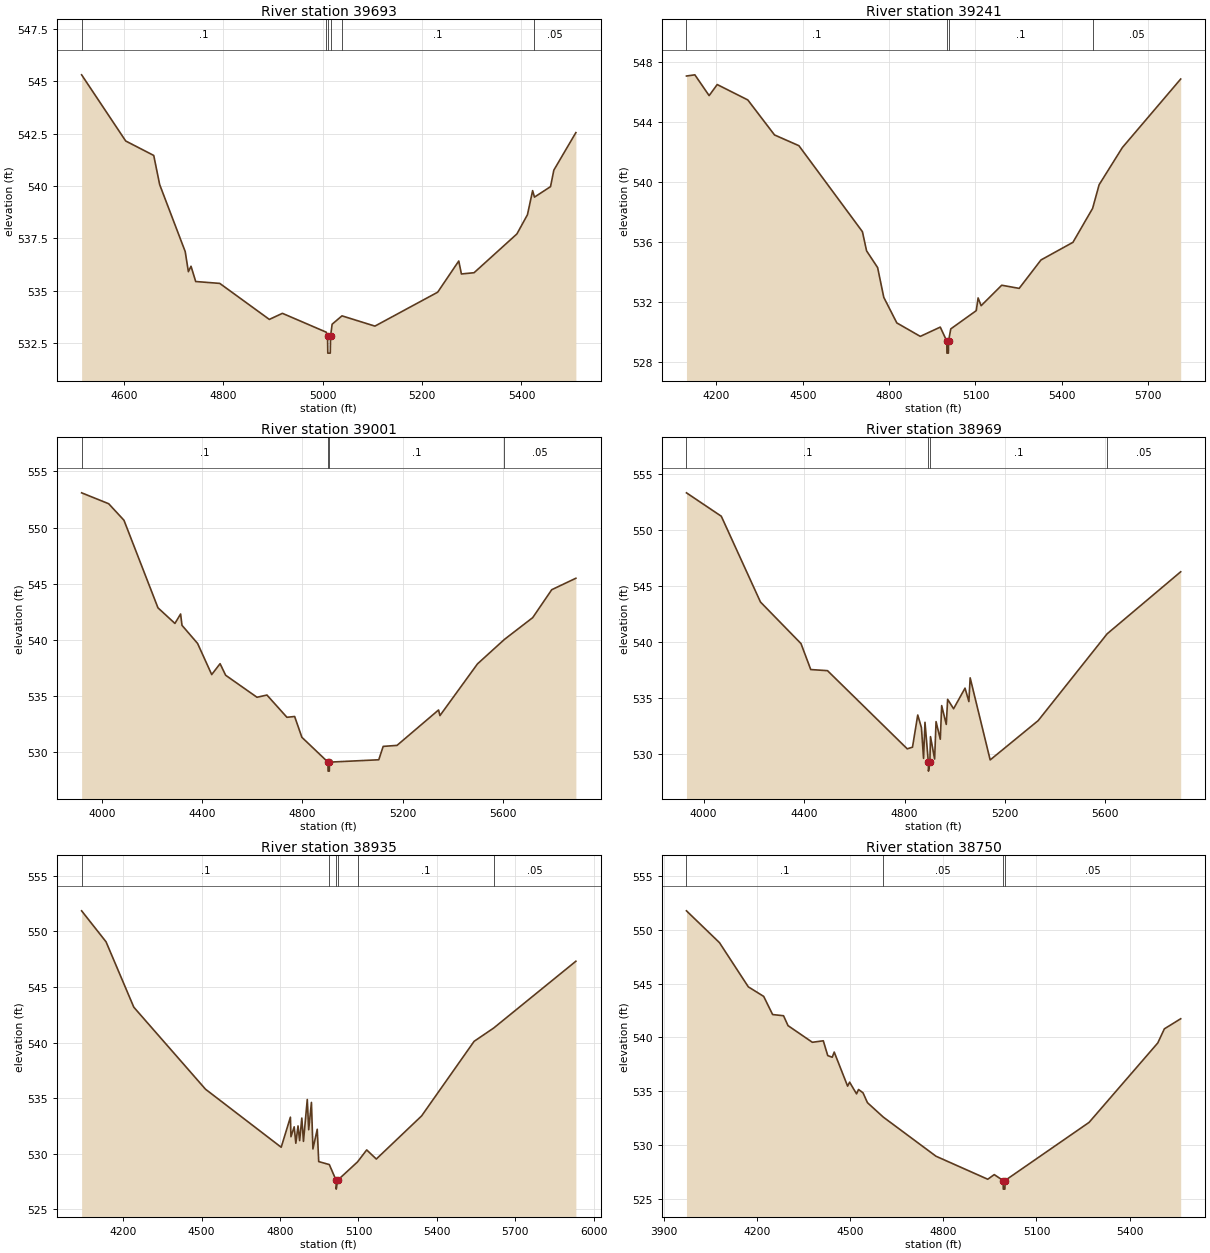
Type RM Length L Ch R = 1 ,39693   ,452,452,452
BEGIN DESCRIPTION:
UNT 042 in RCW 66.0
END DESCRIPTION:
XS GIS Cut Line= 3
      2022622.54     13474908.77      2022178.07     13474759.45
      2021683.28     13474582.37
#Sta/Elev= 30
  4515.1  545.31  4603.8  542.15  4660.2  541.46  4672.1  540.07  4723.5  536.87
  4729.9  535.91  4735.2  536.17  4744.6  535.44    4793  535.35  4892.8  533.63
  4919.1  533.92  5007.3  533.02  5009.9  532.82  5010.4  532.02  5015.4  532.02
  5015.9  532.82  5019.1   533.4  5038.9   533.8  5105.2  533.31  5231.5  534.93
  5273.9  536.42  5279.2   535.8  5304.7  535.86  5390.8  537.71  5412.1  538.63
  5422.5  539.78  5426.2  539.47  5458.5  539.97  5465.2  540.76  5509.5  542.55
#Mann= 6 ,-1 , 0
  4515.1      .1       0  5007.3     .12       0  5009.9     .07       0
  5015.9     .12       0  5038.9      .1       0  5426.2     .05       0
Bank Sta=5009.9,5015.9
XS Rating Curve= 0 ,0
Exp/Cntr=0.3,0.1

Type RM Length L Ch R = 1 ,39241   ,240,240,240
BEGIN DESCRIPTION:
UNT 042 in RCW 65.0
END DESCRIPTION:
XS GIS Cut Line= 4
      2022941.94     13474938.26      2022525.29     13474420.91
      2022060.01     13474261.19      2021504.42     13474341.06
#Sta/Elev= 30
  4095.8  547.09    4125  547.17  4174.6  545.78  4202.7  546.52    4309  545.49
  4401.8  543.15  4486.6  542.43  4707.3  536.68  4721.7   535.4  4760.1  534.28
  4781.5  532.29  4826.8  530.58  4908.4  529.68  4977.8   530.3  5000.5  529.36
    5001  528.56    5006  528.56  5006.5  529.36  5014.3  530.18  5102.8   531.4
  5109.3  532.25  5119.8  531.73  5191.3   533.1    5252  532.89  5327.8  534.79
  5438.9  535.97  5507.2  538.24  5529.8  539.82  5610.7  542.31  5813.3  546.89
#Mann= 4 ,-1 , 0
  4095.8      .1       0  5000.5     .07       0  5006.5      .1       0
  5507.2     .05       0
Bank Sta=5000.5,5006.5
XS Rating Curve= 0 ,0
Exp/Cntr=0.3,0.1

Type RM Length L Ch R = 1 ,39001   ,32,32,32
BEGIN DESCRIPTION:
Mapping XS 17f29ef6
END DESCRIPTION:
XS GIS Cut Line= 6
      2023362.12     13474653.56      2022608.63     13474288.97
      2022473.21     13474170.91      2022389.88     13474139.66
      2022292.65     13474153.55      2021599.08     13473831.04
#Sta/Elev= 30
  3919.9  553.09  4027.8  552.12  4088.8  550.65  4224.4  542.86  4292.1  541.47
  4314.7  542.31  4320.3   541.3  4382.5  539.69  4438.8  536.92  4472.2  537.89
  4494.4  536.86  4619.5   534.9  4659.1   535.1  4738.8  533.12  4769.6  533.19
  4798.5  531.34  4902.5  529.13    4903  528.33    4908  528.33  4908.5  529.13
  5105.2  529.34  5122.8  530.53    5178  530.62  5343.7  533.77  5349.2  533.27
  5498.9  537.87    5606  540.04  5719.4  541.99  5795.1  544.47  5891.4  545.49
#Mann= 4 ,-1 , 0
  3919.9      .1       0  4902.5     .07       0  4908.5      .1       0
    5606     .05       0
Bank Sta=4902.5,4908.5
XS Rating Curve= 0 ,0
Exp/Cntr=0.3,0.1

Type RM Length L Ch R = 1 ,38969   ,34,34,34
BEGIN DESCRIPTION:
Mapping XS 8bcd229d
END DESCRIPTION:
XS GIS Cut Line= 6
      2023358.62     13474625.77      2022608.63     13474243.83
      2022483.63     13474143.13      2022417.65     13474115.36
      2022278.76     13474108.41      2021599.08     13473785.91
#Sta/Elev= 30
  3931.8   553.3  4070.5  551.21  4226.5  543.55  4387.8  539.84  4426.7  537.52
  4493.4  537.42  4810.9  530.44  4831.8  530.59  4852.7  533.46  4867.4  532.33
  4875.8  529.59  4881.5  532.81  4894.9  529.25  4895.4  528.45  4900.9  529.25
  4903.5  531.53  4919.9  529.53  4925.6  532.87  4942.5   531.3    4948   534.3
  4966.3  532.62  4971.7  534.86  4995.4  534.02    5041  535.86  5056.3  534.66
  5061.4  536.78  5141.1  529.45  5332.2  532.96  5606.8  540.71  5899.7  546.25
#Mann= 4 ,-1 , 0
  3931.8      .1       0  4894.9     .07       0  4900.9      .1       0
  5606.8     .05       0
Bank Sta=4894.9,4900.9
XS Rating Curve= 0 ,0
Exp/Cntr=0.3,0.1

Type RM Length L Ch R = 1 ,38935   ,185,185,185
BEGIN DESCRIPTION:
Mapping XS 9473ed53
END DESCRIPTION:
XS GIS Cut Line= 6
      2023268.36     13474549.39       2022636.4     13474233.41
       2022511.4     13474125.77      2022417.65     13474077.16
      2022292.65     13474080.63      2021588.92     13473727.04
#Sta/Elev= 30
  4041.4  551.86  4134.8  549.07    4241  543.18    4515   535.8  4804.6  530.57
  4839.8  533.28  4841.9  531.52  4854.3  532.41  4860.5  530.93  4868.9  532.49
  4875.1  531.17  4883.4   533.2  4889.7   531.1  4904.3  534.87  4909.7  532.15
  4920.2  534.61  4925.9  530.42  4942.4  532.19    4948  529.28  4988.6  529.01
  5014.5   527.6    5015   526.8  5020.5   527.6  5096.4  529.25  5131.5  530.33
  5168.3  529.51  5341.4  533.39  5542.3  540.11  5616.8   541.3  5931.4  547.32
#Mann= 6 ,-1 , 0
  4041.4      .1       0  4988.6     .05       0  5014.5     .03       0
  5020.5     .05       0  5096.4      .1       0  5616.8     .05       0
Bank Sta=5014.5,5020.5
XS Rating Curve= 0 ,0
Exp/Cntr=0.3,0.1

Type RM Length L Ch R = 1 ,38750   ,260,260,260
BEGIN DESCRIPTION:
UNT 042 in RCW 64.0
END DESCRIPTION:
XS GIS Cut Line= 3
      2023274.97     13474524.97        2022525.       13473925.
      2021924.98     13473724.99
#Sta/Elev= 30
  3971.9  551.78  4078.3  548.82  4171.2  544.71  4220.8  543.82  4249.6  542.13
  4284.8  542.02  4299.2   541.1  4377.7  539.55  4412.9  539.69  4427.3  538.31
  4441.7  538.16  4448.1  538.64  4491.3  535.47  4497.7  535.84  4520.1  534.75
  4526.5  535.16  4540.9  534.85  4555.3  533.93  4606.3  532.59  4776.2  528.95
  4942.9  526.81  4963.9  527.24  4992.5  526.69    4993  525.89  4998.2  525.89
  4998.7  526.69  5269.6   532.1    5491  539.49  5512.1   540.8  5564.8  541.74
#Mann= 4 ,-1 , 0
  3971.9      .1       0  4606.3     .05       0  4992.5     .03       0
  4998.7     .05       0
Bank Sta=4992.5,4998.7
XS Rating Curve= 0 ,0
Exp/Cntr=0.3,0.1

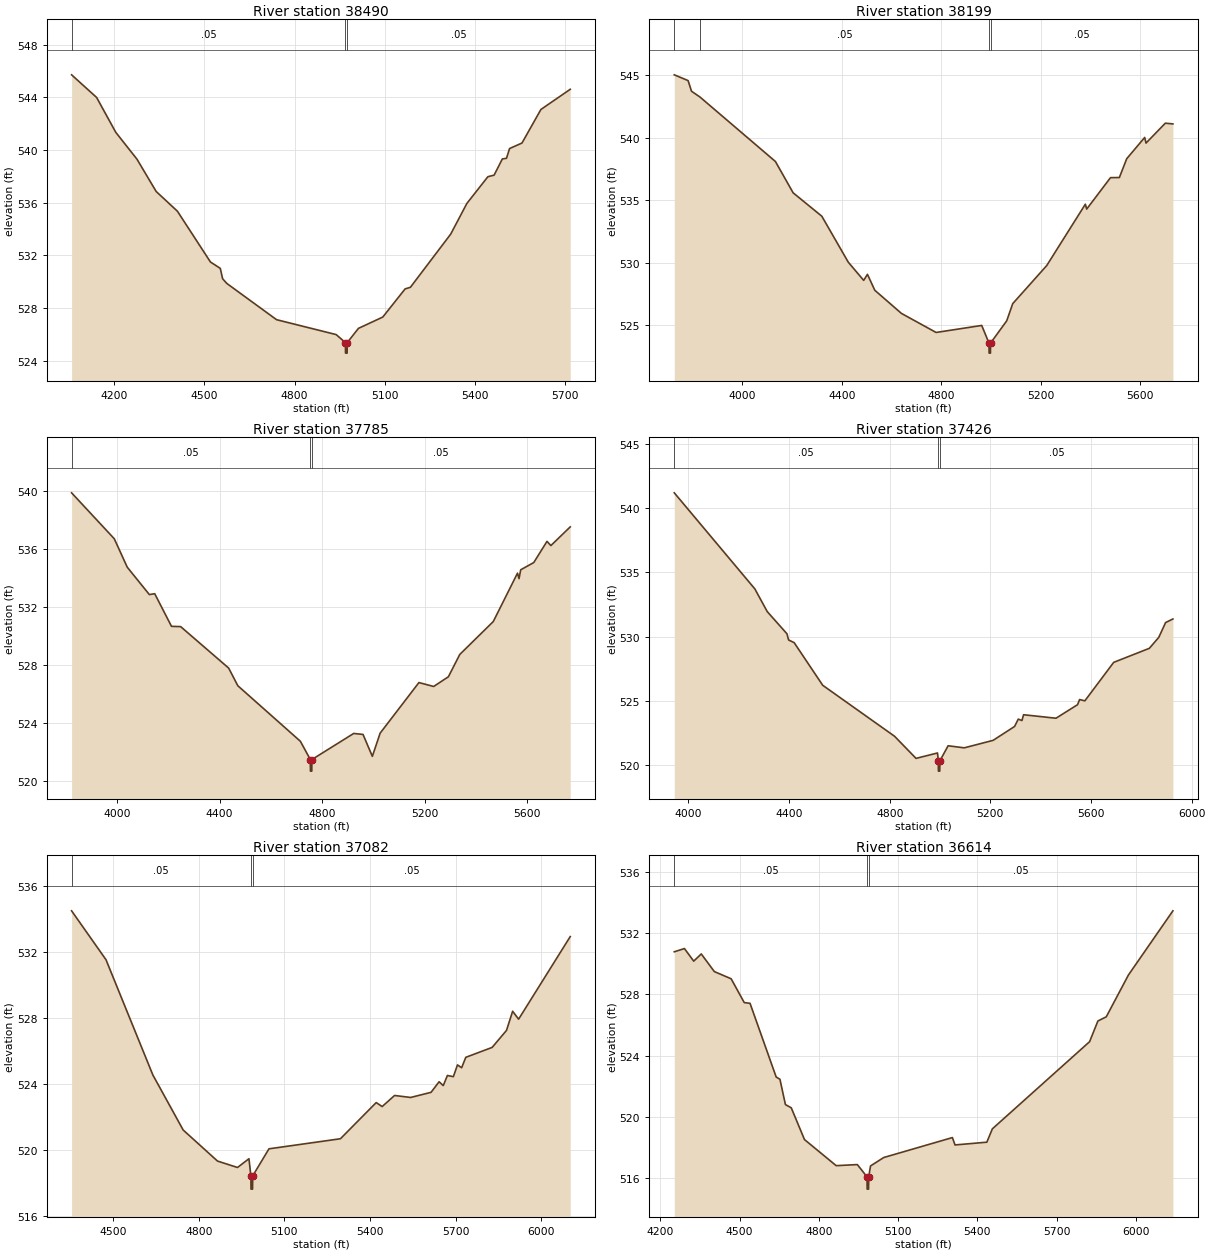
Type RM Length L Ch R = 1 ,38490   ,291,291,291
BEGIN DESCRIPTION:
Mapping XS d56779f3
END DESCRIPTION:
XS GIS Cut Line= 4
       2023317.5     13474180.36      2023059.69     13473917.34
      2022458.13      13473638.7      2021849.34      13473485.2
#Sta/Elev= 30
    4058   545.7  4141.3  543.98  4205.1  541.33  4275.6  539.29  4339.4  536.84
  4410.1  535.34  4520.1  531.48  4552.7     531  4560.5  530.21  4574.7  529.85
    4740   527.1  4938.2  525.97    4969  525.36  4969.5  524.56  4974.7  524.56
  4975.2  525.36  5012.4  526.44  5093.4   527.3  5167.8  529.44  5185.3  529.56
  5319.4   533.6  5373.2  535.93  5443.1  537.96  5463.8  538.08  5491.2  539.31
    5505  539.36  5515.3   540.1  5556.6  540.52  5619.6  543.07  5717.1   544.6
#Mann= 3 ,-1 , 0
    4058     .05       0    4969     .03       0  4975.2     .05       0
Bank Sta=4969,4975.2
XS Rating Curve= 0 ,0
Exp/Cntr=0.3,0.1

Type RM Length L Ch R = 1 ,38199   ,414,414,414
BEGIN DESCRIPTION:
UNT 042 in RCW 63.0
END DESCRIPTION:
XS GIS Cut Line= 3
      2023730.17     13474047.66      2023160.71     13473637.93
      2021952.37     13473148.34
#Sta/Elev= 30
  3726.7  545.01  3782.3  544.55    3796   543.7  3829.9  543.24  4133.5  538.09
  4204.7  535.59  4320.1  533.72  4426.5  530.05  4488.4   528.6  4503.6  529.08
  4533.1  527.81  4640.3  525.96  4779.7  524.44  4963.1     525  4992.4  523.59
  4992.9  522.79  4998.1  522.79  4998.6  523.59  5063.7  525.37  5087.8  526.74
  5224.5  529.78  5379.9  534.68  5385.3  534.29    5481   536.8  5516.7  536.81
  5546.2  538.31  5618.5  540.01  5623.9  539.56  5701.6  541.15    5732  541.09
#Mann= 4 ,-1 , 0
  3726.7      .1       0  3829.9     .05       0  4992.4     .03       0
  4998.6     .05       0
Bank Sta=4992.4,4998.6
XS Rating Curve= 0 ,0
Exp/Cntr=0.3,0.1

Type RM Length L Ch R = 1 ,37785   ,359,359,359
BEGIN DESCRIPTION:
UNT 042 in RCW 62.0
END DESCRIPTION:
XS GIS Cut Line= 3
       2023737.1     13473735.15      2022966.26     13473193.48
      2022122.49      13472651.8
#Sta/Elev= 30
  3823.1  539.85  3989.6  536.68  4040.2  534.72  4126.4  532.83  4147.3  532.89
  4212.7  530.64  4248.4  530.62  4435.7  527.76  4471.5  526.54  4715.4  522.71
  4754.2  521.45  4754.7  520.65  4759.9  520.65  4760.4  521.45  4923.4  523.25
  4959.8  523.18  4996.1  521.67  5026.5  523.27  5177.8  526.76  5235.3  526.49
  5292.7  527.16  5337.1   528.7  5467.8  530.97  5562.3  534.31  5568.2  533.93
  5574.8  534.54  5625.7  535.04  5677.2   536.5  5692.4  536.21  5767.9   537.5
#Mann= 3 ,-1 , 0
  3823.1     .05       0  4754.2     .03       0  4760.4     .05       0
Bank Sta=4754.2,4760.4
XS Rating Curve= 0 ,0
Exp/Cntr=0.3,0.1

Type RM Length L Ch R = 1 ,37426   ,344,344,344
BEGIN DESCRIPTION:
UNT 042 in RCW 61.0
END DESCRIPTION:
XS GIS Cut Line= 3
      2023875.03     13473575.03      2023278.76     13473085.84
      2022309.99     13472360.13
#Sta/Elev= 30
  3943.8  541.17  4263.9  533.71  4313.4  531.94  4391.6  530.22  4398.1  529.74
  4420.3  529.53  4533.7  526.22  4819.2  522.26  4904.6  520.54    4990  520.96
  4993.1  520.35  4993.6  519.55  4998.9  519.55  4999.4  520.35  5032.1  521.52
  5096.3  521.36  5210.9  521.94  5296.3  523.02  5310.9  523.59  5325.5  523.48
    5332  523.93  5460.9  523.66  5546.4  524.71  5554.7  525.11  5575.5  525.01
  5690.2     528  5831.8  529.09  5869.3  529.94  5896.4  531.09  5925.5  531.37
#Mann= 3 ,-1 , 0
  3943.8     .05       0  4993.1     .03       0  4999.4     .05       0
Bank Sta=4993.1,4999.4
XS Rating Curve= 0 ,0
Exp/Cntr=0.3,0.1

Type RM Length L Ch R = 1 ,37082   ,468,468,468
BEGIN DESCRIPTION:
UNT 042 in RCW 60.0
END DESCRIPTION:
XS GIS Cut Line= 4
      2023825.04     13472925.03      2023553.07     13472700.43
       2022877.4     13472664.74      2022307.71      13472229.1
#Sta/Elev= 30
  4354.6  534.48  4475.1  531.52  4639.3  524.54  4745.4  521.21  4865.6  519.33
  4935.7  518.94  4975.8  519.47  4982.6  518.43  4983.1  517.63  4988.4  517.63
  4988.9  518.43  5045.9  520.07  5296.2  520.68  5421.5  522.87  5442.4  522.63
  5485.9   523.3  5542.1  523.18  5613.6  523.49  5641.8  524.13  5656.4   523.9
  5670.9  524.51  5691.7  524.44  5706.2  525.15  5720.8  524.98  5735.3  525.61
  5827.6  526.21  5877.9  527.24  5899.4   528.4  5920.3  527.92  6101.1  532.92
#Mann= 3 ,-1 , 0
  4354.6     .05       0  4982.6     .03       0  4988.9     .05       0
Bank Sta=4982.6,4988.9
XS Rating Curve= 0 ,0
Exp/Cntr=0.3,0.1

Type RM Length L Ch R = 1 ,36614   ,565,565,565
BEGIN DESCRIPTION:
UNT 042 in RCW 59.0
END DESCRIPTION:
XS GIS Cut Line= 4
        2024018.     13472625.64      2023728.97     13472281.93
       2022999.8     13472294.95      2022325.01       13472075.
#Sta/Elev= 30
  4252.7  530.77  4291.2  530.98  4326.3  530.16  4354.9  530.63  4404.4  529.48
  4468.1  529.01  4517.6  527.46  4539.6  527.41  4638.5  522.61  4652.8  522.46
  4673.6  520.81  4695.7   520.6  4745.8  518.53  4865.8  516.83  4945.8   516.9
  4982.6   516.1  4983.1   515.3  4988.4   515.3  4988.9   516.1  4995.8  516.81
  5045.8  517.36  5305.8  518.66  5315.8  518.18  5436.2  518.36  5457.2  519.23
  5825.3  524.91  5856.8  526.26  5888.4  526.53  5972.5  529.26  6140.8  533.44
#Mann= 3 ,-1 , 0
  4252.7     .05       0  4982.6     .03       0  4988.9     .05       0
Bank Sta=4982.6,4988.9
XS Rating Curve= 0 ,0
Exp/Cntr=0.3,0.1

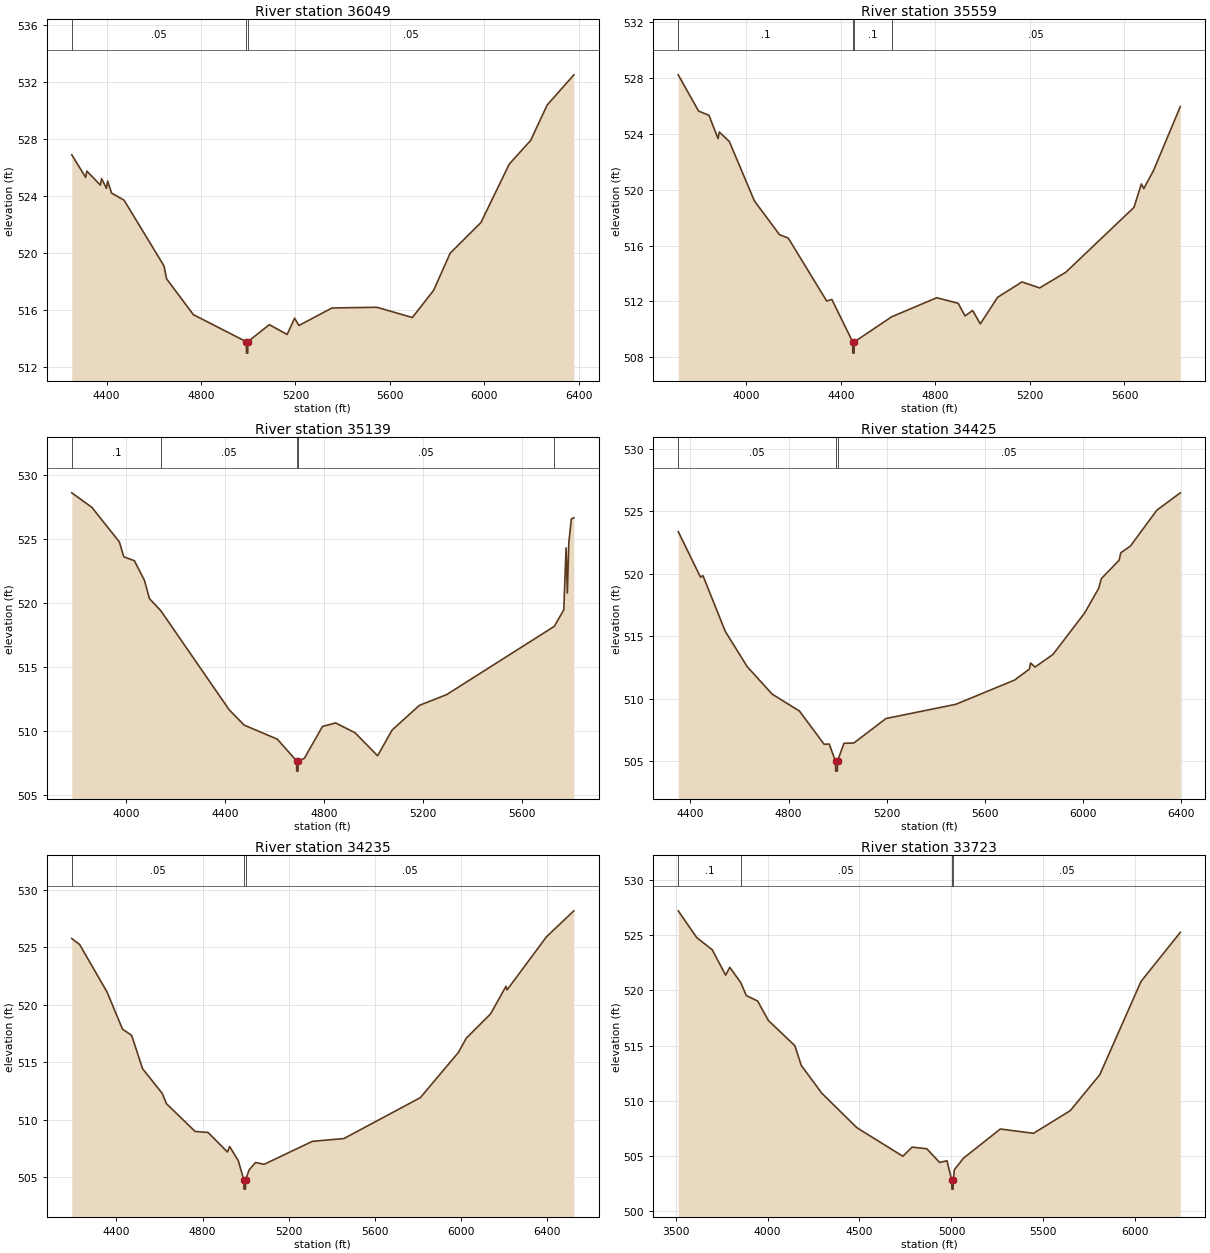
Type RM Length L Ch R = 1 ,36049   ,490,490,490
BEGIN DESCRIPTION:
Mapping XS 701f47c9
END DESCRIPTION:
XS GIS Cut Line= 4
      2024059.68     13472404.28      2023859.17      13471826.2
      2023400.84     13471982.45      2022372.19     13472042.35
#Sta/Elev= 30
  4252.5  526.89  4311.3   525.3  4316.5  525.74  4373.5  524.76  4378.8  525.21
  4399.4  524.53  4404.7  525.04  4421.1   524.2    4474   523.7  4643.2  519.08
    4654  518.18  4767.7  515.66    4992  513.76  4992.5  512.96  4997.8  512.96
  4998.3  513.76  5089.2  514.96  5164.6  514.27  5196.3  515.41  5214.6   514.9
  5354.5  516.13  5544.8  516.18    5695  515.46  5785.2  517.37  5855.3  519.98
  5985.5  522.13  6105.7  526.24  6195.9  527.89    6266  530.38    6379   532.5
#Mann= 3 ,-1 , 0
  4252.5     .05       0    4992     .03       0  4998.3     .05       0
Bank Sta=4992,4998.3
XS Rating Curve= 0 ,0
Exp/Cntr=0.3,0.1

Type RM Length L Ch R = 1 ,35559   ,420,420,420
BEGIN DESCRIPTION:
UNT 042 in RCW 57.0
END DESCRIPTION:
XS GIS Cut Line= 3
      2024674.97     13471025.01        2023475.       13471525.
      2022674.99       13471725.
#Sta/Elev= 30
  3711.8   528.2  3797.9  525.61  3841.8  525.31  3880.2  523.64  3885.6  524.11
  3927.9  523.44  4034.1  519.19  4140.2  516.78  4177.6  516.53  4340.1  512.03
  4361.8  512.15  4450.1  509.11  4450.6  508.31    4456  508.31  4456.5  509.11
  4615.4  510.91  4805.9  512.27  4896.4  511.87  4925.6  510.97  4957.6  511.36
  4990.1   510.4  5063.3   512.3  5166.4   513.4  5241.1  512.97  5351.9  514.09
  5640.5  518.73  5671.5   520.4  5681.8  520.07    5723  521.36  5836.4  525.93
#Mann= 4 ,-1 , 0
  3711.8      .1       0  4450.1     .03       0  4456.5      .1       0
  4615.4     .05       0
Bank Sta=4450.1,4456.5
XS Rating Curve= 0 ,0
Exp/Cntr=0.3,0.1

Type RM Length L Ch R = 1 ,35139   ,714,714,714
BEGIN DESCRIPTION:
UNT 042 in RCW 56.0
END DESCRIPTION:
XS GIS Cut Line= 3
      2024674.97       13470925.        2023475.       13471125.
      2022674.97     13471275.01
#Sta/Elev= 30
  3779.2  528.61  3860.3  527.48  3971.8  524.77  3989.5  523.61  4032.6   523.3
  4073.2  521.76  4093.4  520.34  4139.5  519.39  4415.3  511.66  4476.2  510.45
  4610.5  509.35  4688.3  507.65  4688.8  506.85  4694.3  506.85  4694.8  507.65
  4719.5  507.84    4793  510.34  4846.2  510.62  4924.8  509.85  5016.1  508.05
  5074.6  510.06  5184.8  511.99    5295  512.83  5730.6  518.17    5769  519.46
  5778.3  524.31  5783.4  520.78  5789.3  524.68  5799.5  526.56  5809.7  526.66
#Mann= 5 ,-1 , 0
  3779.2      .1       0  4139.5     .05       0  4688.3     .03       0
  4694.8     .05       0  5730.6      .1       0
Bank Sta=4688.3,4694.8
XS Rating Curve= 0 ,0
Exp/Cntr=0.3,0.1

Type RM Length L Ch R = 1 ,34425   ,190,190,190
BEGIN DESCRIPTION:
UNT 042 in RCW 55.0
END DESCRIPTION:
XS GIS Cut Line= 3
      2024425.04       13470675.      2023410.28     13470549.38
      2022425.01       13470825.
#Sta/Elev= 30
  4350.2  523.37  4440.9  519.72    4451  519.84  4541.7  515.39  4631.2  512.56
  4733.1  510.36    4844  509.01  4944.7  506.35  4965.3  506.37    4991     505
  4991.7   504.2  4998.5   504.2  4999.2     505  5025.4  506.43  5065.7  506.45
  5196.7  508.41  5481.6  509.55  5720.9  511.49  5780.6  512.36  5785.8  512.85
  5803.9  512.53  5876.6  513.53  6006.2  516.86  6063.5  518.84  6073.9   519.6
  6146.6  521.08  6153.2  521.67  6192.5  522.21  6300.1  525.08  6395.8  526.47
#Mann= 3 ,-1 , 0
  4350.2     .05       0    4991     .03       0  4999.2     .05       0
Bank Sta=4991,4999.2
XS Rating Curve= 0 ,0
Exp/Cntr=0.3,0.1

Type RM Length L Ch R = 1 ,34235   ,512,512,512
BEGIN DESCRIPTION:
UNT 042 in RCW 54.0
END DESCRIPTION:
XS GIS Cut Line= 4
      2024524.97     13470674.98      2024174.16     13470403.55
      2023115.14     13470445.22      2022308.05      13470628.8
#Sta/Elev= 30
  4192.8  525.76    4229  525.25  4357.1  521.09  4428.2  517.88  4470.9  517.33
  4521.5  514.43  4612.9  512.28  4632.7  511.38  4765.6  508.97  4825.7  508.88
  4915.7  507.18  4925.7  507.66  4965.8  506.43  4991.7  504.75  4992.4  503.95
  4999.2  503.95  4999.9  504.75  5015.8  505.61  5045.8  506.27  5085.9  506.11
  5310.1  508.11  5456.2  508.35  5811.1  511.91  5988.4  515.86  6024.5  517.09
  6137.3   519.2  6208.8   521.6    6214  521.29  6396.4   525.9  6523.9  528.17
#Mann= 3 ,-1 , 0
  4192.8     .05       0  4991.7     .03       0  4999.9     .05       0
Bank Sta=4991.7,4999.9
XS Rating Curve= 0 ,0
Exp/Cntr=0.3,0.1

Type RM Length L Ch R = 1 ,33723   ,360,360,360
BEGIN DESCRIPTION:
UNT 042 in RCW 53.0
END DESCRIPTION:
XS GIS Cut Line= 4
      2025024.86      13470372.3      2024229.72     13469979.94
      2023184.58     13469979.94      2022424.95     13470225.01
#Sta/Elev= 30
  3514.4  527.21  3615.1  524.78  3699.3  523.68  3772.2  521.38  3794.7  522.09
  3854.5   520.7  3884.5  519.53  3946.3  519.03  4004.9  517.26  4148.3  514.99
  4183.3   513.2  4294.8  510.68  4485.8  507.55  4735.8  504.96  4785.8  505.79
  4865.8  505.64  4935.8   504.4  4975.8  504.55  5001.6  502.78  5002.3  501.98
  5009.2  501.98  5009.9  502.78  5015.8  503.74  5065.8  504.79  5265.8  507.43
  5446.2  507.04  5646.3   509.1  5806.5  512.35  6030.8  520.81  6244.4  525.26
#Mann= 4 ,-1 , 0
  3514.4      .1       0  3854.5     .05       0  5001.6     .03       0
  5009.9     .05       0
Bank Sta=5001.6,5009.9
XS Rating Curve= 0 ,0
Exp/Cntr=0.3,0.1

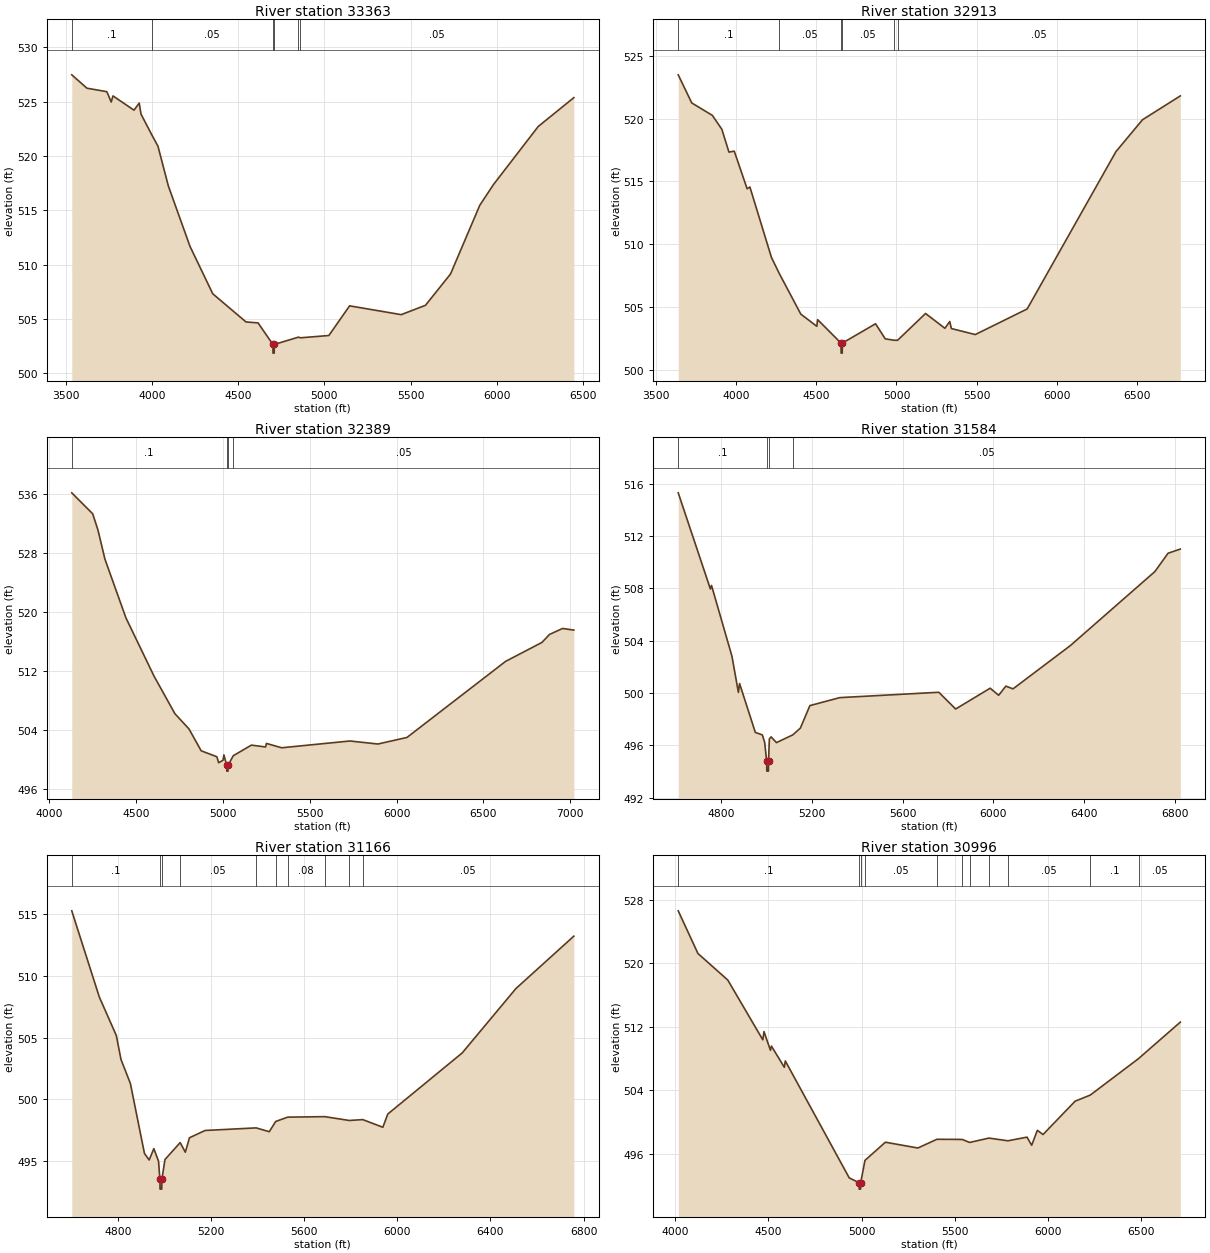
Type RM Length L Ch R = 1 ,33363   ,450,450,450
BEGIN DESCRIPTION:
UNT 042 in RCW 52.0
END DESCRIPTION:
XS GIS Cut Line= 4
      2025080.41     13469834.11      2024101.25     13469667.44
      2023170.69     13469639.66      2022240.14     13469962.58
#Sta/Elev= 30
  3536.1  527.47    3624  526.24  3739.4  525.92  3764.7  524.97  3774.9  525.53
  3896.6  524.22    3927  524.87  3937.2  523.86  3998.2     522  4035.4  520.91
  4095.7  517.25  4221.2  511.69  4353.1  507.33  4545.6  504.74  4615.6  504.65
  4701.5  502.67  4702.2  501.87  4709.1  501.87  4709.8  502.67  4849.5  503.34
  4861.3  503.28  5025.8  503.49  5145.9  506.22    5445  505.41  5585.7  506.27
  5730.8  509.15  5900.3  515.47  5979.8  517.38    6239  522.72  6445.3  525.37
#Mann= 6 ,-1 , 0
  3536.1      .1       0  3998.2     .05       0  4701.5     .03       0
  4709.8     .05       0  4849.5     .12       0  4861.3     .05       0
Bank Sta=4701.5,4709.8
XS Rating Curve= 0 ,0
Exp/Cntr=0.3,0.1

Type RM Length L Ch R = 1 ,32913   ,524,524,524
BEGIN DESCRIPTION:
Mapping XS 18bb6e93
END DESCRIPTION:
XS GIS Cut Line= 4
      2025101.28     13469660.51      2024417.22     13469341.05
      2023288.75     13469226.47      2022098.84     13469573.38
#Sta/Elev= 30
  3640.1   523.5  3724.3  521.26  3852.6  520.27  3911.9  519.16  3956.1  517.34
  3989.2  517.42  4069.3  514.42  4086.7  514.56  4220.9  508.95  4269.6  507.67
  4403.9  504.43  4503.7  503.46  4508.7  503.99  4654.4  502.12  4655.2  501.32
  4662.1  501.32  4662.8  502.12  4869.7  503.66    4930  502.46  4983.7  502.35
  5006.7  502.34  5181.3  504.48  5301.9   503.3  5332.1  503.84  5342.1  503.28
  5491.1   502.8  5814.5  504.84  6367.7  517.38  6533.2  519.92  6768.8  521.82
#Mann= 6 ,-1 , 0
  3640.1      .1       0  4269.6     .05       0  4654.4     .07       0
  4662.8     .05       0  4983.7     .12       0  5006.7     .05       0
Bank Sta=4654.4,4662.8
XS Rating Curve= 0 ,0
Exp/Cntr=0.3,0.1

Type RM Length L Ch R = 1 ,32389   ,805,805,805
BEGIN DESCRIPTION:
Mapping XS 36452057
END DESCRIPTION:
XS GIS Cut Line= 3
      2024934.61     13468764.66      2023139.44     13468983.41
      2022134.78     13469386.34
#Sta/Elev= 30
  4129.8  536.13  4250.3  533.29  4280.5  531.09  4320.8  527.13  4441.7  519.16
  4602.9  511.28  4723.8  506.15  4804.4   504.1  4874.9  501.12  4965.5  500.31
  4975.6   499.5  5000.7  499.84  5005.8  500.56  5021.7  499.16  5022.5  498.36
  5029.5  498.36  5030.2  499.16  5059.6  500.45    5164  501.89  5245.6  501.64
  5250.7  502.12  5338.3  501.53  5731.2  502.45  5892.4  502.04  6059.8  502.93
  6627.4  513.25  6837.2  515.83  6880.4  516.91  6955.8  517.72  7020.7   517.5
#Mann= 4 ,-1 , 0
  4129.8      .1       0  5021.7     .07       0  5030.2      .1       0
  5059.6     .05       0
Bank Sta=5021.7,5030.2
XS Rating Curve= 0 ,0
Exp/Cntr=0.3,0.1

Type RM Length L Ch R = 1 ,31584   ,418,418,418
BEGIN DESCRIPTION:
UNT 042 in RCW 51.0
END DESCRIPTION:
XS GIS Cut Line= 3
      2024425.04     13468124.99        2024025.       13468225.
      2022314.83      13468795.9
#Sta/Elev= 30
  4609.3  515.31  4751.1  507.96  4756.2  508.23  4846.4  502.81  4874.8  500.05
  4879.9  500.73  4949.5  496.99  4980.4   496.8  4990.7  496.23  4999.3  494.83
  5000.1  494.03  5007.2  494.03  5007.9  494.83  5011.3  496.49  5019.1  496.65
  5042.7  496.21  5114.6   496.8  5148.2  497.32  5190.2  499.04  5321.9  499.65
  5759.1  500.06  5833.4  498.78  5985.6  500.37  6023.2  499.83  6054.8  500.53
  6086.4  500.32  6339.5  503.63  6712.5  509.29  6770.4  510.69  6824.6  511.01
#Mann= 4 ,-1 , 0
  4609.3      .1       0  4999.3     .07       0  5007.9      .1       0
  5114.6     .05       0
Bank Sta=4999.3,5007.9
XS Rating Curve= 0 ,0
Exp/Cntr=0.3,0.1

Type RM Length L Ch R = 1 ,31166   ,170,170,170
BEGIN DESCRIPTION:
UNT 042 in RCW 50.0
END DESCRIPTION:
XS GIS Cut Line= 3
      2024325.01       13467825.        2023925.       13467875.
      2022271.42      13468461.7
#Sta/Elev= 30
  4600.8  515.28  4719.2   508.3  4792.3  505.18  4812.4  503.24  4852.8  501.29
  4913.2  495.63  4933.4   495.1  4953.5  496.02  4973.7     495  4979.5  493.54
  4980.2  492.74  4987.3  492.74  4988.1  493.54  5001.4  495.14  5066.7  496.51
  5088.8  495.73  5106.7   496.9  5173.7  497.49  5393.4   497.7  5449.6  497.39
  5477.2  498.22  5528.7  498.57  5688.2  498.61  5793.6   498.3  5851.4  498.37
  5937.7  497.75  5958.9  498.82  6278.7  503.77  6509.8  508.99  6758.5  513.23
#Mann= 10 ,-1 , 0
  4600.8      .1       0  4979.5     .07       0  4988.1      .1       0
  5066.7     .05       0  5393.4     .08       0  5477.2      .1       0
  5528.7     .08       0  5688.2      .1       0  5793.6     .08       0
  5851.4     .05       0
Bank Sta=4979.5,4988.1
XS Rating Curve= 0 ,0
Exp/Cntr=0.3,0.1

Type RM Length L Ch R = 1 ,30996   ,151,151,151
BEGIN DESCRIPTION:
Mapping XS e5781e53
END DESCRIPTION:
XS GIS Cut Line= 4
      2024810.46     13467576.29      2024354.72     13467589.32
      2022996.21     13467958.24      2022219.65     13468244.57
#Sta/Elev= 30
  4017.4   526.6  4122.9  521.23    4283  517.88  4470.7  510.35  4477.1  511.39
  4511.7  509.03  4516.9  509.56  4586.1  506.89  4591.3  507.69    4934  492.96
  4986.8  492.34  4987.6  491.54  4994.7  491.54  4995.4  492.34  5018.3  495.16
  5127.8  497.45    5302  496.72  5403.7  497.82  5539.6   497.8  5579.6  497.42
  5682.3  497.97    5785  497.63  5886.9  498.09    5912  497.07  5942.4  498.95
  5972.9  498.42  6144.9  502.62  6226.2  503.39  6484.6  507.98  6708.7  512.58
#Mann= 11 ,-1 , 0
  4017.4      .1       0  4986.8     .07       0  4995.4      .1       0
  5018.3     .05       0  5403.7      .1       0  5539.6     .08       0
  5579.6      .1       0  5682.3     .08       0    5785     .05       0
  6226.2      .1       0  6484.6     .05       0
Bank Sta=4986.8,4995.4
XS Rating Curve= 0 ,0
Exp/Cntr=0.3,0.1

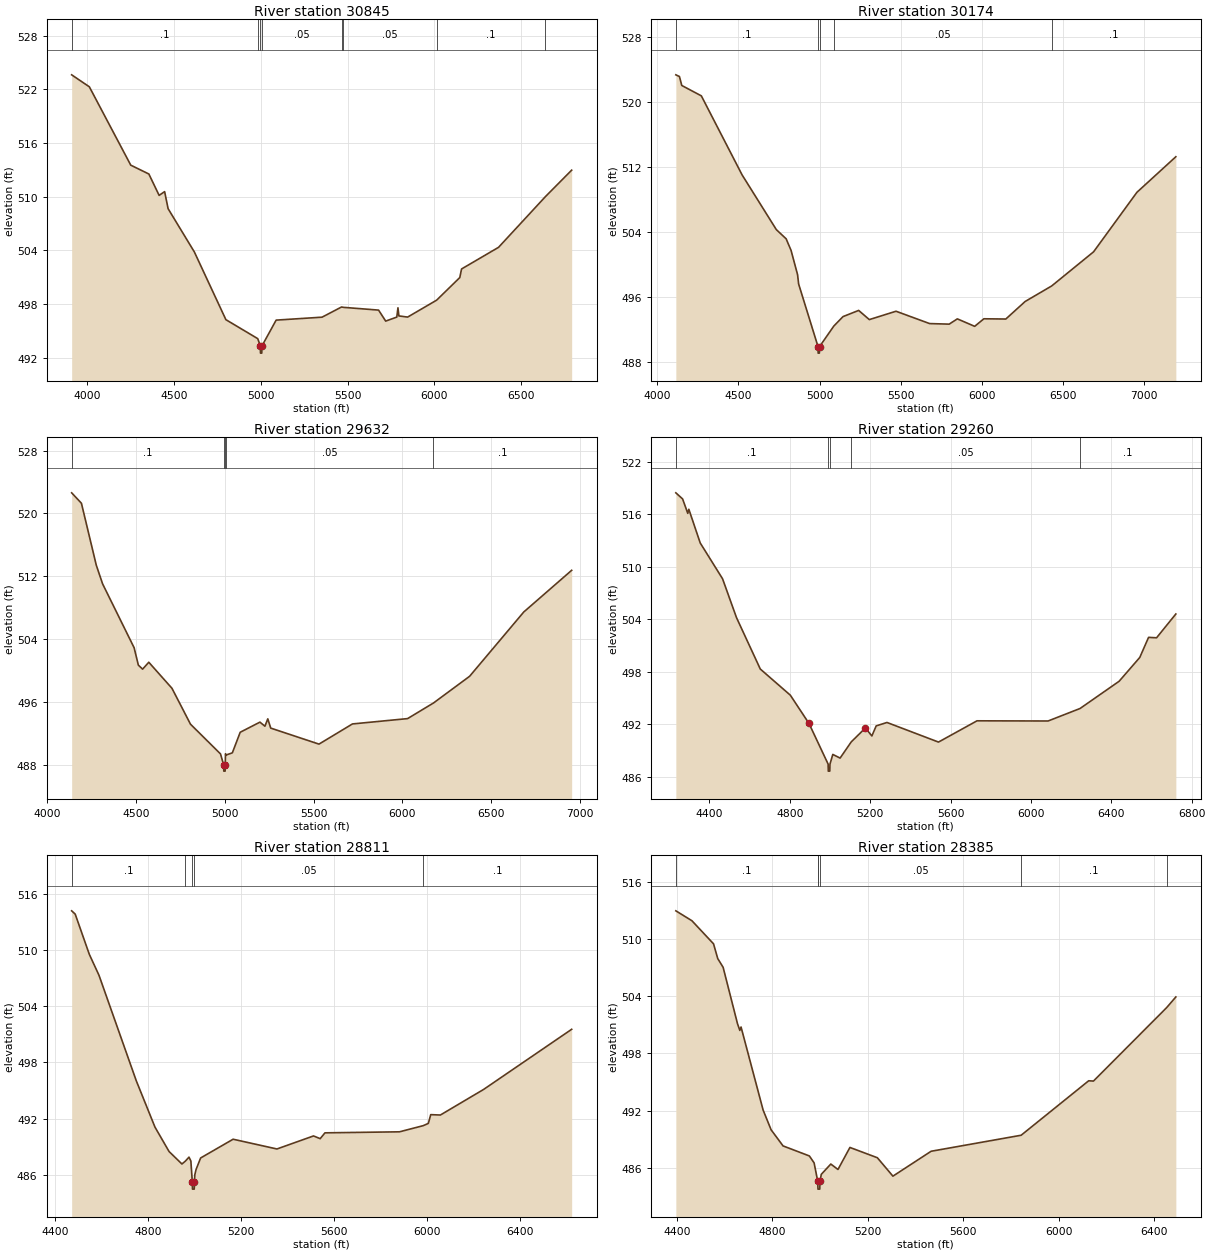
Type RM Length L Ch R = 1 ,30845   ,671,671,671
BEGIN DESCRIPTION:
UNT 042 in RCW 49.0
END DESCRIPTION:
XS GIS Cut Line= 3
      2024905.96     13467428.72      2023907.67     13467550.25
      2022149.92     13468192.59
#Sta/Elev= 30
  3912.5  523.61  4014.2  522.27  4252.5  513.51  4356.7  512.52  4415.8  510.13
  4447.4  510.55  4467.5  508.64  4618.6   503.8    4800  496.23  4983.2  494.11
  4998.3  493.29  4999.1  492.49  5006.5  492.49  5007.4  493.29  5089.1  496.18
  5353.3  496.51  5465.7  497.65  5476.4  497.61  5678.6   497.3  5719.5  496.07
  5783.4  496.52  5790.1  497.56  5795.4  496.65  5845.8  496.52  6012.5  498.41
  6145.9  500.94    6156   501.9  6368.9  504.32  6638.6  509.99  6789.6  512.95
#Mann= 8 ,-1 , 0
  3912.5      .1       0  4983.2     .05       0  4998.3     .03       0
  5007.4     .05       0  5465.7      .1       0  5476.4     .05       0
  6012.5      .1       0  6638.6     .05       0
Bank Sta=4998.3,5007.4
XS Rating Curve= 0 ,0
Exp/Cntr=0.3,0.1

Type RM Length L Ch R = 1 ,30174   ,542,542,542
BEGIN DESCRIPTION:
UNT 042 in RCW 48.0
END DESCRIPTION:
XS GIS Cut Line= 3
      2024871.25     13466877.51      2023521.39     13467025.08
      2021969.12     13467779.53
#Sta/Elev= 30
  4113.6  523.38  4135.8  523.17  4150.1  522.07  4270.8  520.79  4522.3  511.05
  4733.5  504.31  4793.9  503.18  4824.1  501.76  4864.3  498.77    4871  497.61
  4990.5   489.9  4991.3   489.1  4998.8   489.1  4999.7   489.9  5088.2  492.44
  5144.8   493.6  5241.1  494.36  5306.9  493.23  5471.5  494.26  5678.7  492.74
  5799.3  492.67  5849.9  493.32  5956.7   492.4  6013.4  493.33  6148.7   493.3
    6268  495.46    6432  497.38  6690.1  501.58  6957.4  508.91  7197.4  513.29
#Mann= 5 ,-1 , 0
  4113.6      .1       0  4990.5     .07       0  4999.7      .1       0
  5088.2     .05       0    6432      .1       0
Bank Sta=4990.5,4999.7
XS Rating Curve= 0 ,0
Exp/Cntr=0.3,0.1

Type RM Length L Ch R = 1 ,29632   ,372,372,372
BEGIN DESCRIPTION:
UNT 042 in RCW 47.0
END DESCRIPTION:
XS GIS Cut Line= 3
      2024445.85      13466326.3      2023825.21     13466582.37
      2021919.95     13467563.21
#Sta/Elev= 30
  4138.1  522.62  4193.1  521.29  4276.6  513.41  4312.1  511.03  4489.6  502.89
  4513.5  500.67  4537.5  500.16  4572.2  501.04  4702.7  497.72  4806.9  493.15
    4976  489.36  4993.5  487.97  4994.4  487.17  5001.9  487.17  5002.7  487.97
  5003.8  489.38  5008.6  489.23  5042.5   489.5  5086.8  492.12  5197.7  493.41
  5225.9  492.89    5242  493.83  5258.6  492.65  5530.2  490.61  5718.5  493.18
  6028.9  493.86  6174.7  495.85    6378  499.25  6682.8  507.44  6952.4  512.75
#Mann= 5 ,-1 , 0
  4138.1      .1       0  4993.5     .07       0  5002.7      .1       0
  5008.6     .05       0  6174.7      .1       0
Bank Sta=4993.5,5002.7
XS Rating Curve= 0 ,0
Exp/Cntr=0.3,0.1

Type RM Length L Ch R = 1 ,29260   ,449,449,449
BEGIN DESCRIPTION:
UNT 042 in RCW 46.0
END DESCRIPTION:
XS GIS Cut Line= 3
      2024424.21     13466139.65      2023573.47     13466439.14
      2022098.87     13467024.64
#Sta/Elev= 30
  4232.9  518.43  4266.6  517.73  4292.3  516.08  4297.6  516.55  4354.2   512.7
  4465.3  508.61  4534.7  504.17  4653.2  498.29  4802.7   495.3  4895.6  492.07
  4990.8  487.42  4991.6  486.62  4999.1  486.62    5000  487.42  5014.1  488.53
  5050.4  488.11  5105.8  489.96  5176.2  491.55  5208.5  490.64    5230  491.79
  5283.8  492.18  5540.1  489.94  5731.8  492.37  6085.5  492.35  6244.7  493.78
  6439.1  496.89  6541.8  499.61  6585.7  501.91  6625.4  501.86  6721.4  504.58
#Mann= 5 ,-1 , 0
  4232.9      .1       0  4990.8     .07       0    5000      .1       0
  5105.8     .05       0  6244.7      .1       0
Bank Sta=4895.6,5176.2
XS Rating Curve= 0 ,0
Exp/Cntr=0.3,0.1

Type RM Length L Ch R = 1 ,28811   ,426,426,426
BEGIN DESCRIPTION:
UNT 042 in RCW 45.0
END DESCRIPTION:
XS GIS Cut Line= 3
      2023925.02     13465924.99      2023208.89     13466191.75
      2021868.88     13466538.67
#Sta/Elev= 30
  4472.6  514.17  4487.8  513.82  4548.5  509.53    4590   507.3  4750.1  496.06
  4830.4  491.12  4891.1  488.51  4946.4  487.18  4961.3  487.49  4976.7  487.91
  4984.8   487.5  4990.9   485.3  4991.8   484.5  4999.3   484.5  5000.2   485.3
  5001.7  486.03  5007.1  486.59  5026.7  487.82  5166.3  489.82  5354.6  488.78
  5511.8  490.17  5540.4  489.88    5561   490.5  5881.3  490.61  5983.7  491.27
  6005.2  491.51  6015.5  492.44  6056.9   492.4  6242.8  495.13    6621  501.54
#Mann= 5 ,-1 , 0
  4472.6      .1       0  4961.3     .05       0  4990.9     .03       0
  5000.2     .05       0  5983.7      .1       0
Bank Sta=4990.9,5000.2
XS Rating Curve= 0 ,0
Exp/Cntr=0.3,0.1

Type RM Length L Ch R = 1 ,28385   ,432,432,432
BEGIN DESCRIPTION:
UNT 042 in RCW 44.0
END DESCRIPTION:
XS GIS Cut Line= 3
      2023911.99     13465848.86      2023504.03     13465805.46
      2021820.03     13465861.88
#Sta/Elev= 30
  4396.4  512.94  4463.8   511.9  4554.3  509.48    4572  507.93  4594.5  507.02
  4654.8   501.1  4664.5   500.4  4669.6  500.76  4762.1  492.05  4795.6  489.98
  4845.7  488.29  4955.8  487.24  4975.8  486.51  4990.2  484.68  4991.1  484.56
    4992  483.76  4999.5  483.76  5000.4  484.56  5005.8  485.31  5045.8  486.39
  5075.8  485.82  5125.9  488.13  5240.9  487.05    5306  485.12  5466.1  487.73
  5843.4  489.41  6126.4  495.12  6146.4  495.09    6453  502.79  6491.6  503.91
#Mann= 6 ,-1 , 0
  4396.4      .1       0  4990.2     .05       0  4991.1     .03       0
  5000.4     .05       0  5843.4      .1       0    6453     .05       0
Bank Sta=4991.1,5000.4
XS Rating Curve= 0 ,0
Exp/Cntr=0.3,0.1