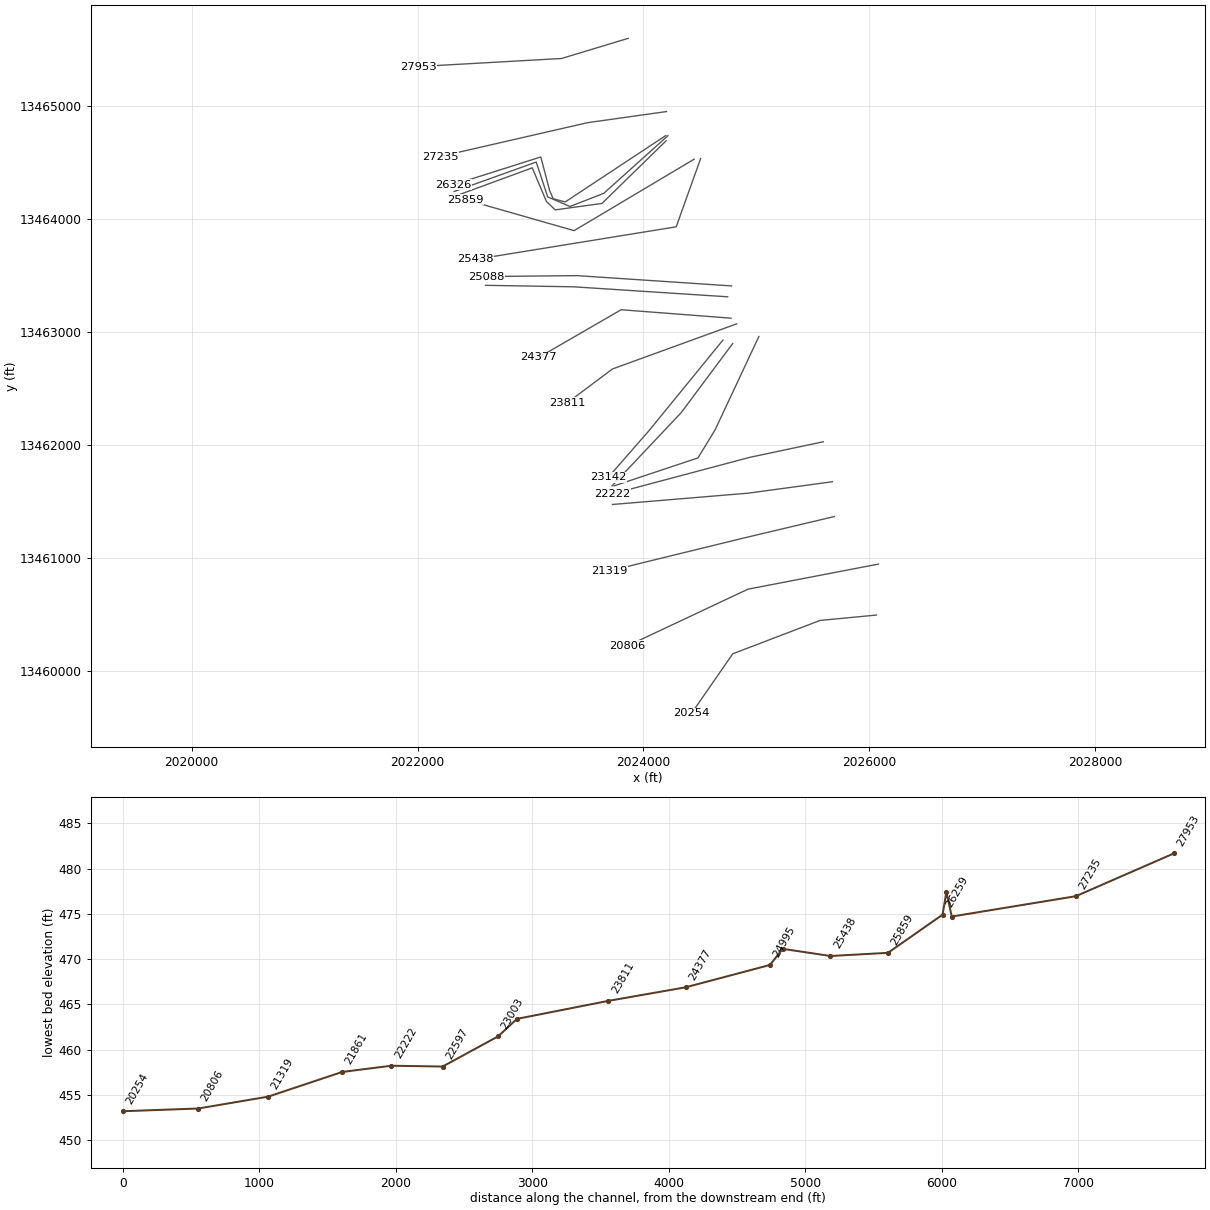
HEC-RAS study UNT 042 in RCW.prj: UNT 042 in RCW Base Level Engineering

--- UNT 042 in RCW.g01 (geometry) --- (continued)

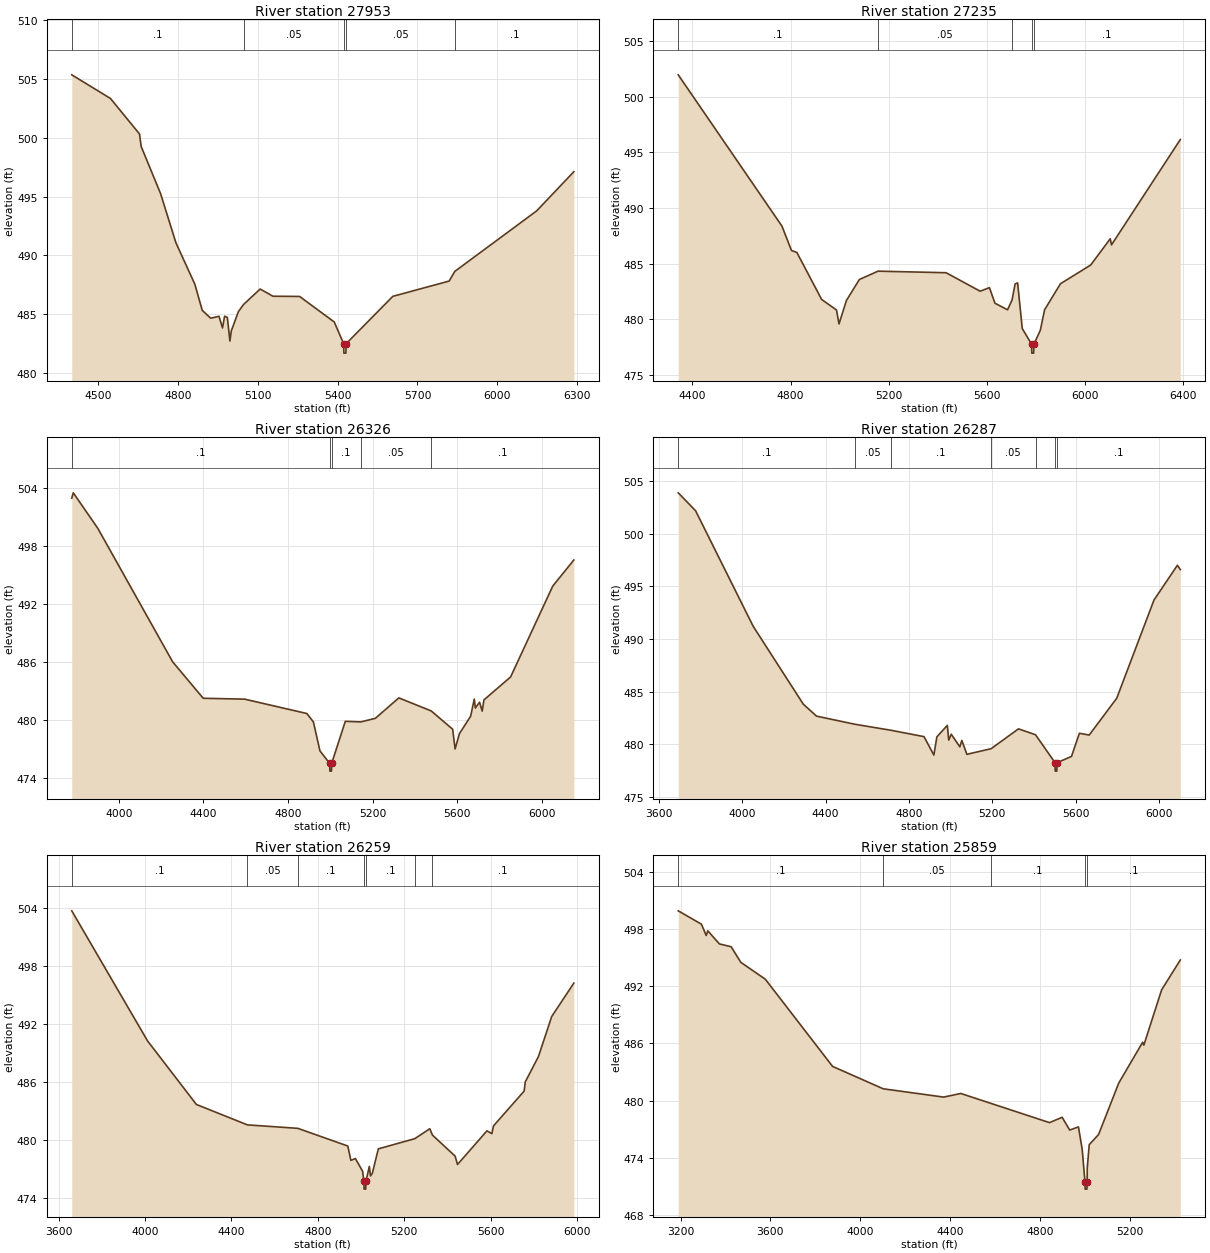
Type RM Length L Ch R = 1 ,27953   ,718,718,718
BEGIN DESCRIPTION:
UNT 042 in RCW 43.0
END DESCRIPTION:
XS GIS Cut Line= 3
      2023864.91     13465603.42        2023275.       13465425.
      2022005.52     13465353.42
#Sta/Elev= 30
  4400.2  505.36  4545.7  503.35  4654.9  500.33  4661.3  499.26  4734.4  495.24
  4791.9  491.07    4863  487.55  4890.8  485.33  4922.5  484.66  4953.8  484.82
  4967.1  483.83  4974.7  484.83  4985.2  484.73  4994.8  482.72    5000  483.58
  5026.5  485.21  5046.2  485.83  5108.5  487.14  5156.7  486.53  5256.9  486.51
  5387.1  484.34  5422.5  482.49  5423.4  481.69  5430.9  481.69  5431.8  482.49
  5607.4  486.52  5819.3  487.82  5840.4  488.64  6148.3  493.79    6288  497.12
#Mann= 5 ,-1 , 0
  4400.2      .1       0  5046.2     .05       0  5422.5     .07       0
  5431.8     .05       0  5840.4      .1       0
Bank Sta=5422.5,5431.8
XS Rating Curve= 0 ,0
Exp/Cntr=0.3,0.1

Type RM Length L Ch R = 1 ,27235   ,909,909,909
BEGIN DESCRIPTION:
UNT 042 in RCW 42.0
END DESCRIPTION:
XS GIS Cut Line= 3
      2024203.47     13464954.98      2023502.94     13464856.03
      2022199.13     13464556.75
#Sta/Elev= 30
  4342.4  501.95    4765  488.36  4803.7  486.18  4825.6     486  4926.6  481.78
  4987.2  480.83  4997.3  479.58  5027.6  481.69  5080.2  483.57  5156.4  484.32
  5433.5  484.18  5572.3  482.52  5610.1  482.84  5632.6  481.44  5683.9  480.85
  5702.2  481.73  5714.7  483.17  5724.9  483.27  5743.8  479.17  5781.8  477.76
  5782.7  476.96  5790.3  476.96  5791.2  477.76  5817.3  479.01  5834.7  480.85
  5899.4  483.19  6022.5  484.87  6102.2  487.23  6107.3  486.68  6387.6  496.14
#Mann= 5 ,-1 , 0
  4342.4      .1       0  5156.4     .05       0  5702.2      .1       0
  5781.8     .07       0  5791.2      .1       0
Bank Sta=5781.8,5791.2
XS Rating Curve= 0 ,0
Exp/Cntr=0.3,0.1

Type RM Length L Ch R = 1 ,26326   ,39,39,39
BEGIN DESCRIPTION:
Mapping XS be99be60
END DESCRIPTION:
XS GIS Cut Line= 6
      2024197.73     13464742.87      2023307.09     13464154.32
      2023200.32     13464182.97      2023169.07     13464255.89
      2023090.94     13464552.76      2022320.07     13464307.96
#Sta/Elev= 30
  3778.1     503  3785.3  503.55  3901.2  499.87  4254.9  486.04  4399.3  482.26
    4595  482.17  4889.2  480.68  4920.3  479.81  4951.2  476.81  4997.2  475.51
  4998.1  474.71  5005.7  474.71  5006.6  475.51  5071.1  479.87  5144.1  479.81
    5213  480.18  5324.1   482.3    5477  480.95  5578.6  479.05    5590  477.01
  5610.9  478.61  5663.5   480.4  5680.6  482.18  5685.9  481.25  5705.5  481.85
  5718.1  480.93  5726.4  482.09  5852.4  484.47  6051.7  493.89  6151.3  496.59
#Mann= 5 ,-1 , 0
  3778.1      .1       0  4997.2     .07       0  5006.6      .1       0
  5144.1     .05       0    5477      .1       0
Bank Sta=4997.2,5006.6
XS Rating Curve= 0 ,0
Exp/Cntr=0.3,0.1

Type RM Length L Ch R = 1 ,26287   ,28,28,28
BEGIN DESCRIPTION:
Mapping XS 735b4e9d
END DESCRIPTION:
XS GIS Cut Line= 6
      2024216.49     13464741.45      2023648.77     13464231.03
      2023348.76     13464113.96      2023152.14     13464199.12
      2023050.58     13464507.71      2022323.24     13464246.65
#Sta/Elev= 30
  3692.7   503.9  3775.9   502.2  4052.4  491.21  4293.1   483.8  4356.7  482.66
  4540.7  481.89    4713  481.32  4872.7  480.71    4920  478.96  4934.5  480.69
  4984.7  481.78  4991.4  480.38  5003.4  480.94  5044.8  479.74  5054.3  480.35
  5078.4  479.03  5194.7  479.56  5326.3  481.45  5408.1  480.89  5501.8  478.23
  5502.7  477.43  5510.3  477.43  5511.2  478.23  5580.7  478.83  5618.8  481.03
  5665.7  480.86  5797.9  484.36    5977  493.71  6089.3  497.01  6103.2   496.6
#Mann= 7 ,-1 , 0
  3692.7      .1       0  4540.7     .05       0    4713      .1       0
  5194.7     .05       0  5408.1      .1       0  5501.8     .07       0
  5511.2      .1       0
Bank Sta=5501.8,5511.2
XS Rating Curve= 0 ,0
Exp/Cntr=0.3,0.1

Type RM Length L Ch R = 1 ,26259   ,400,400,400
BEGIN DESCRIPTION:
Mapping XS a3d00e8f
END DESCRIPTION:
XS GIS Cut Line= 6
      2024200.35     13464696.02      2023632.61      13464141.3
      2023218.55     13464084.01      2023140.42     13464159.53
      2023015.42     13464456.41      2022378.72     13464222.52
#Sta/Elev= 30
  3660.4  503.72  4011.4  490.26  4237.7  483.68  4473.8  481.57  4707.6  481.21
    4939  479.38  4953.2   477.9  4974.2  478.08  5007.6  476.77  5013.6  475.72
  5014.5  474.92  5022.1  474.92    5023  475.72  5038.7  477.27    5044  476.29
  5052.5  476.55  5080.5  479.09  5249.2  480.14  5318.8  481.17  5331.1  480.51
    5436  478.34  5447.1  477.47  5583.5  480.95  5606.4  480.66    5614  481.47
  5755.6  485.06  5761.1  486.02  5822.1  488.64  5883.4  492.78    5986  496.24
#Mann= 7 ,-1 , 0
  3660.4      .1       0  4473.8     .05       0  4707.6      .1       0
  5013.6     .07       0    5023      .1       0  5249.2     .05       0
  5331.1      .1       0
Bank Sta=5013.6,5023
XS Rating Curve= 0 ,0
Exp/Cntr=0.3,0.1

Type RM Length L Ch R = 1 ,25859   ,421,421,421
BEGIN DESCRIPTION:
UNT 042 in RCW 41.0
END DESCRIPTION:
XS GIS Cut Line= 3
      2024448.27     13464533.12      2023385.75      13463900.3
      2022425.04     13464174.99
#Sta/Elev= 30
  3189.7  499.91    3293  498.51  3314.4  497.32  3321.5  497.81  3372.8  496.44
  3425.4  496.14  3468.2  494.51  3577.6  492.73  3877.1  483.58  4102.7  481.23
  4371.6  480.36    4448  480.74  4583.4  479.69  4843.2  477.68  4899.3  478.24
  4933.1   476.9  4972.1  477.23  4988.8  474.85  5000.9   471.5  5001.9   470.7
  5009.8   470.7  5010.8   471.5  5011.1  472.88    5020  475.37  5061.6  476.43
  5151.4  481.83    5258  486.12  5263.2  485.81  5342.4  491.62  5425.6  494.75
#Mann= 5 ,-1 , 0
  3189.7      .1       0  4102.7     .05       0  4583.4      .1       0
  5000.9     .07       0  5010.8      .1       0
Bank Sta=5000.9,5010.8
XS Rating Curve= 0 ,0
Exp/Cntr=0.3,0.1

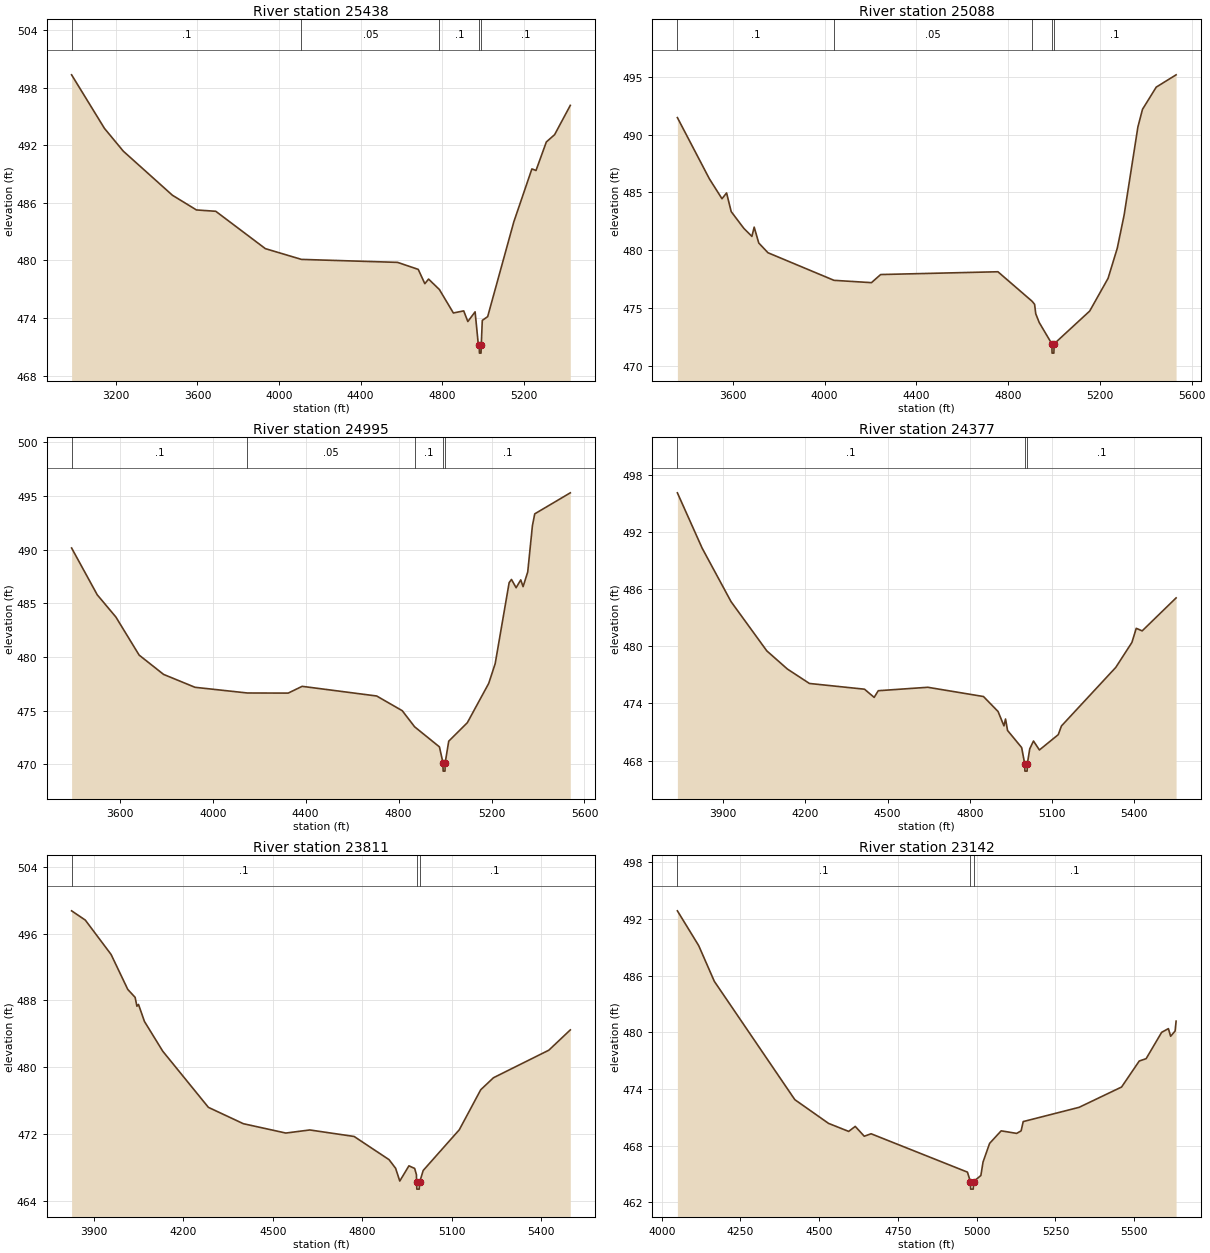
Type RM Length L Ch R = 1 ,25438   ,350,350,350
BEGIN DESCRIPTION:
Mapping XS 4067d0a0
END DESCRIPTION:
XS GIS Cut Line= 3
      2024505.55     13464538.33       2024289.4     13463934.15
      2022509.07     13463645.24
#Sta/Elev= 30
  2982.7  499.33  3143.9  493.75  3236.2  491.38  3477.1  486.79  3594.9  485.26
  3689.6  485.12  3932.8  481.23  4109.7  480.11  4581.1   479.8  4682.4  479.07
  4714.7  477.58  4733.1  478.06  4786.2  476.97  4854.7  474.53  4905.3  474.75
  4925.6  473.64  4961.2  474.65  4976.2  471.41  4981.4  471.15  4982.4  470.35
  4990.3  470.35  4991.3  471.15  4996.5  473.76  5022.8  474.15    5151  484.02
  5239.6  489.53  5259.9  489.37  5310.5  492.34  5351.1   493.1    5428  496.15
#Mann= 5 ,-1 , 0
  2982.7      .1       0  4109.7     .05       0  4786.2      .1       0
  4981.4     .07       0  4991.3      .1       0
Bank Sta=4981.4,4991.3
XS Rating Curve= 0 ,0
Exp/Cntr=0.3,0.1

Type RM Length L Ch R = 1 ,25088   ,93,93,93
BEGIN DESCRIPTION:
UNT 042 in RCW 40.0
END DESCRIPTION:
XS GIS Cut Line= 3
      2024778.95     13463410.71      2023411.79     13463501.86
      2022608.52     13463494.06
#Sta/Elev= 30
  3358.8  491.46  3498.2  486.18  3553.2  484.46  3573.2  484.96  3593.3  483.35
  3648.6   481.9  3683.5  481.21  3693.5  482.01  3713.5  480.64  3753.6   479.8
  4041.4  477.42  4204.6  477.22  4244.7  477.92  4755.8  478.16    4905  475.61
  4915.6  475.35  4920.6  474.54  4935.8  473.78  4990.8  471.94  4991.8  471.14
  4999.7  471.14  5000.7  471.94  5155.8  474.77  5235.8  477.59  5275.8  480.18
  5305.8  483.05  5365.8  490.65  5385.8  492.17  5445.8  494.09  5532.3  495.15
#Mann= 5 ,-1 , 0
  3358.8      .1       0  4041.4     .05       0    4905      .1       0
  4990.8     .07       0  5000.7      .1       0
Bank Sta=4990.8,5000.7
XS Rating Curve= 0 ,0
Exp/Cntr=0.3,0.1

Type RM Length L Ch R = 1 ,24995   ,618,618,618
BEGIN DESCRIPTION:
UNT 042 in RCW 39.0
END DESCRIPTION:
XS GIS Cut Line= 3
       2024745.1     13463314.36      2023380.54      13463402.9
      2022601.87     13463415.92
#Sta/Elev= 30
  3392.8  490.15  3503.1  485.79  3583.3  483.72  3683.5  480.17  3788.8  478.37
    3924  477.17  4149.2  476.64  4324.9  476.63    4385  477.26  4705.7  476.36
  4815.8  474.99    4869  473.49  4975.8  471.62  4990.8  470.16  4991.8  469.36
  4999.7  469.36  5000.7  470.16  5015.8  472.15  5095.8  473.87  5187.8  477.53
  5215.8  479.38  5275.8  486.92  5285.8  487.22  5305.8  486.45  5325.8  487.18
  5335.8  486.55  5355.8  487.92  5375.9  492.22  5385.9  493.33    5539  495.29
#Mann= 5 ,-1 , 0
  3392.8      .1       0  4149.2     .05       0    4869      .1       0
  4990.8     .07       0  5000.7      .1       0
Bank Sta=4990.8,5000.7
XS Rating Curve= 0 ,0
Exp/Cntr=0.3,0.1

Type RM Length L Ch R = 1 ,24377   ,566,566,566
BEGIN DESCRIPTION:
UNT 042 in RCW 38.0
END DESCRIPTION:
XS GIS Cut Line= 3
        2024775.       13463125.      2023802.42     13463199.78
      2023073.22     13462777.88
#Sta/Elev= 30
  3734.1   496.1  3824.4  490.29  3929.7  484.68  4060.1  479.51  4135.3   477.6
  4215.5  476.09  4416.1  475.49  4451.4  474.63  4466.3  475.33  4646.8  475.69
  4849.9  474.72    4903  473.15  4924.5  471.64  4930.3  472.36  4937.6  471.16
  4989.1  469.36  4999.9  467.69  5000.9  466.89  5008.9  466.89  5009.9  467.69
  5018.5  469.23  5032.2  470.05  5053.8  469.11  5122.5  470.72  5134.1  471.63
  5332.2  477.78    5391   480.4  5406.8  481.88  5428.3  481.61    5552  485.07
#Mann= 3 ,-1 , 0
  3734.1      .1       0  4999.9     .07       0  5009.9      .1       0
Bank Sta=4999.9,5009.9
XS Rating Curve= 0 ,0
Exp/Cntr=0.3,0.1

Type RM Length L Ch R = 1 ,23811   ,669,669,669
BEGIN DESCRIPTION:
UNT 042 in RCW 37.0
END DESCRIPTION:
XS GIS Cut Line= 3
        2024825.       13463075.        2023725.       13462675.
      2023324.98     13462374.98
#Sta/Elev= 30
  3826.2  498.74  3872.1  497.63  3958.5  493.51  4014.4  489.32    4039  488.37
    4045  487.31  4050.3  487.52  4070.3  485.48  4131.5  481.92  4284.4  475.19
  4401.5  473.23  4543.8  472.11  4624.2  472.48  4772.6   471.7  4889.6  468.92
  4911.5  467.89  4925.5  466.36  4956.1  468.18  4975.4  467.87  4981.4   467.1
  4981.7  466.19  4982.7  465.39  4990.7  465.39  4991.7  466.19    5004  467.63
  5124.8   472.5  5196.7   477.3  5239.4  478.74  5424.8  482.04  5496.7  484.47
#Mann= 3 ,-1 , 0
  3826.2      .1       0  4981.7     .07       0  4991.7      .1       0
Bank Sta=4981.7,4991.7
XS Rating Curve= 0 ,0
Exp/Cntr=0.3,0.1

Type RM Length L Ch R = 1 ,23142   ,139,139,139
BEGIN DESCRIPTION:
UNT 042 in RCW 36.0
END DESCRIPTION:
XS GIS Cut Line= 3
      2024703.45     13462931.53      2024047.21     13462126.86
      2023688.92     13461716.64
#Sta/Elev= 30
  4049.8  492.86  4117.4  489.18    4167   485.4  4422.6  472.87  4529.6  470.36
  4593.5  469.51  4614.3  470.04    4643     469  4664.7  469.26  4970.5   465.2
  4979.8   464.2  4980.7   463.4  4988.9   463.4  4989.9   464.2  5013.1  464.84
    5020  466.27  5040.8  468.24  5077.5  469.57  5126.7   469.3  5140.9  469.57
  5147.5  470.55    5325  472.06  5459.8  474.21  5515.8  476.96  5537.7  477.21
    5587     480  5608.4  480.39  5615.5  479.58  5629.7  480.14  5632.8  481.18
#Mann= 3 ,-1 , 0
  4049.8      .1       0  4979.8     .07       0  4989.9      .1       0
Bank Sta=4979.8,4989.9
XS Rating Curve= 0 ,0
Exp/Cntr=0.3,0.1

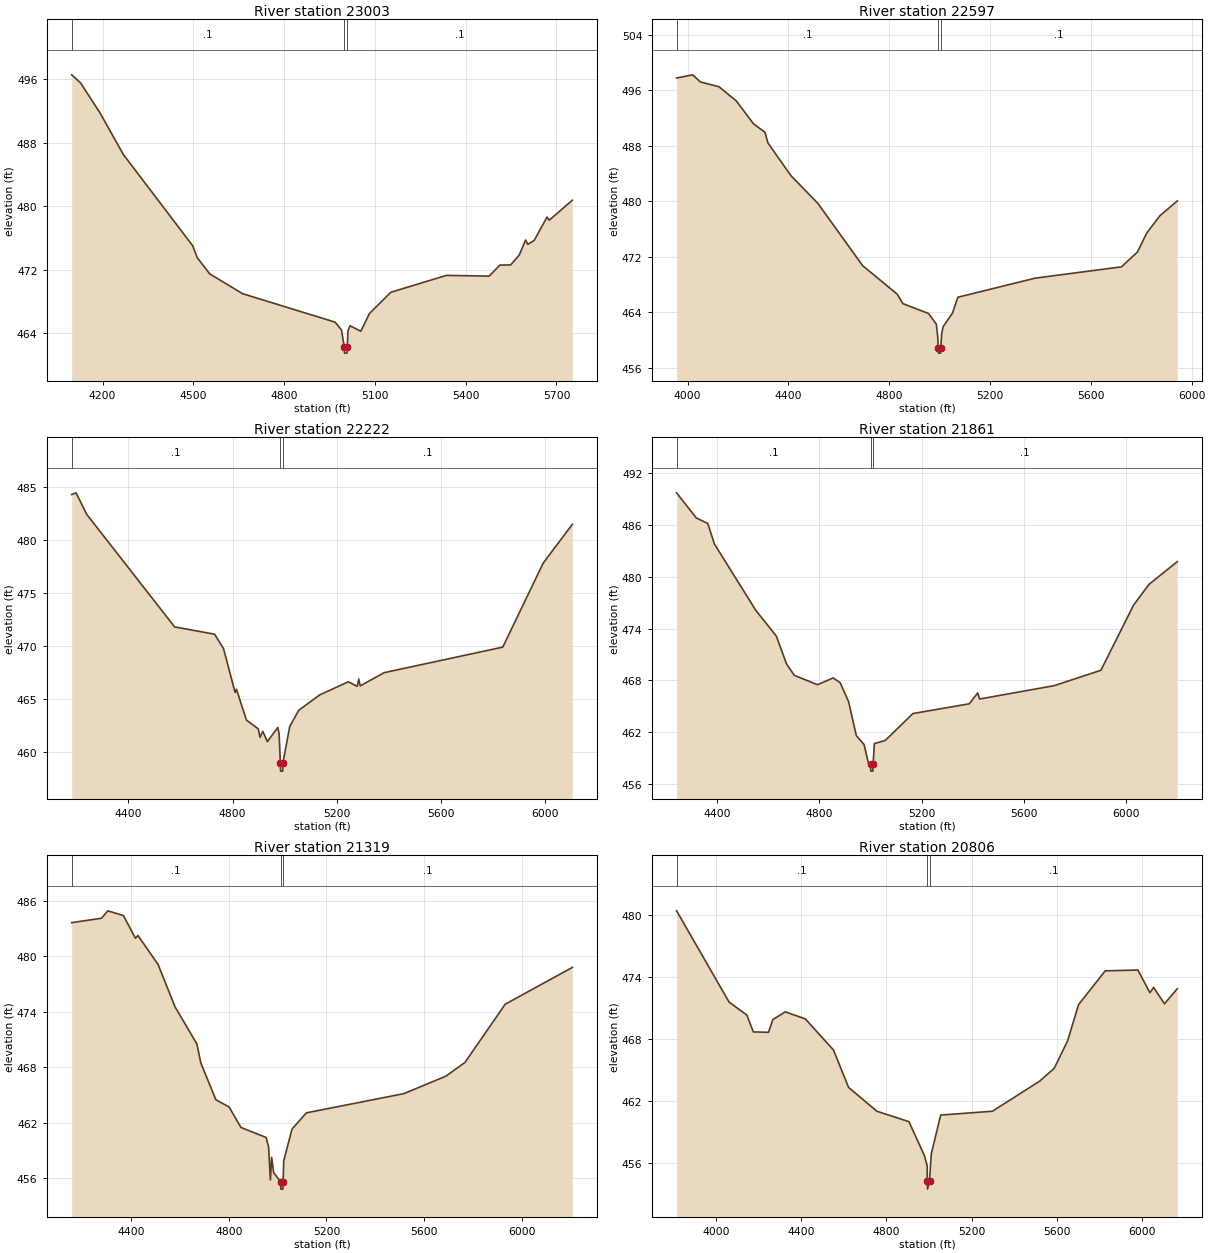
Type RM Length L Ch R = 1 ,23003   ,406,406,406
BEGIN DESCRIPTION:
UNT 042 in RCW 35.0
END DESCRIPTION:
XS GIS Cut Line= 3
      2024789.38     13462900.27      2024333.67     13462288.32
      2023721.77     13461639.96
#Sta/Elev= 30
  4097.9  496.58  4126.8  495.58  4191.4  491.78  4268.5  486.53    4498     475
  4512.6  473.51  4554.2  471.46  4662.7  468.96  4968.4  465.37  4989.4  464.39
  4998.5  462.26  4999.5  461.46  5007.7  461.46  5008.6  462.26  5010.9  464.28
  5017.8  464.91  5053.4  464.22  5081.7  466.45  5152.5  469.14  5336.1  471.27
  5477.7  471.18  5512.9  472.57  5548.5  472.59  5576.9  473.83  5597.9  475.73
  5605.2  475.19  5626.2  475.68  5668.7  478.63    5676  478.23  5752.4  480.76
#Mann= 3 ,-1 , 0
  4097.9      .1       0  4998.5     .07       0  5008.6      .1       0
Bank Sta=4998.5,5008.6
XS Rating Curve= 0 ,0
Exp/Cntr=0.3,0.1

Type RM Length L Ch R = 1 ,22597   ,375,375,375
BEGIN DESCRIPTION:
Mapping XS 3409e8af
END DESCRIPTION:
XS GIS Cut Line= 4
      2025021.19     13462962.83      2024633.15     13462134.67
      2024482.11     13461887.28      2023740.16     13461639.96
#Sta/Elev= 30
  3956.4  497.76  4020.3  498.22  4050.7   497.2  4124.7   496.5  4193.2  494.46
  4261.6  491.16  4307.3  489.93  4318.4  488.43  4409.7  483.71  4517.2  479.69
  4694.6  470.73  4831.6  466.63  4854.4  465.26  4956.1  463.84    4987   462.3
  4992.9  460.37  4994.4  458.93  4995.4  458.13  5003.6  458.13  5004.5  458.93
  5008.3  460.94  5014.2  461.96    5051  463.89  5072.3  466.18  5379.1  468.93
  5721.6  470.56  5784.8  472.69  5821.9  475.43  5874.4  477.93  5942.9  480.05
#Mann= 3 ,-1 , 0
  3956.4      .1       0  4994.4     .07       0  5004.5      .1       0
Bank Sta=4994.4,5004.5
XS Rating Curve= 0 ,0
Exp/Cntr=0.3,0.1

Type RM Length L Ch R = 1 ,22222   ,361,361,361
BEGIN DESCRIPTION:
UNT 042 in RCW 34.0
END DESCRIPTION:
XS GIS Cut Line= 3
      2025591.44      13462030.5      2024940.44     13461892.48
      2023726.93     13461569.58
#Sta/Elev= 30
  4182.8  484.32  4199.6  484.48  4240.5  482.45  4577.8  471.83  4731.2  471.14
  4765.4  469.78  4809.9  465.64    4815  465.95  4853.3  463.04  4898.6  462.21
  4905.6  461.41    4916  461.98  4933.6     461  4973.7  462.34  4978.9  461.71
  4983.4  459.02  4984.3  458.22  4992.5  458.22  4993.5  459.02  5019.5  462.43
    5054  463.96  5134.3  465.41  5244.4  466.65  5278.2  466.22  5284.5  466.91
  5289.7  466.26  5381.6  467.51    5837  469.92  5992.2  477.85    6104  481.51
#Mann= 3 ,-1 , 0
  4182.8      .1       0  4983.4     .07       0  4993.5      .1       0
Bank Sta=4983.4,4993.5
XS Rating Curve= 0 ,0
Exp/Cntr=0.3,0.1

Type RM Length L Ch R = 1 ,21861   ,542,542,542
BEGIN DESCRIPTION:
UNT 042 in RCW 33.0
END DESCRIPTION:
XS GIS Cut Line= 3
      2025671.33     13461676.34        2024925.       13461575.
      2023725.04       13461475.
#Sta/Elev= 30
    4242  489.68    4319  486.78  4363.9  486.14  4389.7  483.78  4551.1  476.13
  4631.9  473.13  4672.2  469.89  4702.5  468.59  4793.3  467.51  4853.9   468.3
  4881.4  467.75  4914.4  465.56  4944.7  461.63    4975   460.6  4992.7  458.36
  5000.1  458.33  5001.1  457.53  5009.4  457.53  5010.3  458.33  5015.2  460.71
  5057.9  461.08  5165.8  464.18  5386.5  465.31  5419.1  466.56  5426.7  465.86
  5717.7   467.4  5900.8  469.18  6028.8  476.72    6089  479.11  6199.3  481.73
#Mann= 3 ,-1 , 0
    4242      .1       0  5000.1     .07       0  5010.3      .1       0
Bank Sta=5000.1,5010.3
XS Rating Curve= 0 ,0
Exp/Cntr=0.3,0.1

Type RM Length L Ch R = 1 ,21319   ,513,513,513
BEGIN DESCRIPTION:
UNT 042 in RCW 32.0
END DESCRIPTION:
XS GIS Cut Line= 3
      2025688.72     13461368.18        2024875.       13461175.
       2023698.3     13460886.84
#Sta/Elev= 30
  4157.8  483.62  4279.8   484.1  4305.5   484.9  4369.4  484.39  4418.6  481.93
  4428.8  482.23  4511.1   479.1  4580.4  474.52  4669.9   470.5  4685.8  468.46
  4747.5  464.47  4801.7  463.68  4850.2  461.47    4953  460.39  4963.3  459.33
  4970.5   455.8  4975.6  458.24  4983.9  456.58  5012.4   455.6  5013.4   454.8
  5021.7   454.8  5022.6   455.6    5025  457.86  5059.1   461.3  5117.7  463.05
  5516.9  465.13  5688.5  467.02  5766.3   468.5    5931   474.8  6205.6  478.78
#Mann= 3 ,-1 , 0
  4157.8      .1       0  5012.4     .07       0  5022.6      .1       0
Bank Sta=5012.4,5022.6
XS Rating Curve= 0 ,0
Exp/Cntr=0.3,0.1

Type RM Length L Ch R = 1 ,20806   ,552,552,552
BEGIN DESCRIPTION:
UNT 042 in RCW 31.0
END DESCRIPTION:
XS GIS Cut Line= 3
      2026079.35     13460947.18        2024925.       13460725.
      2023858.57     13460223.03
#Sta/Elev= 30
  3813.3  480.43    4060   471.6  4143.6  470.34  4174.2  468.71  4245.4  468.67
  4265.8   469.9  4324.6  470.65  4418.6  469.97  4550.9  466.96  4622.2  463.33
  4755.2  461.03  4905.9  460.02  4978.7  456.73  4991.6  455.74  4992.4  454.29
  4993.3  453.49  5002.6  454.29  5010.9  456.91  5055.2  460.66  5298.3  461.03
    5521  463.95  5589.4   465.2    5652  467.85  5703.4  471.35  5828.8  474.62
  5982.4   474.7    6039   472.5  6056.3  473.02  6107.4  471.43  6167.5  472.89
#Mann= 3 ,-1 , 0
  3813.3      .1       0  4992.4     .07       0  5002.6      .1       0
Bank Sta=4992.4,5002.6
XS Rating Curve= 0 ,0
Exp/Cntr=0.3,0.1

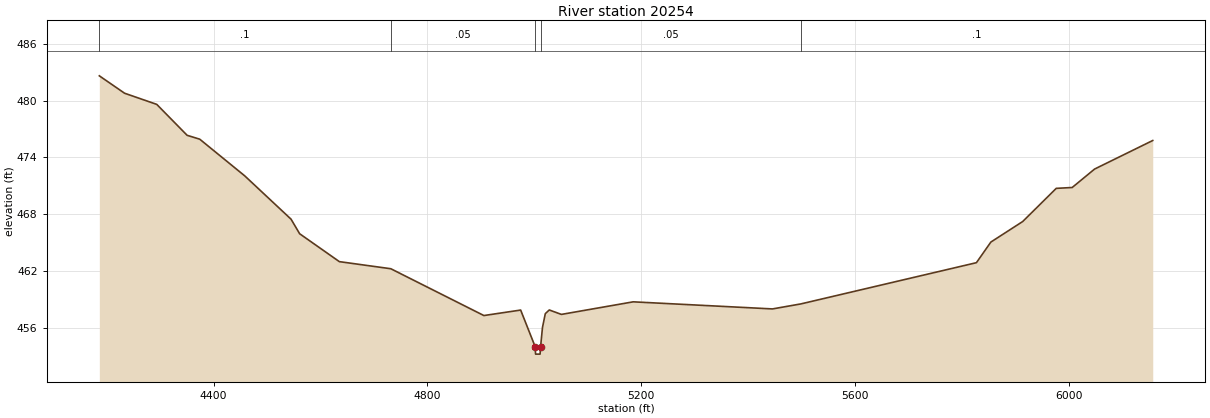
Type RM Length L Ch R = 1 ,20254   ,348,348,348
BEGIN DESCRIPTION:
UNT 042 in RCW 30.0
END DESCRIPTION:
XS GIS Cut Line= 4
      2026061.94     13460495.78      2025562.84     13460448.04
      2024790.27      13460152.9      2024424.98     13459624.96
#Sta/Elev= 30
  4186.4  482.62  4233.6  480.78  4293.8   479.6  4350.6  476.33  4374.2  475.92
  4458.4  472.04    4545  467.46  4561.1  465.92  4635.4  462.97  4731.6  462.22
  4905.7  457.27  4974.5  457.85  5001.5  453.99  5002.4  453.19  5010.8  453.19
  5011.8  453.99  5015.3  456.01  5020.6  457.47    5028  457.86  5050.7  457.39
    5185  458.72  5445.5  457.97  5498.6   458.5    5827  462.86    5854  465.04
  5913.5  467.21  5976.3  470.72  6006.1  470.81    6048  472.76  6156.8  475.78
#Mann= 5 ,-1 , 0
  4186.4      .1       0  4731.6     .05       0  5001.5    .035       0
  5011.8     .05       0  5498.6      .1       0
Bank Sta=5001.5,5011.8
XS Rating Curve= 0 ,0
Exp/Cntr=0.3,0.1