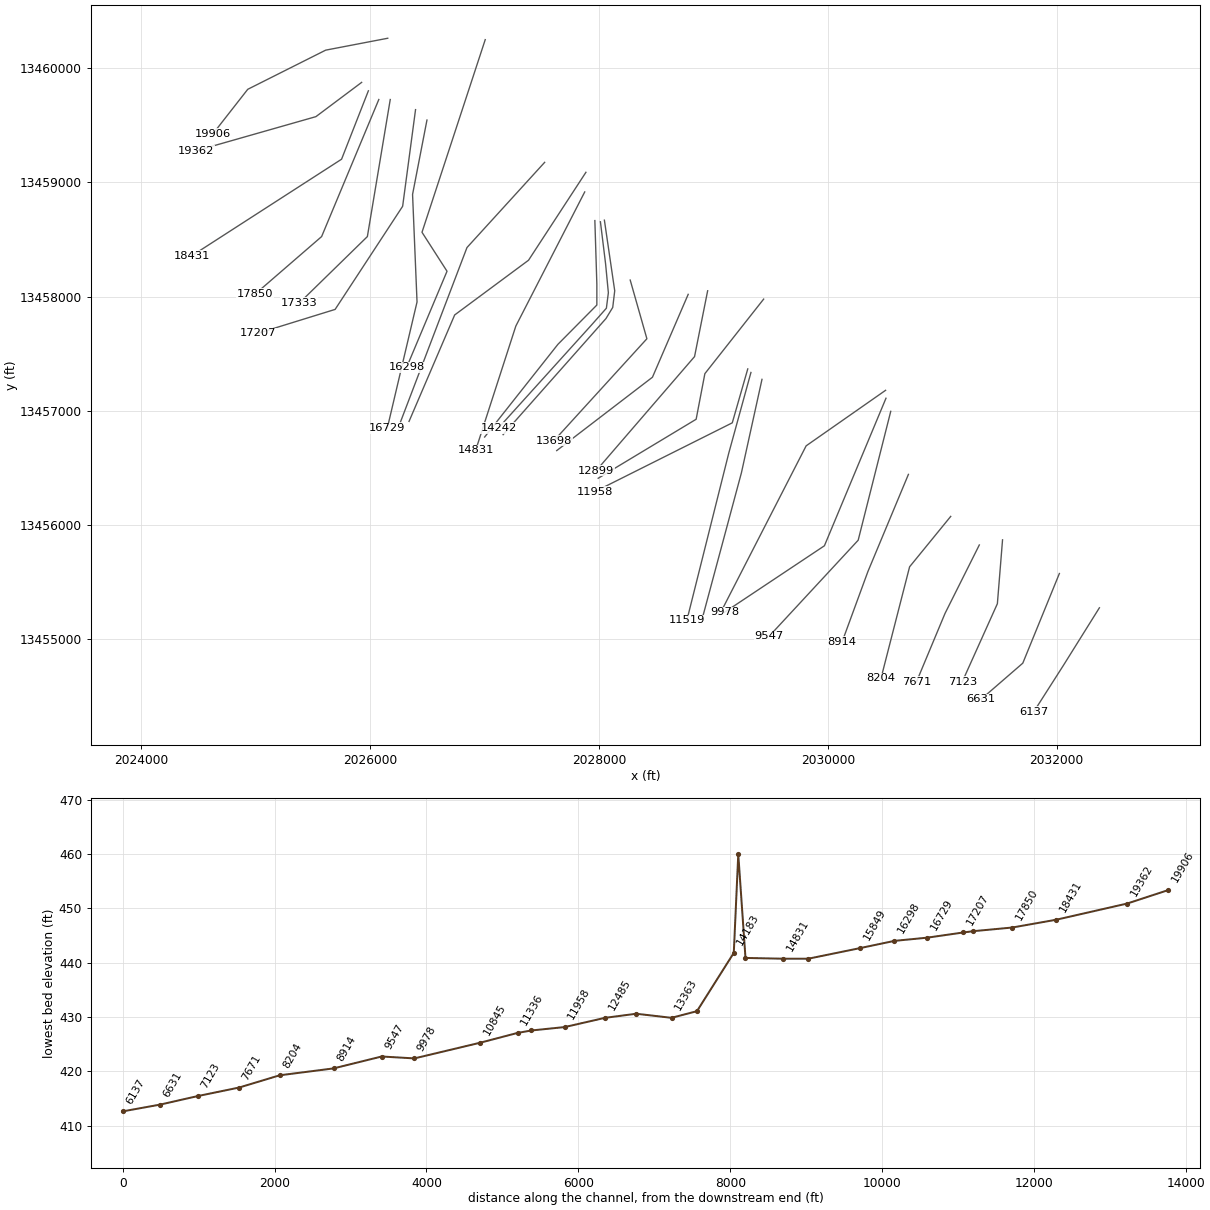
HEC-RAS study UNT 042 in RCW.prj: UNT 042 in RCW Base Level Engineering

--- UNT 042 in RCW.g01 (geometry) --- (continued)

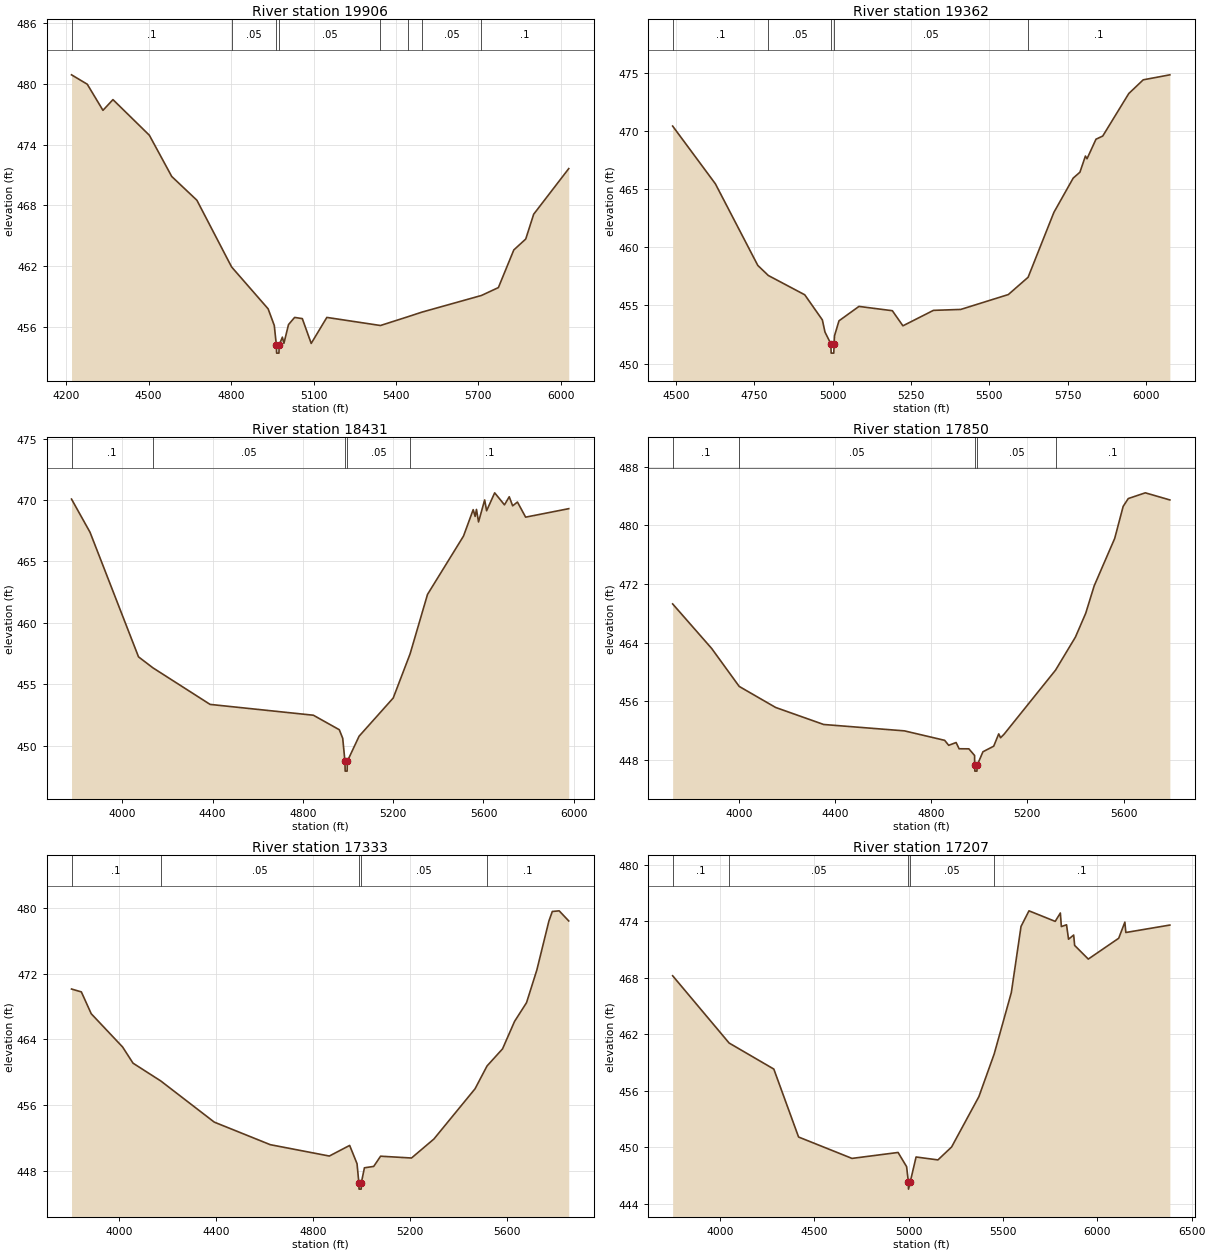
Type RM Length L Ch R = 1 ,19906   ,544,544,544
BEGIN DESCRIPTION:
UNT 042 in RCW 29.0
END DESCRIPTION:
XS GIS Cut Line= 4
      2026153.14     13460261.41      2025610.58     13460157.24
      2024929.16     13459814.36      2024624.98     13459424.98
#Sta/Elev= 30
  4219.3   480.9  4276.6  479.97  4333.7  477.39  4370.1  478.45  4502.5  474.93
    4584  470.85  4675.6   468.5  4801.8  461.91  4934.7  457.77  4957.1  456.13
  4964.7  454.19  4965.7  453.39  4974.1  453.39    4975  454.19  4986.6  454.97
  4992.2  454.36  5008.9  456.21  5031.2  456.92  5059.2   456.8  5091.5  454.35
  5148.4  456.92  5343.5  456.12  5442.5  456.98  5494.1  457.44  5711.1  459.09
  5772.7  459.87  5828.8  463.59  5872.2  464.67  5901.1  467.12  6028.7  471.63
#Mann= 8 ,-1 , 0
  4219.3      .1       0  4801.8     .05       0  4964.7    .035       0
    4975     .05       0  5343.5     .07       0  5442.5      .1       0
  5494.1     .05       0  5711.1      .1       0
Bank Sta=4964.7,4975
XS Rating Curve= 0 ,0
Exp/Cntr=0.3,0.1

Type RM Length L Ch R = 1 ,19362   ,931,931,931
BEGIN DESCRIPTION:
UNT 042 in RCW 28.0
END DESCRIPTION:
XS GIS Cut Line= 3
        2025925.       13459875.        2025525.       13459575.
      2024478.86     13459276.48
#Sta/Elev= 30
    4489  470.44  4625.5  465.47  4760.9  458.45  4794.6  457.58  4910.9  455.92
  4967.1  453.76  4975.5  452.71  4994.3   451.7  4995.2   450.9  5003.6   450.9
  5004.6   451.7  5005.9  452.39  5020.2  453.68    5084  454.92  5190.6  454.55
  5224.4  453.25  5321.8  454.58  5409.1  454.66    5561  455.94  5624.2  457.43
  5706.5  463.01  5768.1  465.96  5789.7  466.47  5807.2  467.86  5812.4  467.63
    5841  469.31  5862.5  469.58  5945.7  473.24  5991.8  474.42  6076.9  474.85
#Mann= 5 ,-1 , 0
    4489      .1       0  4794.6     .05       0  4994.3    .035       0
  5004.6     .05       0  5624.2      .1       0
Bank Sta=4994.3,5004.6
XS Rating Curve= 0 ,0
Exp/Cntr=0.3,0.1

Type RM Length L Ch R = 1 ,18431   ,581,581,581
BEGIN DESCRIPTION:
Mapping XS 24299393
END DESCRIPTION:
XS GIS Cut Line= 3
      2025983.86     13459801.38      2025749.47     13459202.38
      2024439.37     13458356.45
#Sta/Elev= 30
  3775.1  470.07  3857.1  467.37  4071.9  457.23  4135.4  456.34    4389  453.36
  4846.5  452.48  4961.3   451.3  4976.5   450.6  4986.4  448.73  4987.3  447.93
    4996  447.93  4996.9  448.73    5049  450.77  5200.2  453.88  5275.1  457.48
  5352.1  462.31  5511.6  467.06  5554.5  469.21  5563.1  468.66    5569  469.23
  5578.2  468.21  5605.3     470    5614  469.12  5649.7  470.58  5693.1   469.6
  5714.2  470.26  5729.3  469.52  5750.5  469.83  5786.8   468.6  5977.8  469.29
#Mann= 5 ,-1 , 0
  3775.1      .1       0  4135.4     .05       0  4986.4    .035       0
  4996.9     .05       0  5275.1      .1       0
Bank Sta=4986.4,4996.9
XS Rating Curve= 0 ,0
Exp/Cntr=0.3,0.1

Type RM Length L Ch R = 1 ,17850   ,517,517,517
BEGIN DESCRIPTION:
UNT 042 in RCW 27.0
END DESCRIPTION:
XS GIS Cut Line= 3
      2026075.01     13459725.01        2025575.       13458525.
      2024994.27     13458021.84
#Sta/Elev= 30
  3724.4  469.29  3886.9  463.21  4001.3  458.04  4152.9  455.17  4352.7  452.85
  4688.6  451.98    4856  450.69  4872.7  450.01  4903.6  450.39  4916.1  449.54
  4956.7  449.53  4980.5  448.62  4980.7  447.29  4981.6  446.49  4990.3  446.49
  4991.2  447.29  5015.2  449.13    5060  449.89  5080.9  451.57  5088.5  451.04
  5102.8  451.51  5317.2  460.26    5400  464.77  5442.8  468.02  5477.9  471.75
  5563.4  478.23  5598.5  482.59  5619.8  483.66  5690.7  484.44  5792.8  483.47
#Mann= 5 ,-1 , 0
  3724.4      .1       0  4001.3     .05       0  4980.7    .035       0
  4991.2     .05       0  5317.2      .1       0
Bank Sta=4980.7,4991.2
XS Rating Curve= 0 ,0
Exp/Cntr=0.3,0.1

Type RM Length L Ch R = 1 ,17333   ,126,126,126
BEGIN DESCRIPTION:
UNT 042 in RCW 26.0
END DESCRIPTION:
XS GIS Cut Line= 3
        2026175.     13459724.98        2025975.       13458525.
      2025380.52     13457943.68
#Sta/Elev= 30
  3804.7  470.12  3845.2  469.77  3885.8  467.12    4015  463.08  4058.1  461.11
  4172.4  458.95  4392.7  453.95  4623.3  451.21  4866.6  449.83  4950.3  451.12
  4980.7   448.9  4988.1  446.61    4989  445.81  4997.7  445.81  4998.6  446.61
  5011.1   448.4  5049.4  448.57  5077.7  449.81    5205  449.59  5297.1  451.89
  5466.8     458  5516.1  460.77    5580  462.85  5629.4  466.18  5678.8  468.46
  5721.2  472.42  5770.8  478.36    5785  479.54  5813.3  479.62  5852.7  478.39
#Mann= 5 ,-1 , 0
  3804.7      .1       0  4172.4     .05       0  4988.1    .035       0
  4998.6     .05       0  5516.1      .1       0
Bank Sta=4988.1,4998.6
XS Rating Curve= 0 ,0
Exp/Cntr=0.3,0.1

Type RM Length L Ch R = 1 ,17207   ,478,478,478
BEGIN DESCRIPTION:
Mapping XS 2f8b3919
END DESCRIPTION:
XS GIS Cut Line= 4
      2026396.17     13459636.41      2026283.32     13458790.05
      2025693.04     13457887.28      2025022.05     13457679.48
#Sta/Elev= 30
  3749.6  468.22    4049  461.08  4285.7  458.32  4416.9  451.11    4700  448.84
  4944.2  449.47  4989.5  447.96  4998.5  446.38  4999.4  445.58    5009  446.38
  5039.6  448.99  5155.4  448.68  5227.8  450.05  5372.6   455.4  5453.5  459.92
  5544.4  466.44  5595.7  473.45  5637.9  475.11  5776.9  473.99  5804.2  474.88
  5809.5  473.44  5836.9  473.63  5847.5   472.1  5874.7  472.54  5879.9  471.44
  5952.2  469.99  6113.4   472.2    6146  473.91  6151.2  472.81  6384.5   473.6
#Mann= 5 ,-1 , 0
  3749.6      .1       0    4049     .05       0  4998.5    .035       0
    5009     .05       0  5453.5      .1       0
Bank Sta=4998.5,5009
XS Rating Curve= 0 ,0
Exp/Cntr=0.3,0.1

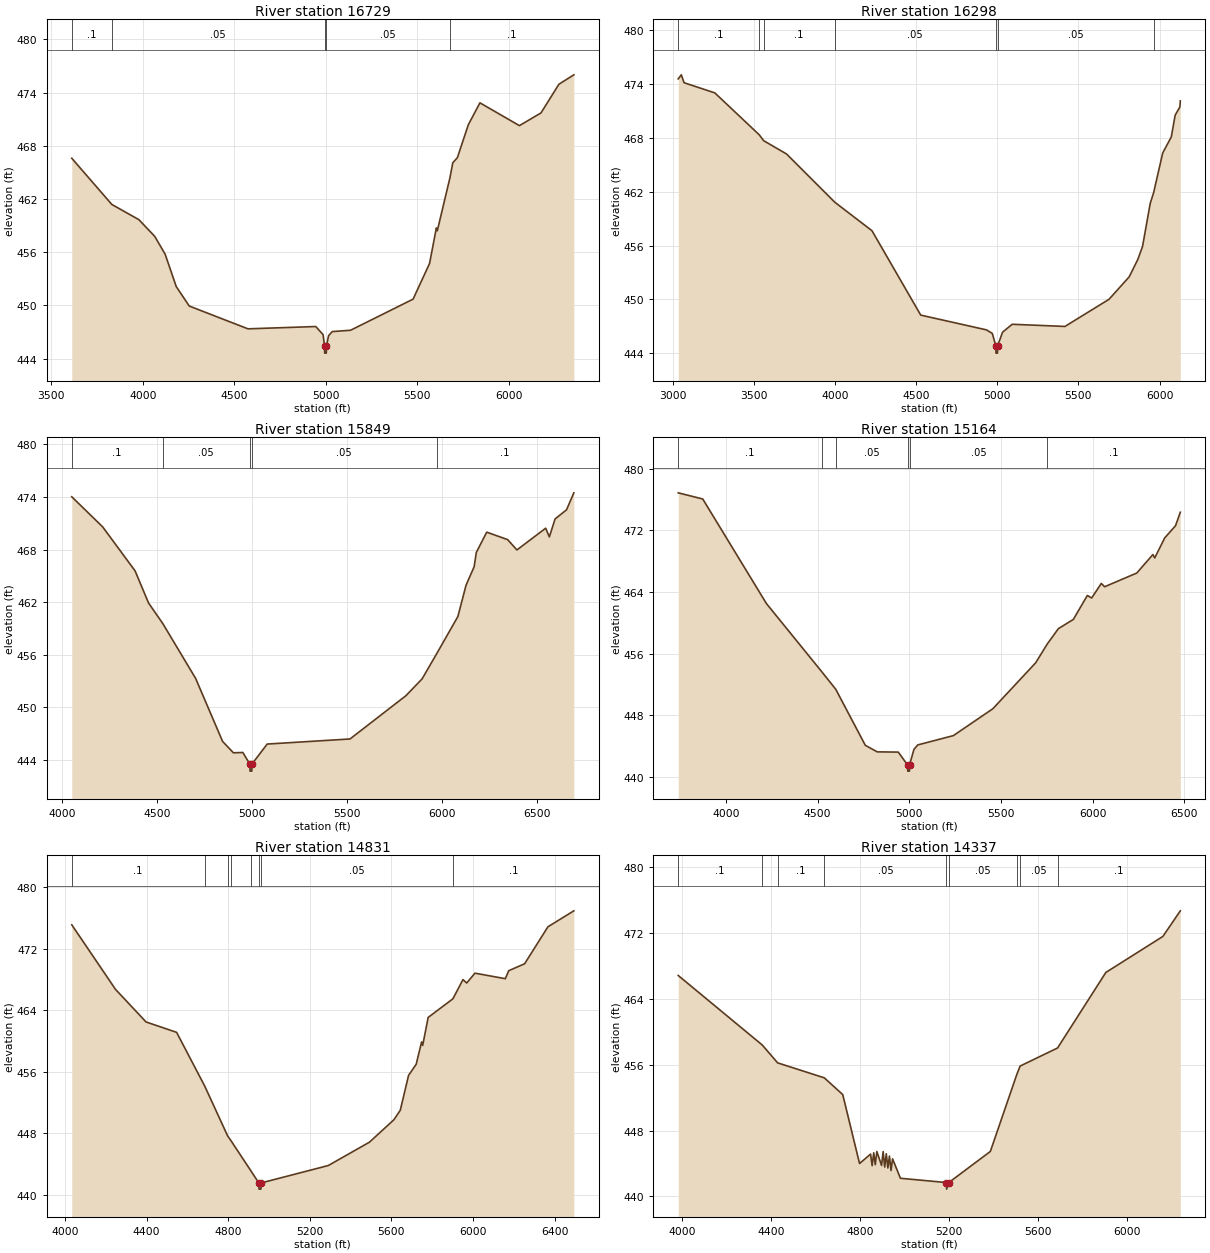
Type RM Length L Ch R = 1 ,16729   ,431,431,431
BEGIN DESCRIPTION:
Mapping XS 11703f79
END DESCRIPTION:
XS GIS Cut Line= 4
      2026495.99     13459545.23      2026370.13     13458894.22
      2026409.19     13457952.38      2026148.78     13456845.62
#Sta/Elev= 30
  3611.9   466.6  3830.7  461.39  3978.8  459.67  4065.1  457.79    4122  455.78
  4182.5  452.13  4253.8  449.93  4574.4  447.36  4944.8  447.62  4984.8  446.71
  4992.6  445.42  4993.5  444.62  5002.2  444.62  5003.1  445.42  5014.8  446.59
  5034.8  447.05  5134.9   447.2  5476.5  450.71  5566.4  454.73  5603.6  458.74
  5608.7  458.42  5677.9  464.41  5693.5   466.1  5718.3  466.66  5778.2  470.38
  5841.6  472.85  6057.3  470.28    6175  471.71  6273.1  474.95  6354.6  476.01
#Mann= 5 ,-1 , 0
  3611.9      .1       0  3830.7     .05       0  4992.6    .035       0
  5003.1     .05       0  5677.9      .1       0
Bank Sta=4992.6,5003.1
XS Rating Curve= 0 ,0
Exp/Cntr=0.3,0.1

Type RM Length L Ch R = 1 ,16298   ,449,449,449
BEGIN DESCRIPTION:
Mapping XS d886d261
END DESCRIPTION:
XS GIS Cut Line= 4
      2027005.47      13460249.2      2026452.59     13458562.62
      2026671.34     13458221.48      2026318.15     13457379.71
#Sta/Elev= 30
    3035  474.55  3053.9     475    3071  474.12  3260.4  472.99  3533.8  468.33
  3561.5  467.67  3702.4  466.19  3999.1  460.83  4228.6  457.65  4528.9  448.26
  4933.3  446.62  4969.6  446.23  4991.8  444.83  4992.7  444.03  5001.6  444.03
  5002.4  444.83    5033  446.36  5092.2  447.24  5417.4     447  5688.9  450.02
  5813.1  452.52  5866.1  454.45  5895.3   455.9  5942.8   460.7  5963.6  461.88
  6019.5   466.3  6072.5  468.09  6096.3  470.51  6125.4  471.42    6128   472.1
#Mann= 7 ,-1 , 0
    3035      .1       0  3533.8     .05       0  3561.5      .1       0
  3999.1     .05       0  4991.8    .035       0  5002.4     .05       0
  5963.6      .1       0
Bank Sta=4991.8,5002.4
XS Rating Curve= 0 ,0
Exp/Cntr=0.3,0.1

Type RM Length L Ch R = 1 ,15849   ,685,685,685
BEGIN DESCRIPTION:
UNT 042 in RCW 25.0
END DESCRIPTION:
XS GIS Cut Line= 3
      2027524.99     13459174.99      2026845.82     13458428.94
      2026265.86     13456905.38
#Sta/Elev= 30
  4052.5  474.03    4215  470.59  4385.3  465.57  4456.2   461.9  4530.6  459.57
  4703.5   453.3  4845.4   446.1  4902.2   444.8  4951.5  444.84  4988.7  443.51
  4989.6  442.71  4998.6  442.71  4999.4  443.51  5079.7   445.8    5515  446.38
  5808.9  451.32  5893.9  453.24  5969.8  456.08  6082.1  460.36  6124.9  463.93
  6167.7  466.05  6178.9  467.67  6233.7  469.99  6343.5  469.14  6392.4  467.96
  6543.5  470.44  6562.9  469.45    6593   471.5  6653.2  472.54  6691.6  474.48
#Mann= 5 ,-1 , 0
  4052.5      .1       0  4530.6     .05       0  4988.7    .035       0
  4999.4     .05       0  5969.8      .1       0
Bank Sta=4988.7,4999.4
XS Rating Curve= 0 ,0
Exp/Cntr=0.3,0.1

Type RM Length L Ch R = 1 ,15164   ,333,333,333
BEGIN DESCRIPTION:
UNT 042 in RCW 24.0
END DESCRIPTION:
XS GIS Cut Line= 4
      2027885.69     13459087.76      2027384.02     13458317.83
      2026738.18     13457838.66      2026339.39     13456906.84
#Sta/Elev= 30
  3740.6  476.87  3874.2  476.07  4221.3   462.5  4524.3  453.61  4599.3  451.37
  4760.4   444.1  4825.1  443.25  4939.9  443.22  4990.8  441.55  4991.7  440.75
  5000.7  440.75  5001.5  441.55  5025.4  443.57  5046.2  444.15  5240.3  445.36
  5455.2  448.84  5689.3  454.82  5752.1  457.25  5812.6  459.24  5894.3  460.44
  5970.5  463.55  5994.1  463.22  6046.7  465.11  6064.8  464.68    6240  466.46
  6327.9  468.86  6337.9  468.42  6392.3  471.02  6451.2   472.6  6477.3  474.35
#Mann= 6 ,-1 , 0
  3740.6      .1       0  4524.3     .07       0  4599.3     .05       0
  4990.8    .033       0  5001.5     .05       0  5752.1      .1       0
Bank Sta=4990.8,5001.5
XS Rating Curve= 0 ,0
Exp/Cntr=0.3,0.1

Type RM Length L Ch R = 1 ,14831   ,494,494,494
BEGIN DESCRIPTION:
UNT 042 in RCW 23.0
END DESCRIPTION:
XS GIS Cut Line= 3
      2027875.24     13458915.82      2027272.91     13457741.44
      2026922.13     13456655.43
#Sta/Elev= 30
  4033.2  475.14  4247.7  466.74  4397.3   462.5  4547.1  461.15  4684.5  454.18
  4797.2  447.68  4812.2  447.11  4909.8  443.19  4950.3  441.55  4951.2  440.75
  4960.2  440.75    4961  441.55  5290.5  443.82  5491.9  446.85    5612  449.77
  5643.5  451.01  5684.1  455.55  5721.4  456.99  5748.1   459.9  5753.4  459.45
  5780.2  463.09  5901.4  465.51  5950.8  468.01  5969.3  467.57  6009.6  468.85
  6158.5  468.13  6175.1  469.17    6253  470.07  6367.2  474.88  6494.3  476.96
#Mann= 8 ,-1 , 0
  4033.2      .1       0  4684.5     .07       0  4797.2     .05       0
  4812.2     .07       0  4909.8     .05       0  4950.3    .033       0
    4961     .05       0  5901.4      .1       0
Bank Sta=4950.3,4961
XS Rating Curve= 0 ,0
Exp/Cntr=0.3,0.1

Type RM Length L Ch R = 1 ,14337   ,95,95,95
BEGIN DESCRIPTION:
Mapping XS c0ab99b8
END DESCRIPTION:
XS GIS Cut Line= 5
      2027963.88     13458665.05      2027981.24      13458109.5
      2027981.24     13457925.47      2027640.96     13457581.72
      2027000.28     13456770.05
#Sta/Elev= 30
  3982.6  466.86  4360.4  458.41  4429.5  456.24  4639.3  454.42  4722.4  452.38
  4797.9     444  4847.4  445.15  4854.5  443.74  4861.6  445.31  4868.6  443.86
  4875.7  445.46  4896.9  443.77    4904  445.45    4911  443.58  4918.1  445.19
  4925.2  443.46  4932.3  444.91  4939.3  443.15  4946.4  444.57  4981.7  442.21
  5188.5  441.69  5189.4  440.89  5199.2  441.69    5386  445.47  5504.9  454.82
  5519.9  455.85  5688.4  458.05  5905.4  467.23  6161.9  471.61  6240.2  474.72
#Mann= 9 ,-1 , 0
  3982.6      .1       0  4360.4     .05       0  4429.5      .1       0
  4639.3     .05       0  5188.5    .033       0  5199.2     .05       0
  5504.9      .1       0  5519.9     .05       0  5688.4      .1       0
Bank Sta=5188.5,5199.2
XS Rating Curve= 0 ,0
Exp/Cntr=0.3,0.1

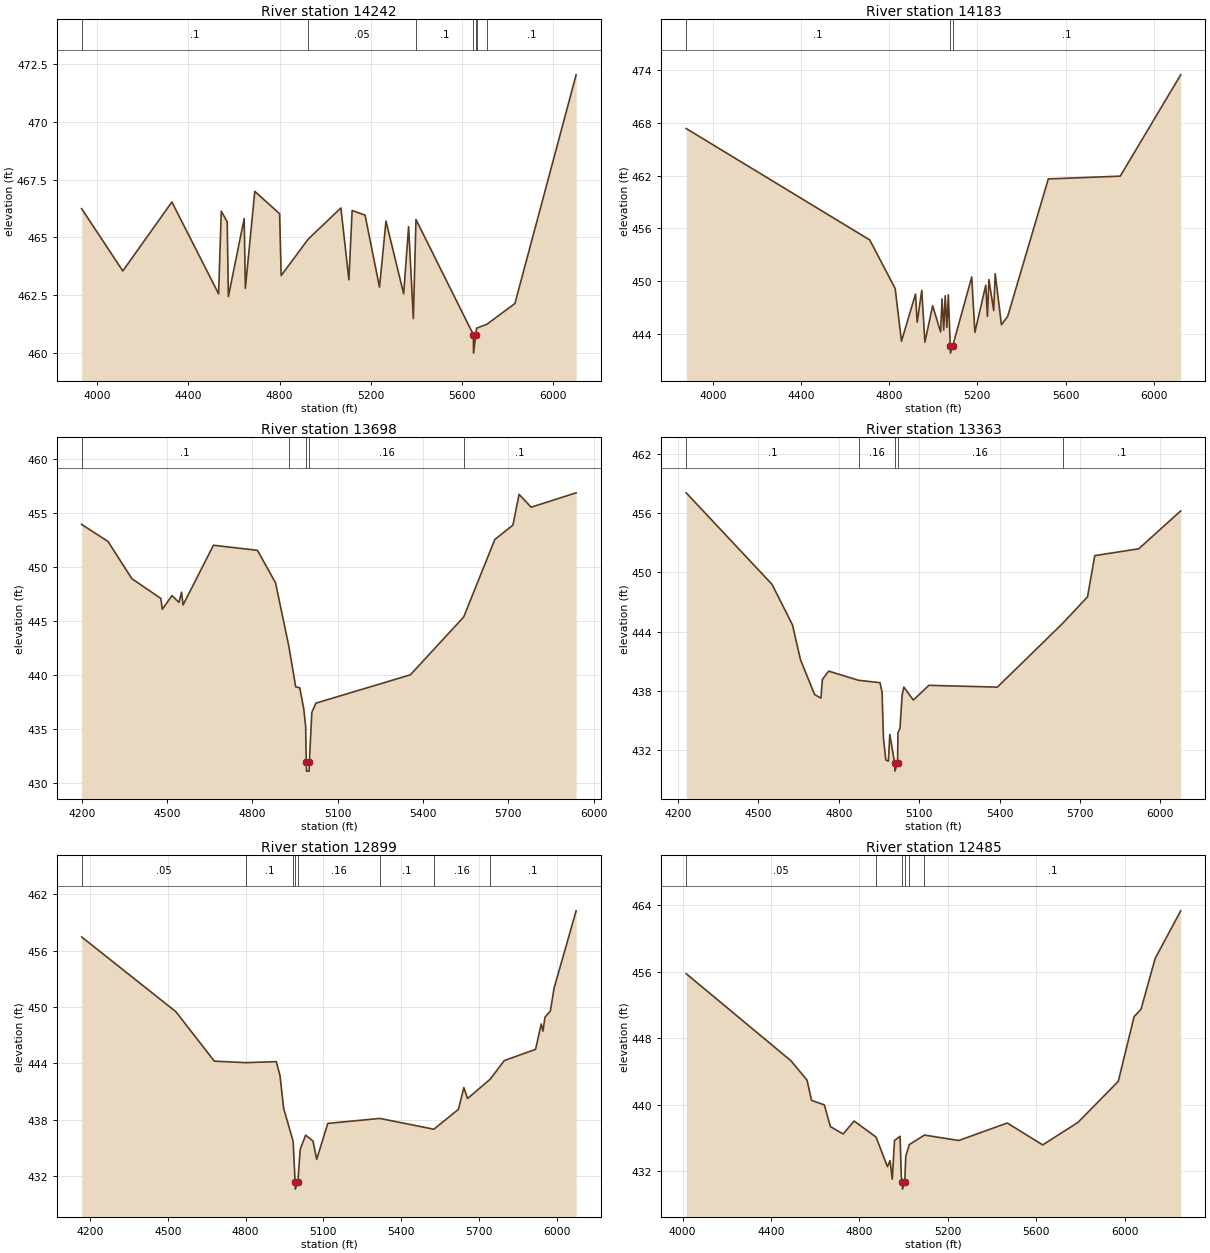
Type RM Length L Ch R = 1 ,14242   ,59,59,59
BEGIN DESCRIPTION:
Mapping XS 4db0fac5
END DESCRIPTION:
XS GIS Cut Line= 6
      2028012.49     13458654.59      2028057.63     13458286.58
      2028081.93     13458033.11      2028064.57     13457897.69
      2027929.16     13457744.91      2027120.86     13456849.04
#Sta/Elev= 30
  3930.6  466.24  4111.5  463.54  4327.1  466.53  4532.4  462.55  4544.1  466.13
  4570.2  465.67  4575.3  462.43  4644.8  465.81  4649.9  462.79  4691.4  466.99
  4800.6  466.02  4807.3  463.34    4926  464.92  5069.7  466.27  5104.9  463.16
  5119.1  466.16  5175.9  465.96  5239.4  462.84  5267.8   465.7  5345.5  462.55
  5367.2  465.46  5388.1  461.48  5399.6  465.77  5651.8  460.78  5652.6  459.98
  5662.5  460.78  5665.8  461.06  5711.1  461.23  5834.3  462.13  6103.3  472.04
#Mann= 7 ,-1 , 0
  3930.6      .1       0    4926     .05       0  5399.6      .1       0
  5651.8    .033       0  5662.5      .1       0  5665.8     .05       0
  5711.1      .1       0
Bank Sta=5651.8,5662.5
XS Rating Curve= 0 ,0
Exp/Cntr=0.3,0.1

Type RM Length L Ch R = 1 ,14183   ,485,485,485
BEGIN DESCRIPTION:
Mapping XS ed5f1193
END DESCRIPTION:
XS GIS Cut Line= 5
      2028047.21     13458668.55      2028137.49     13458050.47
      2028120.13     13457904.64       2028061.1     13457807.41
      2027161.68     13456790.82
#Sta/Elev= 30
  3879.7  467.34  4712.2  454.68  4827.6  449.15    4856  443.17  4919.6  448.53
  4927.2  445.33  4948.1  448.95  4962.3  443.07  4997.4   447.2  5033.4  444.23
  5040.1  447.98  5047.6  444.44  5054.3  448.34  5061.8  444.75  5068.5  448.45
  5077.4  442.62  5078.2  441.82  5088.1  442.62  5174.7  450.47    5189  444.18
  5238.3  449.54  5245.8  445.99  5252.5  450.18  5274.3  446.66    5281  450.85
  5309.4  445.05  5337.8     446  5521.9  461.61  5848.1  461.93  6122.3  473.44
#Mann= 3 ,-1 , 0
  3879.7      .1       0  5077.4     .07       0  5088.1      .1       0
Bank Sta=5077.4,5088.1
XS Rating Curve= 0 ,0
Exp/Cntr=0.3,0.1

Type RM Length L Ch R = 1 ,13698   ,335,335,335
BEGIN DESCRIPTION:
Mapping XS 19478d95
END DESCRIPTION:
XS GIS Cut Line= 3
      2028272.89     13458144.26      2028418.74     13457630.33
      2027607.16     13456738.98
#Sta/Elev= 30
  4199.1  453.92  4291.9  452.34  4375.9  448.89  4477.7  447.07  4482.9  446.06
  4516.8  447.33  4541.4   446.7  4550.7  447.65  4555.9  446.46  4662.8  451.99
  4817.7  451.52  4881.3  448.51  4927.9  442.67  4952.2  438.89  4966.4   438.8
  4980.6  436.85  4987.3   435.2  4989.4  431.89  4990.2  431.09  4999.3  431.09
  5000.1  431.89    5009  436.52  5023.2  437.38  5355.6     440  5543.2  445.35
  5652.9  452.53  5716.4  453.85    5738   456.7  5780.6  455.51  5938.8  456.84
#Mann= 5 ,-1 , 0
  4199.1      .1       0  4927.9     .16       0  4989.4     .07       0
  5000.1     .16       0  5543.2      .1       0
Bank Sta=4989.4,5000.1
XS Rating Curve= 0 ,0
Exp/Cntr=0.3,0.1

Type RM Length L Ch R = 1 ,13363   ,464,464,464
BEGIN DESCRIPTION:
UNT 042 in RCW 20.0
END DESCRIPTION:
XS GIS Cut Line= 3
      2028779.85     13458019.23      2028467.35     13457293.53
      2027630.51     13456651.14
#Sta/Elev= 30
  4230.7  458.06    4551  448.79  4627.3  444.68  4657.3  441.15  4709.8  437.63
  4733.4  437.26  4738.8  439.15  4762.3     440  4873.9  439.07  4953.9  438.83
  4961.5  437.87  4966.9  433.13  4975.7  430.99    4985  430.88  4990.4  433.59
  5008.6  430.67  5009.4  429.87  5019.3  430.67  5020.8  433.75  5028.4  434.22
  5036.4  437.59  5042.9  438.38  5078.2  437.07  5136.3  438.56  5391.8  438.38
  5635.5  444.84  5728.1  447.52  5755.2   451.7  5919.3  452.39  6075.8  456.23
#Mann= 5 ,-1 , 0
  4230.7      .1       0  4873.9     .16       0  5008.6     .07       0
  5019.3     .16       0  5635.5      .1       0
Bank Sta=5008.6,5019.3
XS Rating Curve= 0 ,0
Exp/Cntr=0.3,0.1

Type RM Length L Ch R = 1 ,12899   ,414,414,414
BEGIN DESCRIPTION:
UNT 042 in RCW 19.0
END DESCRIPTION:
XS GIS Cut Line= 3
      2028949.99     13458050.48      2028835.41     13457474.08
      2027974.99     13456474.98
#Sta/Elev= 30
  4168.3  457.48  4531.5  449.52  4679.8  444.25  4801.2  444.09  4918.6   444.2
  4932.9  442.72  4947.1  439.21  4983.7  435.71  4991.1  431.42    4992  430.62
  5001.9  431.42  5010.8  434.86  5031.9  436.37  5060.2  435.74  5074.4   433.8
  5117.2  437.62  5317.7  438.15    5526     437  5620.8  439.12  5641.7  441.44
  5655.9  440.27    5743  442.32  5797.5  444.31  5918.1  445.51  5940.1  448.21
  5946.7  447.45  5954.3  448.93  5975.2  449.59  5989.4  452.02  6074.5  460.26
#Mann= 8 ,-1 , 0
  4168.3     .05       0  4801.2      .1       0  4983.7     .16       0
  4991.1     .07       0  5001.9     .16       0  5317.7      .1       0
    5526     .16       0    5743      .1       0
Bank Sta=4991.1,5001.9
XS Rating Curve= 0 ,0
Exp/Cntr=0.3,0.1

Type RM Length L Ch R = 1 ,12485   ,527,527,527
BEGIN DESCRIPTION:
Mapping XS 3afc4143
END DESCRIPTION:
XS GIS Cut Line= 4
      2029439.54     13457977.52      2028925.68     13457324.78
      2028849.29     13456925.47      2027993.19     13456409.03
#Sta/Elev= 30
  4016.3  455.77  4490.6  445.29  4562.8  442.98  4583.6  440.53  4641.4  439.99
  4668.6  437.38  4726.4  436.49  4776.1  438.05  4875.2  436.12  4926.8  432.56
  4938.4  433.28  4948.6  431.06  4958.8  435.72    4984  436.21  4989.3  431.42
  4994.1  430.66  4994.9  429.86  5004.9  430.66  5009.7  433.83  5025.8  435.22
  5094.3  436.36  5249.4  435.71  5468.8  437.81  5629.2  435.18  5788.4  437.88
    5971  442.82  6042.7  450.61  6073.8  451.49  6137.8  457.59  6253.4  463.33
#Mann= 6 ,-1 , 0
  4016.3     .05       0  4875.2      .1       0  4994.1     .07       0
  5004.9      .1       0  5025.8     .16       0  5094.3      .1       0
Bank Sta=4994.1,5004.9
XS Rating Curve= 0 ,0
Exp/Cntr=0.3,0.1

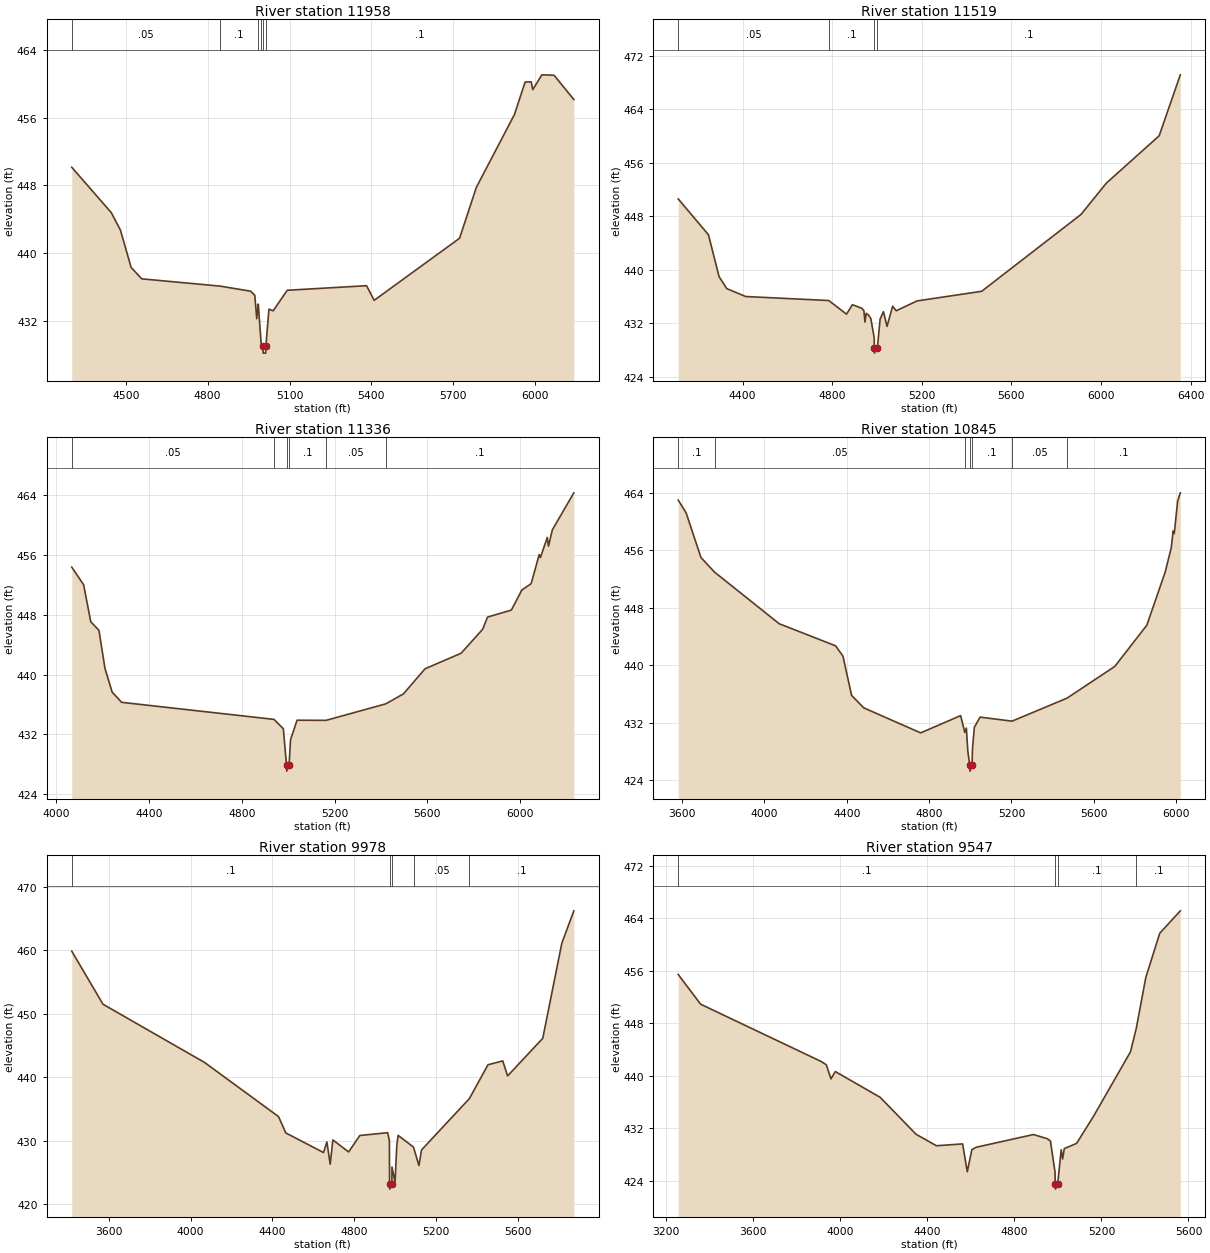
Type RM Length L Ch R = 1 ,11958   ,439,439,439
BEGIN DESCRIPTION:
Mapping XS bac0ed12
END DESCRIPTION:
XS GIS Cut Line= 3
      2029300.68     13457366.43      2029165.27     13456894.22
       2027960.4     13456290.05
#Sta/Elev= 30
  4302.4  450.14  4447.1  444.78  4480.7  442.71  4519.8   438.3  4558.8  436.95
  4846.5  436.09  4957.7  435.49  4972.9     435    4980  432.24  4984.1  433.51
  4985.6  433.97  4996.5  429.13  5002.6  428.97  5003.4  428.17  5012.6  428.17
  5013.4  428.97  5024.7  433.37    5040  433.17  5091.7   435.6  5382.2  436.14
  5410.1  434.41  5722.9  441.75  5784.3  447.76    5924  456.38    5963  460.22
  5985.3  460.24    5991  459.32  6024.5  461.07  6069.2  461.02  6141.5  458.15
#Mann= 6 ,-1 , 0
  4302.4     .05       0  4846.5      .1       0  4984.1     .16       0
  4996.5      .1       0  5002.6     .07       0  5013.4      .1       0
Bank Sta=5002.6,5013.4
XS Rating Curve= 0 ,0
Exp/Cntr=0.3,0.1

Type RM Length L Ch R = 1 ,11519   ,183,183,183
BEGIN DESCRIPTION:
UNT 042 in RCW 18.0
END DESCRIPTION:
XS GIS Cut Line= 3
      2029328.46     13457335.18      2029134.02     13456626.86
      2028768.06     13455164.58
#Sta/Elev= 30
  4112.5  450.61  4247.5  445.25  4294.9  438.98  4329.3  437.19  4413.7  436.01
  4784.7  435.41    4864  433.37  4890.2  434.79  4931.4  434.26  4941.3  433.94
  4946.4  432.19    4952  433.49  4962.3  433.23  4972.6  432.71  4987.6   429.8
  4987.8  428.34  4988.5  427.54  4998.8  428.34  5003.6  428.94  5013.9  432.63
  5028.8  433.75  5044.8  431.55    5070  434.56    5086  433.88  5178.8  435.35
  5467.4  436.79  5910.7  448.28  6024.1  452.97    6260  460.06  6354.4  469.18
#Mann= 4 ,-1 , 0
  4112.5     .05       0  4784.7      .1       0  4987.8     .07       0
  4998.8      .1       0
Bank Sta=4987.8,4998.8
XS Rating Curve= 0 ,0
Exp/Cntr=0.3,0.1

Type RM Length L Ch R = 1 ,11336   ,491,491,491
BEGIN DESCRIPTION:
UNT 042 in RCW 17.0
END DESCRIPTION:
XS GIS Cut Line= 3
      2029424.99     13457274.97      2029245.13     13456456.72
      2028901.39     13455175.52
#Sta/Elev= 30
  4067.1  454.37  4118.3  452.01    4149  447.07  4184.2  445.92  4210.4  440.81
  4241.1  437.66  4282.1  436.29  4938.9  434.01  4979.1  432.76  4992.8  427.89
  4993.5  427.09  5003.8  427.89  5010.2  431.29  5038.3   433.9  5163.2  433.88
  5420.9  436.09  5496.8  437.42    5590  440.78  5745.3  442.85  5838.5  446.07
  5859.2  447.69  5962.1  448.63  6007.3  451.31  6047.3  452.16  6082.1  456.05
  6087.3  455.65  6116.9  458.35  6122.1  457.18  6138.8  459.36  6231.4  464.31
#Mann= 6 ,-1 , 0
  4067.1     .05       0  4938.9      .1       0  4992.8     .07       0
  5003.8      .1       0  5163.2     .05       0  5420.9      .1       0
Bank Sta=4992.8,5003.8
XS Rating Curve= 0 ,0
Exp/Cntr=0.3,0.1

Type RM Length L Ch R = 1 ,10845   ,867,867,867
BEGIN DESCRIPTION:
Mapping XS 53e53c8d
END DESCRIPTION:
XS GIS Cut Line= 3
      2030505.56     13457178.95       2029811.1     13456692.83
      2029085.41     13455276.18
#Sta/Elev= 30
  3581.2  462.98  3619.4  461.23  3691.7     455  3757.7  452.97  4071.9  445.79
  4345.7  442.72  4381.5  441.29  4423.5  435.83  4482.6  434.09  4759.1  430.61
  4953.3  433.01  4973.6  430.68  4981.1  431.28  4988.2  428.06  4997.8  426.09
  4998.6  425.29  5008.8  426.09  5010.7  428.37  5019.9  431.39  5047.7   432.8
  5202.9  432.24  5470.2  435.44  5702.6  439.86    5858  445.59  5946.8  452.95
    5977   456.4  5985.6  458.69  5991.2  458.33  6007.8  462.88  6020.6     464
#Mann= 7 ,-1 , 0
  3581.2      .1       0  3757.7     .05       0  4973.6      .1       0
  4997.8     .07       0  5008.8      .1       0  5202.9     .05       0
  5470.2      .1       0
Bank Sta=4997.8,5008.8
XS Rating Curve= 0 ,0
Exp/Cntr=0.3,0.1

Type RM Length L Ch R = 1 ,9978    ,431,431,431
BEGIN DESCRIPTION:
Mapping XS aea4cbdb
END DESCRIPTION:
XS GIS Cut Line= 3
      2030509.01     13457109.49      2029970.82     13455817.83
      2029095.83     13455234.51
#Sta/Elev= 30
  3420.4  459.89  3572.7  451.53  4068.8  442.35  4429.6  433.83  4465.3  431.25
  4649.4  428.16  4665.8  429.84  4681.9  426.32    4695  430.15  4771.9  428.26
  4826.7  430.85  4962.5  431.29  4970.9  430.01  4971.9   423.2  4972.7   422.4
    4983   423.2  4983.5  425.88  4998.5  423.51    5007  429.23  5013.5  430.87
  5088.6  429.02  5115.1  426.11  5127.7  428.57  5361.1  436.65  5452.2  441.99
  5524.3   442.6  5547.8  440.23  5719.6  446.16  5812.8  461.16  5871.3  466.24
#Mann= 5 ,-1 , 0
  3420.4      .1       0  4971.9     .07       0    4983      .1       0
  5088.6     .05       0  5361.1      .1       0
Bank Sta=4971.9,4983
XS Rating Curve= 0 ,0
Exp/Cntr=0.3,0.1

Type RM Length L Ch R = 1 ,9547    ,633,633,633
BEGIN DESCRIPTION:
Mapping XS 9cd63fd2
END DESCRIPTION:
XS GIS Cut Line= 3
      2030550.68     13456994.89      2030265.96     13455866.44
      2029489.07     13455027.12
#Sta/Elev= 30
    3255  455.46    3358  450.93  3910.8  442.22  3935.6   441.7    3957  439.55
  3976.8  440.67  4183.1  436.74  4348.1  431.11  4441.8  429.36    4562  429.64
  4583.5   425.4  4604.5  428.77  4625.5  429.14  4887.4  431.07  4951.5  430.43
  4965.6  430.08  4986.6  425.37  4987.9  423.55  4988.6  422.75    4999  423.55
    5015  428.75  5021.8  427.35  5029.2  428.93  5085.8  429.72  5163.5  433.84
  5333.6  443.68  5359.8   447.2  5403.9     455    5468  461.74  5562.5  465.16
#Mann= 4 ,-1 , 0
    3255      .1       0  4987.9     .03       0    4999      .1       0
  5359.8      .1       0
Bank Sta=4987.9,4999
XS Rating Curve= 0 ,0
Exp/Cntr=0.3,0.1

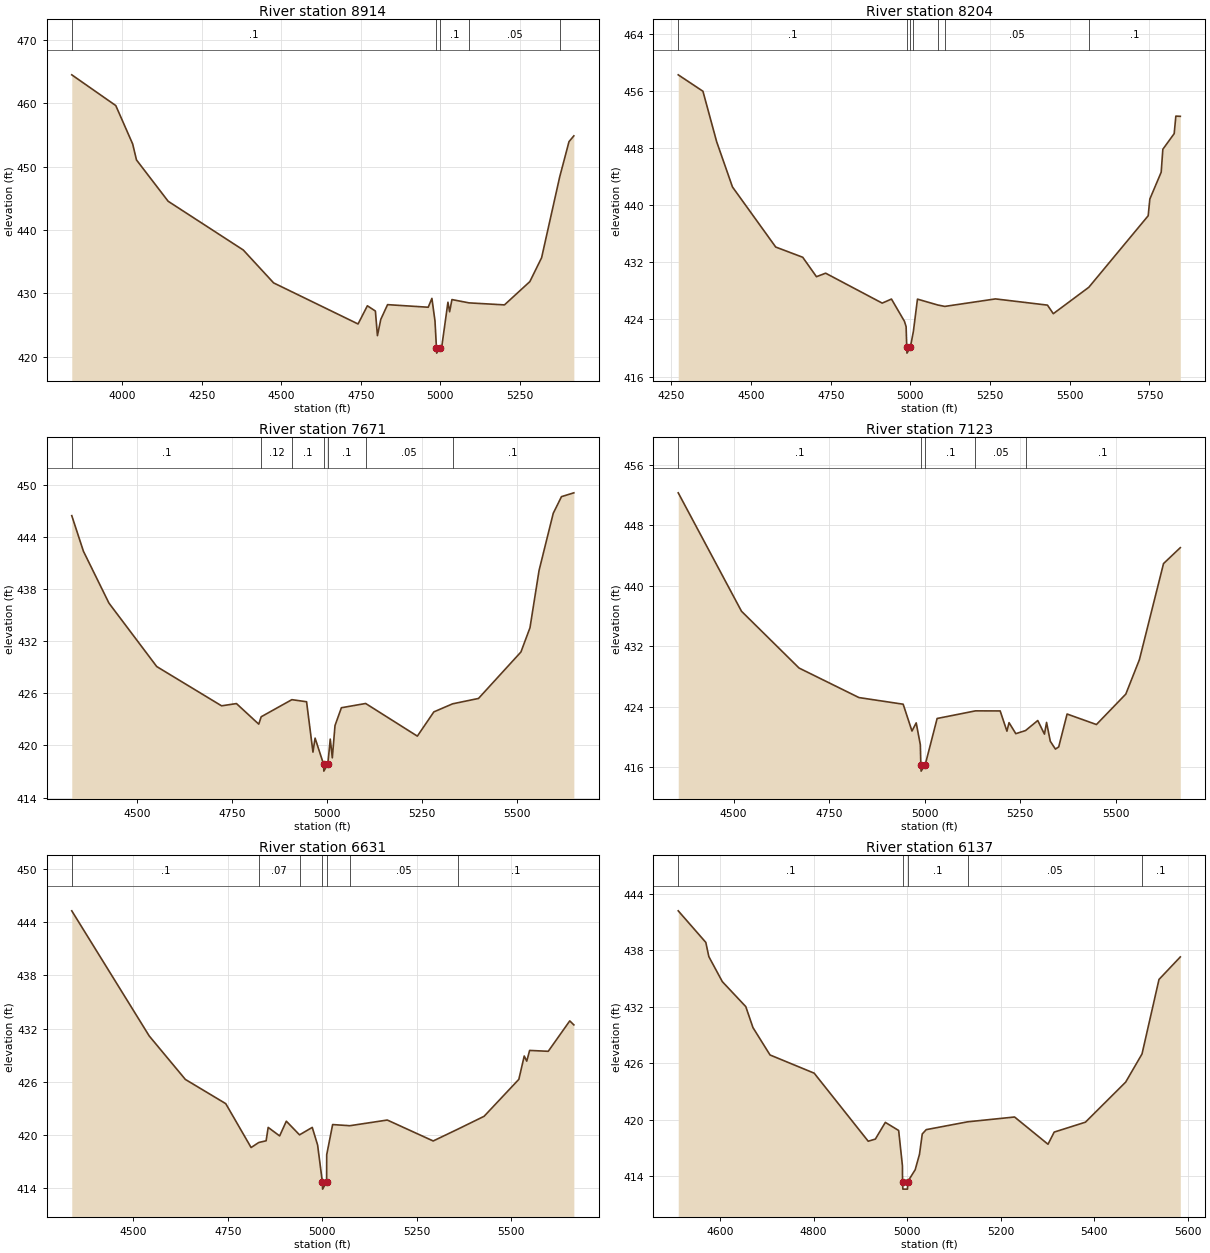
Type RM Length L Ch R = 1 ,8914    ,710,710,710
BEGIN DESCRIPTION:
UNT 042 in RCW 14.0
END DESCRIPTION:
XS GIS Cut Line= 3
      2030705.21     13456442.87      2030351.03     13455592.14
      2030125.02     13454975.04
#Sta/Elev= 30
  3841.2  464.47  3979.6  459.62  4032.7  453.56  4044.7  451.04  4144.3  444.52
  4380.5  436.83  4475.9  431.64  4741.4  425.16  4770.7  428.03  4795.9   427.2
  4802.3  423.32  4812.9  425.89  4834.2  428.21    4962   427.8  4973.6   429.2
  4983.3  425.63  4987.9  421.36  4988.6  420.56  4999.1  421.36  5004.6  421.57
    5024  428.59  5029.3  427.09  5036.6  429.01  5090.2  428.49  5201.7  428.17
  5281.5  431.84  5318.5  435.61  5375.4  448.36  5404.7  453.93  5419.9  454.84
#Mann= 5 ,-1 , 0
  3841.2      .1       0  4987.9     .07       0  4999.1      .1       0
  5090.2     .05       0  5375.4      .1       0
Bank Sta=4987.9,4999.1
XS Rating Curve= 0 ,0
Exp/Cntr=0.3,0.1

Type RM Length L Ch R = 1 ,8204    ,533,533,533
BEGIN DESCRIPTION:
UNT 042 in RCW 13.0
END DESCRIPTION:
XS GIS Cut Line= 3
      2031074.98     13456074.98      2030715.61      13455633.8
      2030465.84     13454659.01
#Sta/Elev= 30
  4271.5  458.25    4349  455.95  4392.1  448.88  4441.7  442.55  4577.4  434.14
  4662.1  432.71  4705.2  429.99    4734  430.48  4911.5  426.29  4940.5  426.86
  4981.3  423.74  4986.5  422.99  4988.5  420.09  4989.2  419.29  4999.7  420.09
  5009.3  422.33  5022.1  426.85  5085.6  426.03  5107.9  425.83  5266.9  426.88
    5430  426.01  5448.3  424.81  5559.8  428.51    5746  438.52  5751.2  440.86
  5786.8  444.62    5792  447.83  5827.6  450.02  5832.8  452.47  5846.8  452.44
#Mann= 7 ,-1 , 0
  4271.5      .1       0  4988.5     .07       0  4999.7      .1       0
  5009.3     .07       0  5085.6      .1       0  5107.9     .05       0
  5559.8      .1       0
Bank Sta=4988.5,4999.7
XS Rating Curve= 0 ,0
Exp/Cntr=0.3,0.1

Type RM Length L Ch R = 1 ,7671    ,548,548,548
BEGIN DESCRIPTION:
UNT 042 in RCW 12.0
END DESCRIPTION:
XS GIS Cut Line= 3
      2031324.99     13455824.98        2031025.       13455225.
        2030775.       13454625.
#Sta/Elev= 30
  4328.7  446.46  4359.4  442.36  4426.5  436.39  4552.3  429.08  4722.8  424.56
  4761.9  424.82  4820.6  422.45    4827   423.3  4907.7  425.27  4946.4  425.03
  4963.2  419.23  4968.8  420.84  4991.1  417.84  4991.8  417.04  5002.3  417.84
  5008.7  420.73  5014.1  418.57  5021.2  422.29    5038  424.34  5101.8  424.83
  5237.8  421.07  5281.2  423.86  5330.5  424.79  5398.7  425.41  5510.3  430.76
  5534.1  433.55    5558  440.15  5595.3  446.73    5617  448.65  5649.5  449.09
#Mann= 7 ,-1 , 0
  4328.7      .1       0    4827     .12       0  4907.7      .1       0
  4991.1     .07       0  5002.3      .1       0  5101.8     .05       0
  5330.5      .1       0
Bank Sta=4991.1,5002.3
XS Rating Curve= 0 ,0
Exp/Cntr=0.3,0.1

Type RM Length L Ch R = 1 ,7123    ,492,492,492
BEGIN DESCRIPTION:
UNT 042 in RCW 11.0
END DESCRIPTION:
XS GIS Cut Line= 3
      2031528.11     13455869.87      2031482.97     13455310.89
      2031174.99     13454624.97
#Sta/Elev= 30
  4355.5  452.31  4520.9  436.63  4671.4  429.11    4828   425.2  4943.6  424.32
  4966.6  420.77  4977.7  421.85  4988.5  418.95  4989.8  416.26  4990.5  415.46
    5001  416.26  5032.4  422.43  5132.7  423.44  5197.2  423.43  5214.9  420.75
  5220.4  421.88  5238.1  420.42  5263.5  420.83  5295.5  422.16    5313  420.36
  5318.5  421.91  5328.3  419.41  5341.7  418.38  5350.3  418.67  5372.2  423.02
  5448.9  421.63  5525.7  425.66  5561.2  430.21  5624.3  442.94  5668.2  445.05
#Mann= 5 ,-1 , 0
  4355.5      .1       0  4989.8     .07       0    5001      .1       0
  5132.7     .05       0  5263.5      .1       0
Bank Sta=4989.8,5001
XS Rating Curve= 0 ,0
Exp/Cntr=0.3,0.1

Type RM Length L Ch R = 1 ,6631    ,494,494,494
BEGIN DESCRIPTION:
UNT 042 in RCW 10.0
END DESCRIPTION:
XS GIS Cut Line= 3
        2032025.     13455575.01       2031705.2     13454790.05
      2031340.58     13454474.05
#Sta/Elev= 30
  4336.6  445.28  4541.8  431.17  4637.5  426.27  4744.5  423.54  4811.7  418.59
  4832.1  419.16  4851.5  419.35  4856.9  420.86  4887.3   419.9    4905  421.56
    4940  420.02  4973.7  420.86  4987.9  418.87  5000.5   414.7  5001.1   413.9
  5011.7   414.7    5012  417.78  5027.7  421.18  5073.2  421.05  5172.5  421.69
  5294.1  419.33  5359.8  420.67  5428.9  422.11    5521  426.28  5535.3  428.91
  5541.9  428.33  5549.6  429.54  5598.9  429.44  5655.9  432.87  5666.7  432.42
#Mann= 7 ,-1 , 0
  4336.6      .1       0  4832.1     .07       0    4940      .1       0
  5000.5     .07       0  5011.7      .1       0  5073.2     .05       0
  5359.8      .1       0
Bank Sta=5000.5,5011.7
XS Rating Curve= 0 ,0
Exp/Cntr=0.3,0.1

Type RM Length L Ch R = 1 ,6137    ,325,325,325
BEGIN DESCRIPTION:
UNT 042 in RCW 9.0
END DESCRIPTION:
XS GIS Cut Line= 3
      2032375.01     13455275.02      2032059.36     13454769.22
       2031802.4     13454366.42
#Sta/Elev= 30
  4510.3  442.17  4569.3  438.82  4575.8  437.31  4604.6  434.66  4654.8  432.01
  4670.2  429.78  4706.7  426.88  4801.1  424.95  4916.7  417.73    4932  417.96
  4953.3  419.73  4981.8  418.87  4989.9  415.13  4990.1  413.45  4990.8  412.65
  5000.7  412.65  5001.3  413.45  5017.2  414.71  5026.4  416.35  5032.3   418.5
  5040.8  418.96  5129.4  419.79  5229.8   420.3  5301.3  417.41  5314.5   418.7
  5381.3  419.75  5467.4     424  5502.4  426.99  5538.7  434.89  5584.3  437.28
#Mann= 5 ,-1 , 0
  4510.3      .1       0  4990.1     .07       0  5001.3      .1       0
  5129.4     .05       0  5502.4      .1       0
Bank Sta=4990.1,5001.3
XS Rating Curve= 0 ,0
Exp/Cntr=0.3,0.1