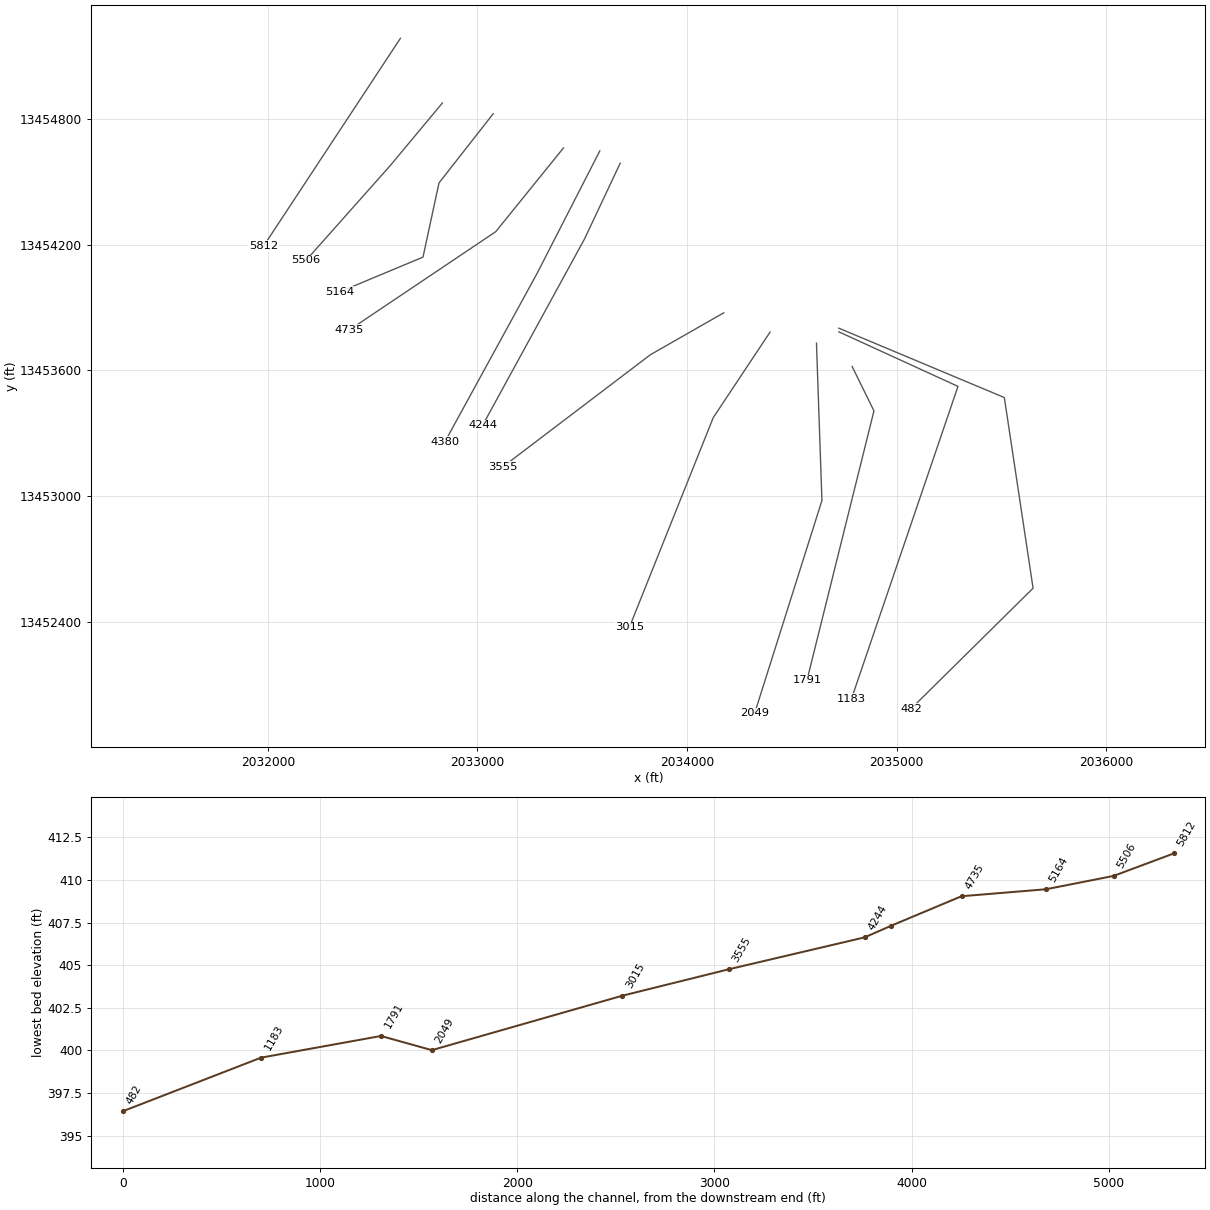
HEC-RAS study UNT 042 in RCW.prj: UNT 042 in RCW Base Level Engineering

--- UNT 042 in RCW.g01 (geometry) --- (continued)

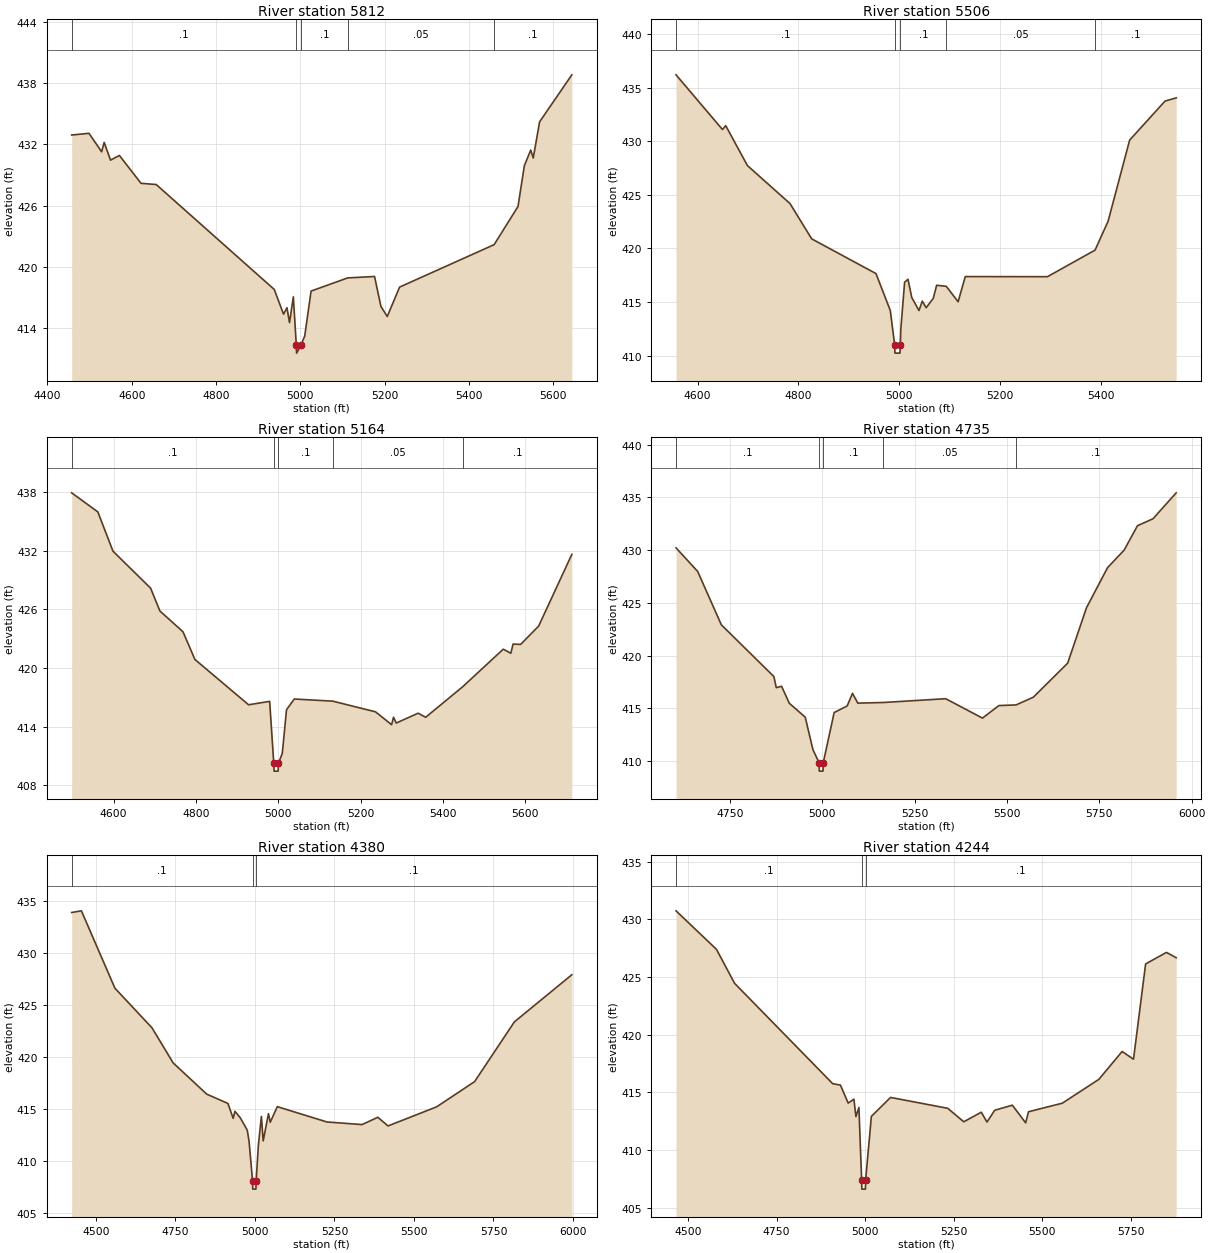
Type RM Length L Ch R = 1 ,5812    ,306,306,306
BEGIN DESCRIPTION:
Mapping XS 7af6f2de
END DESCRIPTION:
XS GIS Cut Line= 2
      2032632.16     13455184.77      2031979.47     13454193.81
#Sta/Elev= 30
  4457.4  432.92  4498.4  433.09  4528.5  431.28  4534.5   432.2  4549.6  430.46
  4570.6  430.92  4621.9  428.19    4658  428.07    4938  417.79    4960  415.37
  4968.2     416  4974.2  414.54  4983.3  417.07  4990.3  412.35    4991  411.55
  5001.6  412.35  5010.3  413.23  5025.4  417.63  5112.2  418.92    5176  419.06
    5191  416.13  5206.1  415.14  5235.4  418.02  5459.7  422.18  5516.3  425.92
  5531.4  429.92  5546.5  431.45  5552.5  430.67  5567.5  434.21    5644  438.82
#Mann= 5 ,-1 , 0
  4457.4      .1       0  4990.3     .07       0  5001.6      .1       0
  5112.2     .05       0  5459.7      .1       0
Bank Sta=4990.3,5001.6
XS Rating Curve= 0 ,0
Exp/Cntr=0.3,0.1

Type RM Length L Ch R = 1 ,5506    ,342,342,342
BEGIN DESCRIPTION:
UNT 042 in RCW 8.0
END DESCRIPTION:
XS GIS Cut Line= 3
      2032832.63     13454876.38      2032582.64     13454576.39
      2032182.63     13454126.38
#Sta/Elev= 30
  4557.3  436.19  4649.4  431.09  4655.9  431.45  4698.9  427.73  4783.5  424.18
  4826.5  420.89  4954.1  417.65  4982.5  414.21  4991.1  411.03  4991.8  410.23
  5001.7  410.23  5002.4  411.03  5003.4  412.47  5010.9  416.84  5017.6  417.12
  5025.1  415.42  5039.4   414.2    5046  415.08  5053.6  414.46  5067.8  415.34
  5074.5  416.56  5093.7  416.46  5117.1  415.02  5131.3  417.37  5294.4  417.36
  5388.9  419.84  5414.8  422.54  5457.5   430.1  5527.7  433.74  5549.9  434.04
#Mann= 5 ,-1 , 0
  4557.3      .1       0  4991.1     .07       0  5002.4      .1       0
  5093.7     .05       0  5388.9      .1       0
Bank Sta=4991.1,5002.4
XS Rating Curve= 0 ,0
Exp/Cntr=0.3,0.1

Type RM Length L Ch R = 1 ,5164    ,429,429,429
BEGIN DESCRIPTION:
UNT 042 in RCW 7.0
END DESCRIPTION:
XS GIS Cut Line= 4
        2033075.       13454825.      2032816.31     13454494.91
      2032739.92     13454140.75      2032340.59     13453974.07
#Sta/Elev= 30
  4498.4  437.93  4561.9  435.98  4598.7  431.96  4690.1  428.17  4712.6  425.84
  4768.7  423.71  4797.6  420.88  4927.9  416.24  4979.1  416.59  4989.1  410.25
  4989.8  409.45  4999.8  409.45  5000.4  410.25  5009.8  411.27    5020  415.73
  5038.9  416.83  5132.4  416.61  5236.1  415.52  5275.2   414.2  5279.9  414.97
  5286.4  414.37  5339.6  415.38  5357.9  414.96  5448.2   418.1  5546.3  421.93
  5564.7  421.51  5570.1  422.45  5588.5  422.42  5632.2  424.29  5712.8  431.63
#Mann= 5 ,-1 , 0
  4498.4      .1       0  4989.1     .07       0  5000.4      .1       0
  5132.4     .05       0  5448.2      .1       0
Bank Sta=4989.1,5000.4
XS Rating Curve= 0 ,0
Exp/Cntr=0.3,0.1

Type RM Length L Ch R = 1 ,4735    ,355,355,355
BEGIN DESCRIPTION:
Mapping XS eba0455e
END DESCRIPTION:
XS GIS Cut Line= 3
      2033410.08     13454661.61      2033087.14     13454262.28
      2032389.64      13453793.8
#Sta/Elev= 30
  4604.4  430.22    4663  427.98    4727  422.92  4869.3  418.01  4875.7  416.96
  4890.1  417.09  4910.9  415.48  4954.1  414.16  4974.9  411.08  4991.6  409.84
  4992.2  409.04  5002.2  409.04  5002.9  409.84  5032.4   414.6  5067.6  415.22
    5082  416.42  5096.4  415.49  5165.9  415.55  5334.3  415.91  5433.8  414.07
  5478.3  415.26  5524.8  415.32  5571.4  416.05  5664.4  419.28  5715.4  424.54
  5772.4  428.34  5817.4  430.01  5853.4  432.32  5895.4  432.98  5958.2  435.44
#Mann= 5 ,-1 , 0
  4604.4      .1       0  4991.6     .07       0  5002.9      .1       0
  5165.9     .05       0  5524.8      .1       0
Bank Sta=4991.6,5002.9
XS Rating Curve= 0 ,0
Exp/Cntr=0.3,0.1

Type RM Length L Ch R = 1 ,4380    ,136,136,136
BEGIN DESCRIPTION:
UNT 042 in RCW 6.0
END DESCRIPTION:
XS GIS Cut Line= 3
      2033583.68     13454647.71      2033285.06     13454064.36
      2032844.42     13453259.41
#Sta/Elev= 30
  4423.5  433.85  4454.1  434.01  4559.5  426.59  4676.1  422.79  4742.8  419.42
  4848.2  416.43  4914.8  415.54  4931.4  414.11    4937  414.78  4953.6  414.17
  4975.8  412.97  4981.4  411.89  4992.4  408.12    4993  407.32    5003  407.32
  5003.7  408.12  5010.7  411.55  5020.2   414.3  5025.8  411.94  5042.4  414.56
    5048  413.73  5070.2  415.23  5226.3  413.76  5336.9  413.51  5386.3  414.21
  5418.5  413.38  5571.2  415.21  5690.7  417.63  5815.8  423.36  5996.5  427.88
#Mann= 3 ,-1 , 0
  4423.5      .1       0  4992.4     .07       0  5003.7      .1       0
Bank Sta=4992.4,5003.7
XS Rating Curve= 0 ,0
Exp/Cntr=0.3,0.1

Type RM Length L Ch R = 1 ,4244    ,689,689,689
BEGIN DESCRIPTION:
UNT 042 in RCW 5.0
END DESCRIPTION:
XS GIS Cut Line= 3
      2033680.89     13454588.66      2033510.75     13454227.55
      2033024.98     13453339.29
#Sta/Elev= 30
    4466  430.73  4580.2  427.39  4631.3  424.45  4908.2  415.76    4930  415.64
  4951.8  414.08    4968  414.42  4973.7  412.91  4982.1   413.7  4989.8  407.43
  4990.5  406.63  5000.5  406.63  5001.1  407.43  5017.3  412.93  5071.4  414.57
  5232.8  413.63  5278.1  412.46  5327.5  413.29  5343.6  412.44  5365.4  413.46
  5415.2   413.9  5452.7  412.37  5460.8  413.33  5556.1  414.07  5659.5  416.14
  5724.9  418.55  5757.1  417.88  5791.3  426.13  5850.1  427.13  5877.6  426.67
#Mann= 3 ,-1 , 0
    4466      .1       0  4989.8     .07       0  5001.1      .1       0
Bank Sta=4989.8,5001.1
XS Rating Curve= 0 ,0
Exp/Cntr=0.3,0.1

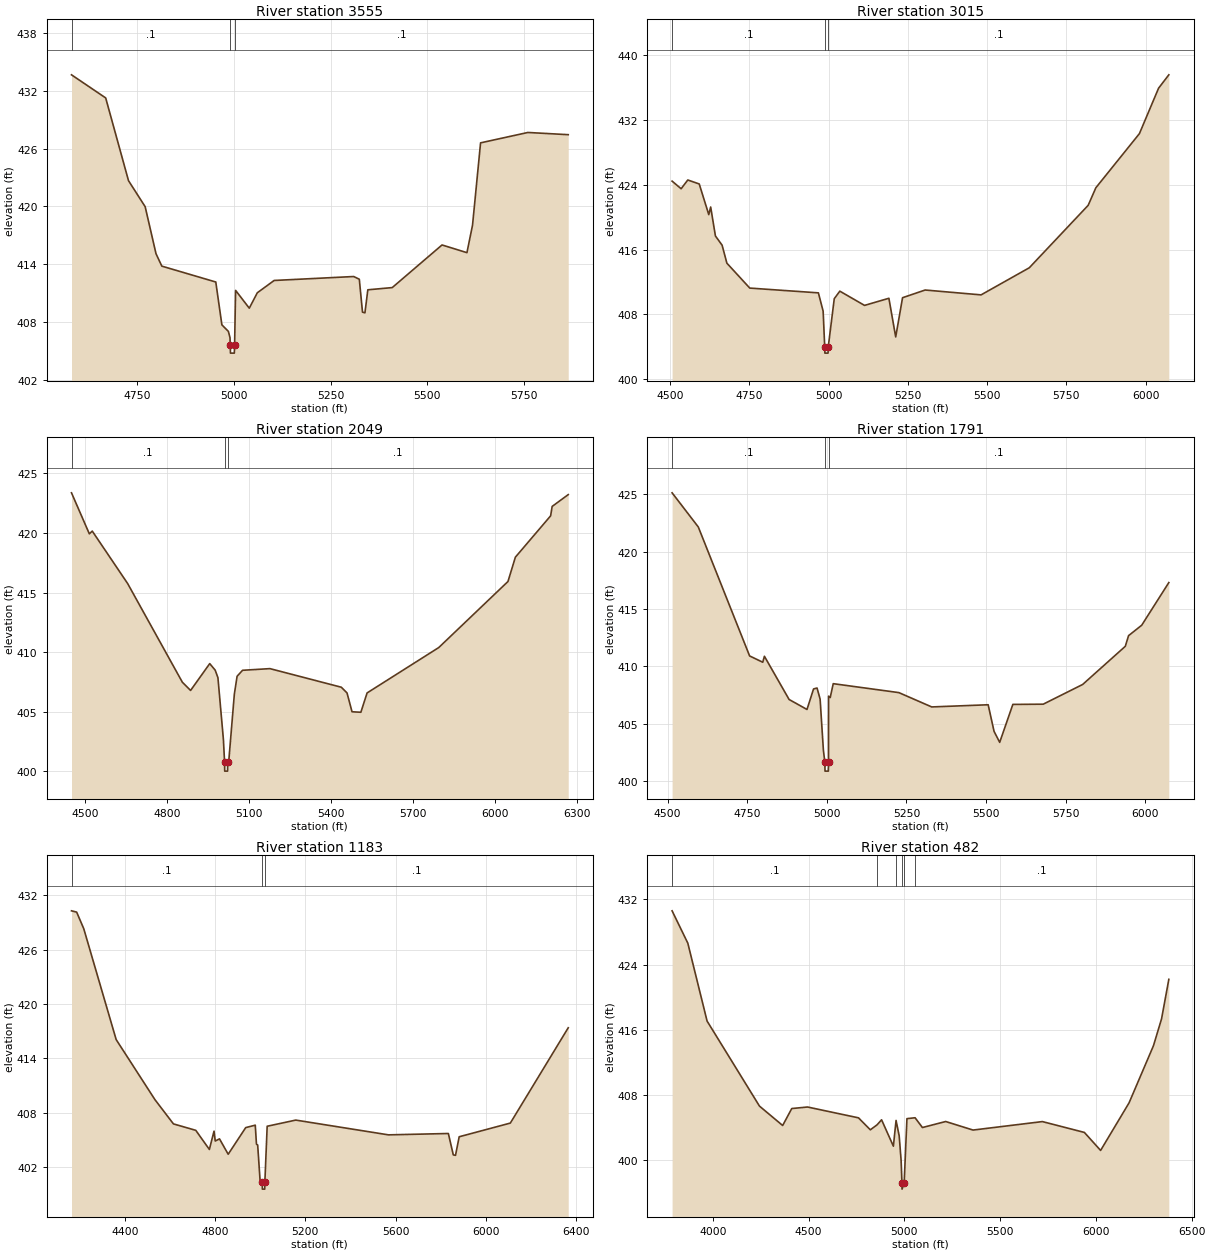
Type RM Length L Ch R = 1 ,3555    ,540,540,540
BEGIN DESCRIPTION:
UNT 042 in RCW 4.0
END DESCRIPTION:
XS GIS Cut Line= 3
      2034174.99     13453874.99        2033825.       13453675.
      2033121.84     13453140.73
#Sta/Elev= 30
  4579.3  433.68  4667.8  431.28  4726.9  422.68    4770  419.98  4798.1  415.09
  4813.2   413.8  4952.9  412.15  4968.7   407.7  4985.5  407.02  4989.7  406.37
  4990.3  405.56  4990.9  404.76  5000.9  404.76  5001.6  405.56  5004.2  411.28
  5039.6  409.43  5060.4  411.03    5104  412.31    5310  412.72  5324.5  412.44
  5332.8  409.02  5339.1  408.95  5346.6  411.34  5409.8  411.57  5538.7     416
  5603.2   415.2  5617.7  418.06  5638.5  426.61  5761.1  427.69  5865.5  427.46
#Mann= 3 ,-1 , 0
  4579.3      .1       0  4990.3     .07       0  5001.6      .1       0
Bank Sta=4990.3,5001.6
XS Rating Curve= 0 ,0
Exp/Cntr=0.3,0.1

Type RM Length L Ch R = 1 ,3015    ,966,966,966
BEGIN DESCRIPTION:
UNT 042 in RCW 3.0
END DESCRIPTION:
XS GIS Cut Line= 3
      2034396.18     13453783.13        2034125.       13453375.
      2033725.02     13452375.04
#Sta/Elev= 30
  4506.4  424.47  4534.9  423.53  4555.9  424.61    4592  424.12  4622.1  420.33
  4628.1  421.27  4643.1  417.69  4664.2  416.55  4679.2  414.33  4751.4  411.25
  4967.9  410.66  4982.9  408.39  4987.8  404.01  4988.4  403.21  4998.4  403.21
  4999.1  404.01    5018  409.94  5035.5  410.87  5113.5  409.11  5190.3  409.99
  5211.8  405.21  5233.4  410.06  5304.7  411.01  5481.1  410.41  5633.2  413.76
    5819  421.48  5843.2  423.65  5980.6  430.34  6041.1  435.96  6073.4  437.61
#Mann= 3 ,-1 , 0
  4506.4      .1       0  4987.8     .07       0  4999.1      .1       0
Bank Sta=4987.8,4999.1
XS Rating Curve= 0 ,0
Exp/Cntr=0.3,0.1

Type RM Length L Ch R = 1 ,2049    ,258,258,258
BEGIN DESCRIPTION:
UNT 042 in RCW 2.0
END DESCRIPTION:
XS GIS Cut Line= 3
      2034617.52      13453730.2      2034643.57     13452979.29
      2034322.37     13451963.63
#Sta/Elev= 30
  4449.8  423.37    4515  419.93  4525.7  420.16  4655.1  415.76  4855.2  407.48
  4885.3  406.79  4955.3  409.04  4975.3  408.49  4985.3  407.86  5005.3  402.68
  5009.5  400.82  5010.1  400.02  5020.6  400.02  5021.1  400.82  5025.3  400.95
  5045.4  406.49  5055.4  407.98  5075.4  408.48  5175.4  408.62  5436.4  407.06
  5457.4  406.58  5475.7     405    5508  404.96  5530.8  406.58    5793  410.39
    6046  415.93  6073.1  417.97    6202  421.44  6207.6  422.23  6266.4  423.22
#Mann= 3 ,-1 , 0
  4449.8      .1       0  5009.5     .07       0  5021.1      .1       0
Bank Sta=5009.5,5021.1
XS Rating Curve= 0 ,0
Exp/Cntr=0.3,0.1

Type RM Length L Ch R = 1 ,1791    ,608,608,608
BEGIN DESCRIPTION:
Mapping XS c91b653b
END DESCRIPTION:
XS GIS Cut Line= 3
      2034787.68     13453618.83      2034891.83     13453407.07
      2034572.39     13452122.37
#Sta/Elev= 30
  4514.1  425.13  4596.4  422.15  4757.5   410.9  4798.8  410.35    4804  410.87
  4881.5   407.1  4937.7  406.23  4958.3  408.02  4969.3   408.1  4978.9  407.13
  4989.2  402.67  4993.7  401.65  4994.3  400.85  5004.8  400.85  5005.3  401.65
  5005.5  407.39  5010.6  407.27  5020.1  408.48  5226.2   407.7  5329.3  406.45
  5506.6  406.64  5525.1  404.32  5542.8  403.36  5584.1  406.67  5679.6  406.69
  5803.3  408.41  5937.2  411.74  5947.5  412.67  5988.8  413.58  6073.9   417.3
#Mann= 3 ,-1 , 0
  4514.1      .1       0  4993.7     .07       0  5005.3      .1       0
Bank Sta=4993.7,5005.3
XS Rating Curve= 0 ,0
Exp/Cntr=0.3,0.1

Type RM Length L Ch R = 1 ,1183    ,701,701,701
BEGIN DESCRIPTION:
Mapping XS c2c404fc
END DESCRIPTION:
XS GIS Cut Line= 3
      2034724.23     13453784.33      2035292.79     13453523.92
      2034784.19     13452032.08
#Sta/Elev= 30
    4164   430.3  4186.8  430.16  4218.4  428.32  4361.9  416.09    4534  409.45
  4615.8  406.78  4714.8  406.07    4775  403.96  4795.7  405.98    4801  404.89
  4819.9  405.13  4858.4  403.43  4936.1  406.37  4978.4  406.64  4983.8  404.53
  4989.1  404.46  4999.5  400.62  5009.3  400.38  5009.9  399.58  5020.4  399.58
    5021  400.38  5031.2  406.52    5158   407.2  5568.7  405.57  5834.2  405.72
  5856.1  403.36  5865.9  403.31  5882.2  405.36  6108.9  406.87  6365.5  417.39
#Mann= 3 ,-1 , 0
    4164      .1       0  5009.3     .07       0    5021      .1       0
Bank Sta=5009.3,5021
XS Rating Curve= 0 ,0
Exp/Cntr=0.3,0.1

Type RM Length L Ch R = 1 ,482     ,0,0,0
BEGIN DESCRIPTION:
UNT 042 in RCW 1.0
END DESCRIPTION:
XS GIS Cut Line= 4
      2034724.18     13453801.71      2035513.98     13453470.67
      2035651.13     13452560.95       2035069.8     13451986.56
#Sta/Elev= 30
  3787.2   430.6  3869.3  426.63  3969.9  417.07  4243.5  406.63  4364.5  404.25
    4412  406.33  4494.2  406.52  4760.5  405.19  4822.2  403.72  4857.3  404.33
    4881  404.95  4942.6  401.71  4956.6  404.87  4972.9  402.98    4983  399.96
  4987.3  397.24  4987.9  396.44    4999  397.24  5013.4  405.09  5055.8   405.2
  5094.3     404  5215.6  404.74  5358.5  403.69  5720.6  404.73  5939.8   403.4
  6024.6  401.19  6173.2  407.03  6300.5  414.04  6342.9  417.35  6380.8  422.19
#Mann= 6 ,-1 , 0
  3787.2      .1       0  4857.3     .12       0  4956.6     .07       0
  4987.3     .07       0    4999     .07       0  5055.8      .1       0
Bank Sta=4987.3,4999
XS Rating Curve= 0 ,0
Exp/Cntr=0.3,0.1
LCMann Table=0

Chan Stop Cuts=-1
Use User Specified Reach Order=0
Composite Channel Slope=5