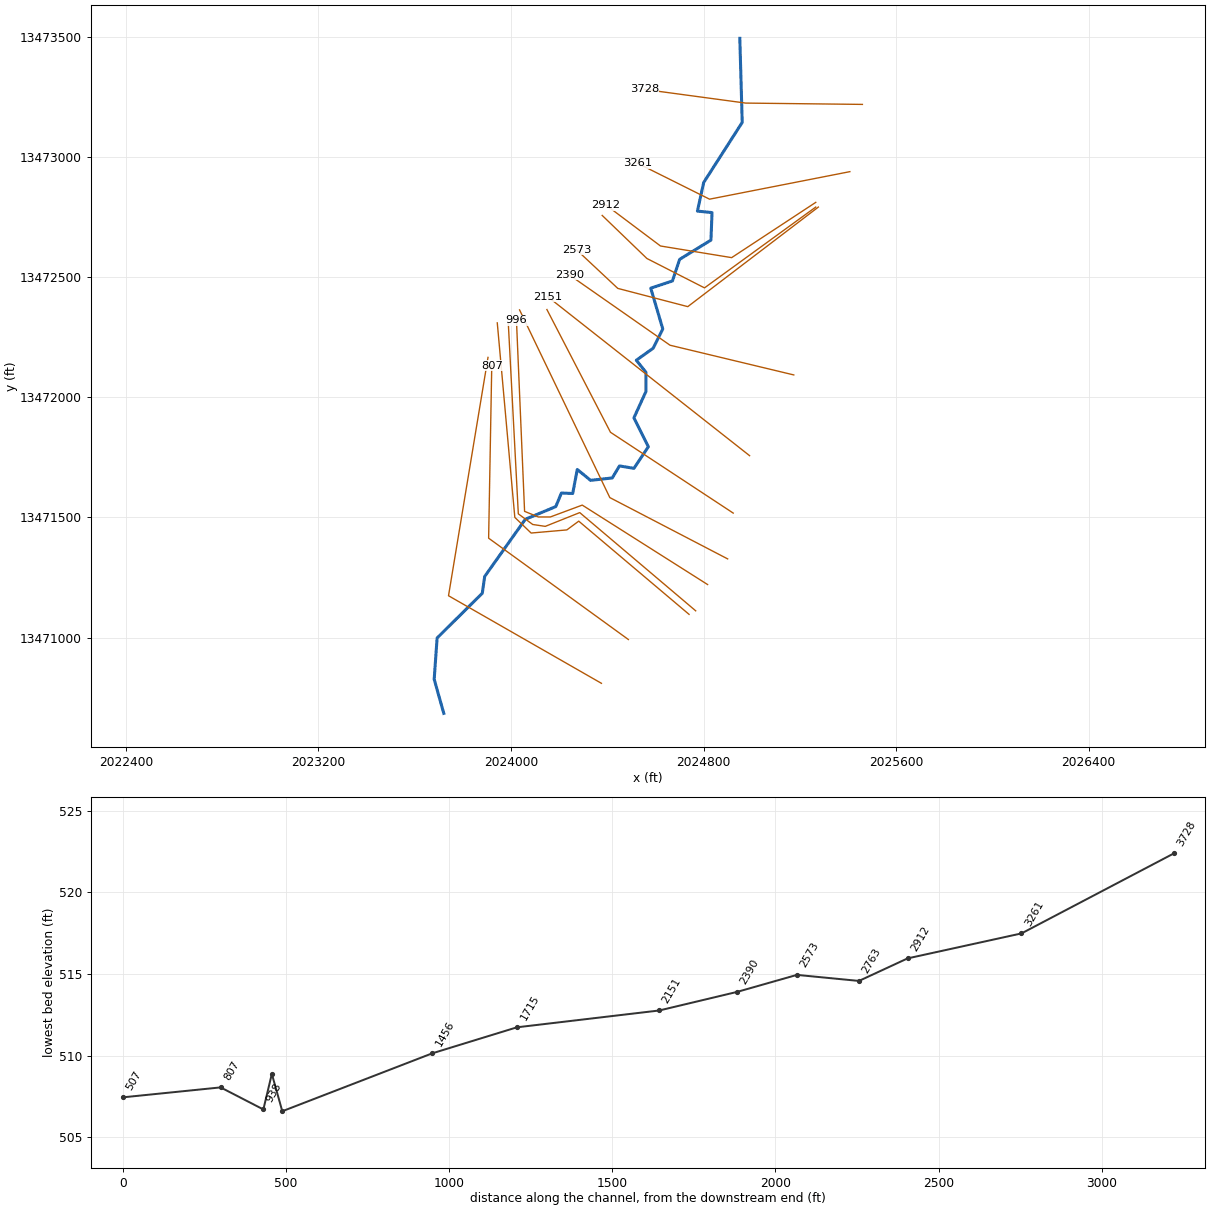
--- UNT 043 in RCW.prj (project) ---

Proj Title=UNT 043 in RCW Base Level Engineering
Current Plan=p01
Default Exp/Contr=0.3,0.1
English Units
Geom File=g01
Flow File=f01
Plan File=p01
BEGIN DESCRIPTION:
UNT 043 in RCW
END DESCRIPTION:

--- UNT 043 in RCW.p01 (plan) ---

Plan Title=Multiple Run
Short Identifier=Multiple
Geom File=g01
Flow File=f01
Subcritical Flow
K Sum by GR= 0
Std Step Tol= 0.01
Critical Tol= 0.01
Num of Std Step Trials= 20
Max Error Tol= 0.3
Flow Tol Ratio= 0.001
Split Flow NTrial= 30
Split Flow Tol= 0.02
Split Flow Ratio= 0.02
Log Output Level= 0
Friction Slope Method= 1
Unsteady Friction Slope Method= 2
Unsteady Bridges Friction Slope Method= 1
Parabolic Critical Depth
Global Vel Dist=  1 , 1 , 1
Global Log Level= 0
CheckData=True
Encroach Param= -1, 0, 0, 0
BEGIN DESCRIPTION:
Multiple Run
END DESCRIPTION:

--- UNT 043 in RCW.f01 (steady flow) ---

Flow Title=Multiple
Number of Profiles=7
Profile Names=10-year,25-year,50-year,1pct_min,100-year,1pct_plu,500-year
River Rch & RM= UNT 043 in RCW,Reach-1,3728
     156     209     252     151     302     602     441
River Rch & RM= UNT 043 in RCW,Reach-1,1715
     193     262     318     193     384     767     570
Boundary for River Rch & Prof#=UNT 043 in RCW,Reach-1,1
Up Type=0
Dn Type=3
Dn Slope=0.005
Boundary for River Rch & Prof#=UNT 043 in RCW,Reach-1,2
Up Type=0
Dn Type=3
Dn Slope=0.005
Boundary for River Rch & Prof#=UNT 043 in RCW,Reach-1,3
Up Type=0
Dn Type=3
Dn Slope=0.005
Boundary for River Rch & Prof#=UNT 043 in RCW,Reach-1,4
Up Type=0
Dn Type=3
Dn Slope=0.005
Boundary for River Rch & Prof#=UNT 043 in RCW,Reach-1,5
Up Type=0
Dn Type=3
Dn Slope=0.005
Boundary for River Rch & Prof#=UNT 043 in RCW,Reach-1,6
Up Type=0
Dn Type=3
Dn Slope=0.005
Boundary for River Rch & Prof#=UNT 043 in RCW,Reach-1,7
Up Type=0
Dn Type=3
Dn Slope=0.005

--- UNT 043 in RCW.g01 (geometry) ---

Geom Title=Existing Conditions

River Reach=UNT 043 in RCW,Reach-1
Reach XY= 30
      2024950.80     13473494.54      2024960.80     13473144.54
      2024800.80     13472894.54      2024774.66     13472775.30
      2024835.42     13472769.22      2024830.80     13472654.54
      2024700.80     13472574.54      2024670.80     13472484.54
      2024580.80     13472454.54      2024630.80     13472284.54
      2024590.80     13472204.54      2024520.80     13472154.54
      2024560.80     13472104.54      2024560.80     13472024.54
      2024510.80     13471914.54      2024570.80     13471794.54
      2024510.80     13471704.54      2024450.80     13471714.54
      2024420.80     13471664.54      2024330.80     13471654.54
      2024275.53     13471699.78      2024256.43     13471599.95
      2024209.56     13471601.69      2024186.12     13471545.26
      2024059.38     13471492.31      2023890.80     13471254.54
      2023880.80     13471184.54      2023693.06     13470998.39
      2023680.91     13470826.51      2023720.80     13470684.54

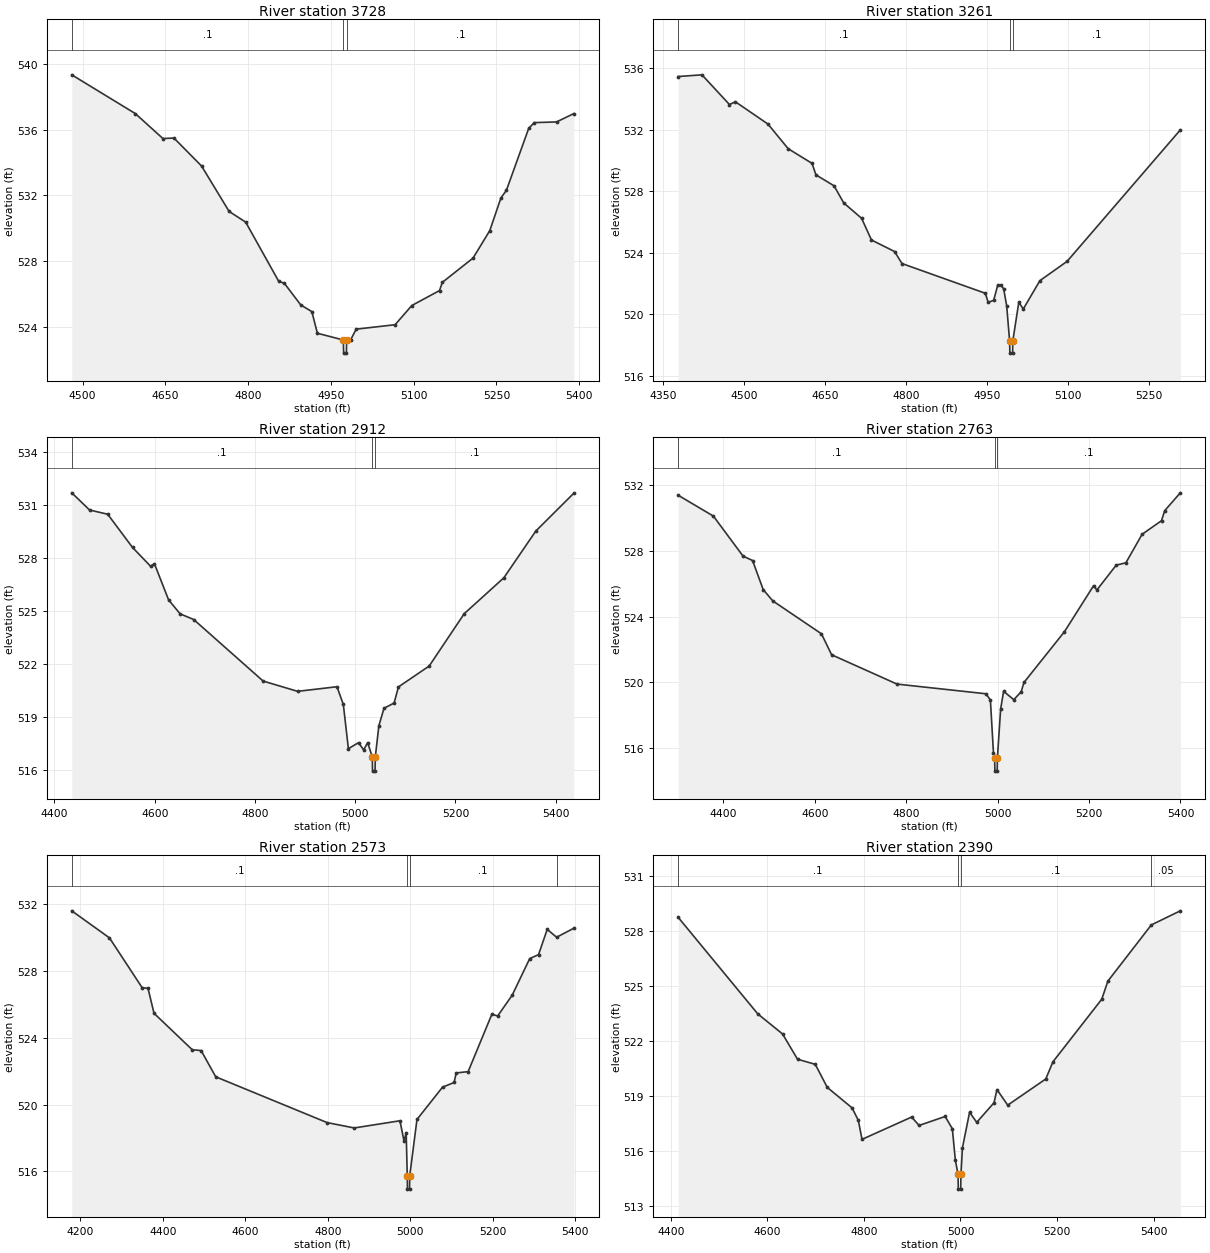
Type RM Length L Ch R = 1,3728,467,467,467
BEGIN DESCRIPTION:
UNT 043 in RCW 4.0
END DESCRIPTION:
XS GIS Cut Line= 3
      2025460.16     13473219.52      2024975.00     13473225.00
      2024553.93     13473282.02
#Sta/Elev= 30
  4480.3  539.33  4595.5  536.97  4645.5  535.45  4665.5  535.48  4715.5  533.78
  4765.5  531.01  4795.5  530.36  4855.5  526.75  4865.5  526.64  4895.5  525.31
  4915.5  524.91  4925.5  523.59  4972.6  523.18  4973.1  522.38  4978.1  522.38
  4978.6  523.18  4985.7  523.18  4995.8  523.84  5066.4  524.11  5096.7  525.28
  5146.9  526.19  5152.0  526.69  5207.7  528.17  5238.0  529.84  5258.1  531.82
  5268.2  532.30  5308.6  536.07  5318.7  536.42  5359.0  536.46  5390.4  536.97
#Mann=3,-1,0
  4480.3     0.1       0  4972.6    0.07       0  4978.6     0.1       0
Bank Sta=4972.6,4978.6
Exp/Cntr=0.3,0.1

Type RM Length L Ch R = 1,3261,349,349,349
BEGIN DESCRIPTION:
UNT 043 in RCW 3.0
END DESCRIPTION:
XS GIS Cut Line= 3
      2025408.09     13472939.57      2024825.00     13472825.00
      2024524.96     13472975.02
#Sta/Elev= 30
  4378.7  535.45  4422.6  535.56  4473.6  533.63  4484.5  533.81  4544.9  532.36
  4582.3  530.76  4626.4  529.81  4633.7  529.06  4667.2  528.35  4685.1  527.24
  4718.2  526.24  4736.5  524.83  4779.3  524.08  4793.0  523.30  4947.2  521.37
  4952.6  520.78  4962.8  520.91  4970.4  521.91  4975.7  521.91  4981.3  521.66
  4986.9  520.55  4992.3  518.28  4992.8  517.48  4997.8  517.48  4998.3  518.28
  5009.3  520.78  5017.7  520.35  5048.4  522.19  5098.7  523.44  5308.4  531.98
#Mann=3,-1,0
  4378.7     0.1       0  4992.3    0.07       0  4998.3     0.1       0
Bank Sta=4992.3,4998.3
Exp/Cntr=0.3,0.1

Type RM Length L Ch R = 1,2912,149,149,149
BEGIN DESCRIPTION:
Mapping XS 22ec880c
END DESCRIPTION:
XS GIS Cut Line= 4
      2025266.34     13472811.72      2024916.91     13472581.66
      2024621.22     13472630.13      2024394.36     13472800.81
#Sta/Elev= 30
  4434.5  531.68  4470.0  530.71  4506.2  530.47  4555.8  528.59  4591.8  527.53
  4599.5  527.67  4627.7  525.63  4650.7  524.84  4677.8  524.52  4816.4  521.04
  4885.2  520.46  4963.7  520.72  4976.4  519.72  4986.5  517.22  5006.8  517.56
  5016.9  517.15  5025.0  517.56  5034.2  516.75  5034.7  515.95  5039.7  515.95
  5040.2  516.75  5047.3  518.51  5057.5  519.50  5077.7  519.80  5086.4  520.71
  5147.7  521.89  5217.7  524.85  5296.8  526.88  5360.5  529.52  5436.4  531.66
#Mann=3,-1,0
  4434.5     0.1       0  5034.2    0.07       0  5040.2     0.1       0
Bank Sta=5034.2,5040.2
Exp/Cntr=0.3,0.1

Type RM Length L Ch R = 1,2763,190,190,190
BEGIN DESCRIPTION:
Mapping XS 489df02e
END DESCRIPTION:
XS GIS Cut Line= 4
      2025266.33     13472792.18      2024804.07     13472455.79
      2024564.79     13472578.04      2024379.08     13472757.28
#Sta/Elev= 30
  4301.1  531.40  4378.0  530.13  4442.9  527.69  4463.7  527.42  4486.9  525.65
  4507.8  524.96  4614.4  522.95  4636.7  521.67  4779.8  519.88  4974.2  519.29
  4984.1  518.91  4990.8  515.68  4993.4  515.37  4993.9  514.57  4998.9  514.57
  4999.4  515.37  5006.5  518.36  5013.0  519.44  5035.2  518.93  5051.4  519.41
  5057.5  519.98  5146.2  523.08  5210.0  525.89  5217.0  525.62  5259.4  527.14
  5280.5  527.28  5316.0  529.02  5358.5  529.85  5365.4  530.46  5399.6  531.55
#Mann=3,-1,0
  4301.1     0.1       0  4993.4    0.07       0  4999.4     0.1       0
Bank Sta=4993.4,4999.4
Exp/Cntr=0.3,0.1

Type RM Length L Ch R = 1,2573,183,183,183
BEGIN DESCRIPTION:
UNT 043 in RCW 2.0
END DESCRIPTION:
XS GIS Cut Line= 4
      2025277.18     13472792.18      2024734.62     13472377.66
      2024443.82     13472453.62      2024272.70     13472614.04
#Sta/Elev= 30
  4178.9  531.59  4270.4  529.97  4349.4  527.00  4363.9  526.95  4378.4  525.46
  4471.1  523.28  4492.7  523.23  4528.1  521.66  4798.3  518.92  4864.1  518.60
  4975.0  519.03  4984.9  517.81  4990.1  518.32  4992.7  515.74  4993.2  514.94
  4998.2  514.94  4998.7  515.74  5016.3  519.11  5078.3  521.04  5106.3  521.32
  5111.4  521.89  5140.4  521.97  5197.9  525.40  5212.0  525.30  5247.2  526.54
  5289.7  528.73  5311.2  528.97  5332.2  530.48  5355.0  530.01  5396.8  530.55
#Mann=4,-1,0
  4178.9     0.1       0  4992.7    0.07       0  4998.7     0.1       0
  5355.0    0.05       0
Bank Sta=4992.7,4998.7
Exp/Cntr=0.3,0.1

Type RM Length L Ch R = 1,2390,239,239,239
BEGIN DESCRIPTION:
Mapping XS 9453003f
END DESCRIPTION:
XS GIS Cut Line= 3
      2025175.12     13472093.38      2024660.84     13472217.07
      2024242.06     13472510.00
#Sta/Elev= 30
  4415.4  528.75  4580.1  523.48  4631.5  522.38  4662.5  521.00  4699.3  520.72
  4724.1  519.46  4775.5  518.34  4788.4  517.66  4796.1  516.62  4898.9  517.84
  4914.2  517.38  4968.3  517.87  4983.2  517.20  4989.3  515.51  4995.0  514.70
  4995.5  513.90  5000.5  513.90  5001.0  514.70  5004.1  516.16  5018.9  518.10
  5033.7  517.55  5069.5  518.62  5075.6  519.34  5097.9  518.49  5176.7  519.92
  5191.6  520.86  5292.7  524.28  5305.4  525.27  5395.4  528.34  5455.4  529.11
#Mann=4,-1,0
  4415.4     0.1       0  4995.0    0.07       0  5001.0     0.1       0
  5395.4    0.05       0
Bank Sta=4995,5001
Exp/Cntr=0.3,0.1

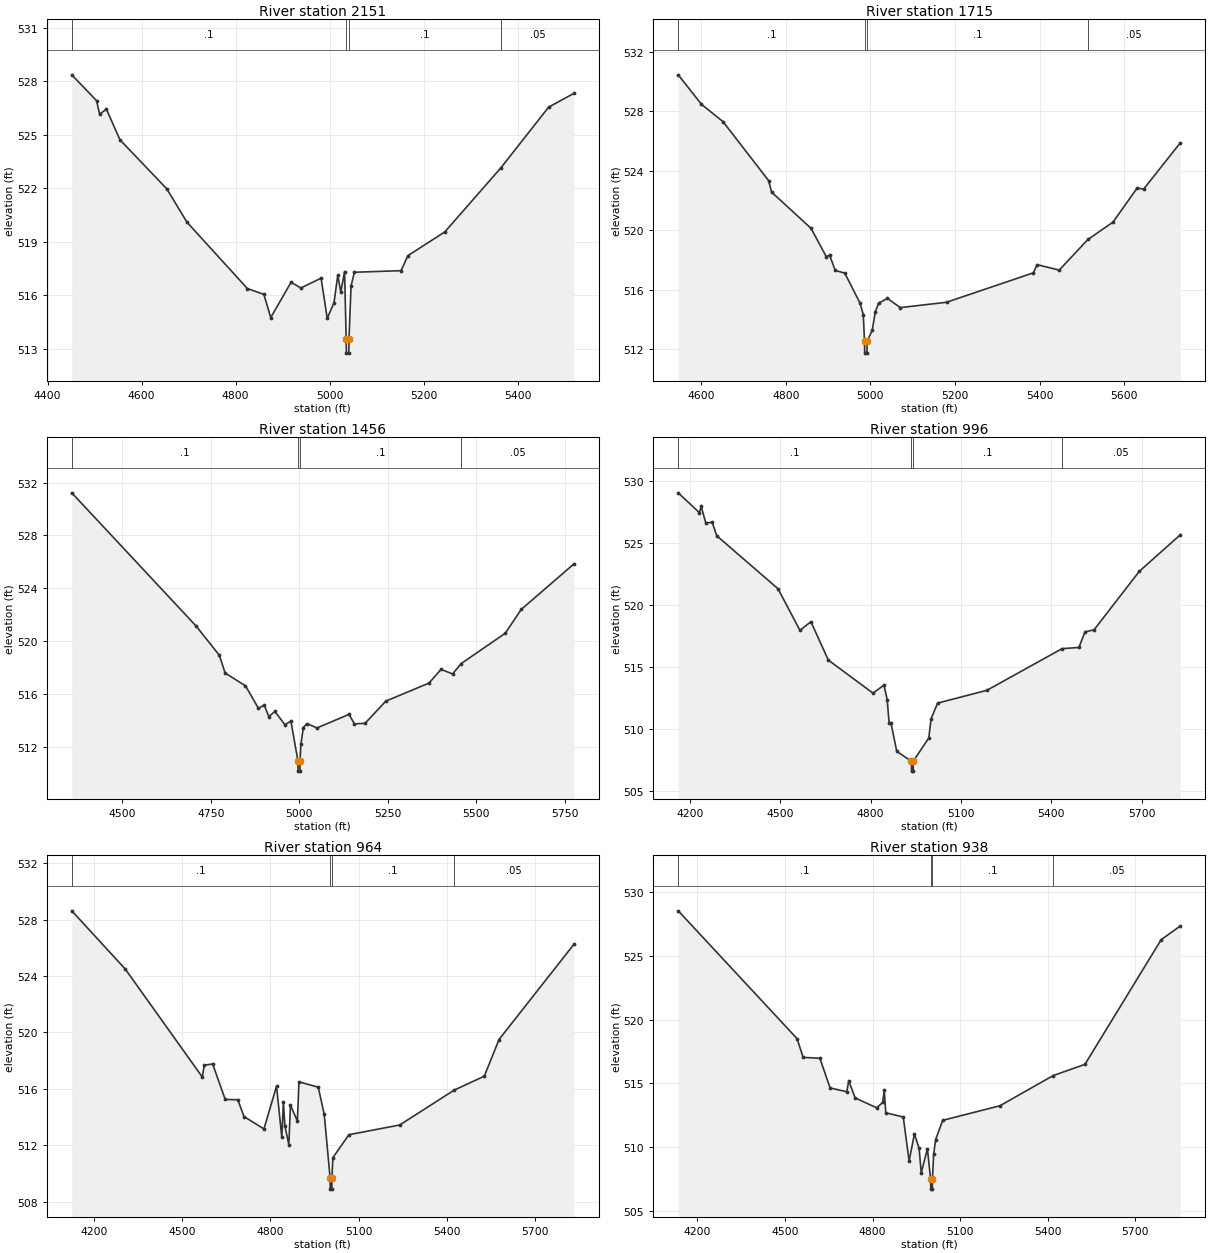
Type RM Length L Ch R = 1,2151,436,436,436
BEGIN DESCRIPTION:
Mapping XS e423e702
END DESCRIPTION:
XS GIS Cut Line= 2
      2024991.44     13471757.28      2024152.92     13472418.72
#Sta/Elev= 30
  4451.5  528.35  4504.3  526.90  4510.7  526.14  4525.1  526.43  4554.0  524.71
  4653.4  521.97  4696.7  520.09  4825.0  516.38  4860.2  516.05  4874.7  514.75
  4918.0  516.73  4938.8  516.41  4981.9  516.96  4994.9  514.71  5009.3  515.58
  5017.4  517.14  5023.8  516.17  5031.8  517.33  5035.2  513.56  5035.7  512.76
  5040.7  512.76  5041.2  513.56  5045.6  516.52  5052.6  517.29  5152.0  517.38
  5166.5  518.22  5245.0  519.55  5364.6  523.15  5465.9  526.54  5519.5  527.31
#Mann=4,-1,0
  4451.5     0.1       0  5035.2    0.07       0  5041.2     0.1       0
  5364.6    0.05       0
Bank Sta=5035.2,5041.2
Exp/Cntr=0.3,0.1

Type RM Length L Ch R = 1,1715,259,259,259
BEGIN DESCRIPTION:
Mapping XS d508e93e
END DESCRIPTION:
XS GIS Cut Line= 3
      2024923.39     13471518.31      2024413.44     13471854.66
      2024149.34     13472365.55
#Sta/Elev= 30
  4546.1  530.44  4600.9  528.46  4652.0  527.29  4759.8  523.32  4766.5  522.56
  4859.8  520.12  4895.9  518.21  4903.5  518.32  4917.0  517.29  4939.5  517.11
  4975.4  515.10  4983.2  514.32  4986.1  512.53  4986.6  511.73  4991.8  511.73
  4992.3  512.53  5004.3  513.26  5011.4  514.49  5019.4  515.09  5040.4  515.41
  5070.6  514.79  5179.9  515.15  5385.2  517.13  5393.8  517.68  5446.0  517.31
  5513.8  519.37  5573.2  520.54  5630.2  522.83  5645.3  522.75  5732.1  525.87
#Mann=4,-1,0
  4546.1     0.1       0  4986.1    0.07       0  4992.3     0.1       0
  5513.8    0.05       0
Bank Sta=4986.1,4992.3
Exp/Cntr=0.3,0.1

Type RM Length L Ch R = 1,1456,460,460,460
BEGIN DESCRIPTION:
Mapping XS 702be5bb
END DESCRIPTION:
XS GIS Cut Line= 3
      2024900.32     13471327.58      2024410.71     13471582.80
      2024035.72     13472364.03
#Sta/Elev= 30
  4357.2  531.22  4707.9  521.15  4774.1  518.92  4790.6  517.57  4848.1  516.60
  4884.6  514.90  4901.1  515.14  4914.1  514.27  4931.2  514.66  4959.4  513.66
  4976.5  513.92  4996.1  510.94  4996.6  510.14  5001.8  510.14  5002.3  510.94
  5004.7  512.19  5011.6  513.44  5021.8  513.74  5050.0  513.41  5140.6  514.44
  5155.8  513.72  5185.9  513.76  5244.5  515.44  5366.6  516.81  5400.8  517.85
  5433.1  517.50  5457.7  518.29  5582.0  520.58  5627.3  522.39  5775.9  525.83
#Mann=4,-1,0
  4357.2     0.1       0  4996.1    0.07       0  5002.3     0.1       0
  5457.7    0.05       0
Bank Sta=4996.1,5002.3
Exp/Cntr=0.3,0.1

Type RM Length L Ch R = 1,996,32,32,32
BEGIN DESCRIPTION:
Mapping XS cef1fded
END DESCRIPTION:
XS GIS Cut Line= 6
      2024816.96     13471220.82      2024296.13     13471551.55
      2024163.31     13471502.08      2024113.83     13471502.08
      2024056.54     13471525.51      2024022.74     13472321.16
#Sta/Elev= 30
  4161.7  529.01  4232.0  527.41  4237.9  527.91  4253.2  526.58  4274.3  526.64
  4289.6  525.55  4492.9  521.28  4565.7  517.93  4602.1  518.63  4659.7  515.54
  4808.3  512.87  4844.5  513.52  4855.3  512.35  4861.7  510.46  4867.5  510.50
  4887.1  508.18  4935.6  507.39  4936.1  506.59  4941.4  506.59  4941.9  507.39
  4993.3  509.26  5001.1  510.82  5022.7  512.07  5186.2  513.10  5435.9  516.46
  5491.7  516.55  5511.8  517.81  5541.8  517.97  5691.9  522.68  5828.2  525.63
#Mann=4,-1,0
  4161.7     0.1       0  4935.6    0.07       0  4941.9     0.1       0
  5435.9    0.05       0
Bank Sta=4935.6,4941.9
Exp/Cntr=0.3,0.1

Type RM Length L Ch R = 1,964,26,26,26
BEGIN DESCRIPTION:
Mapping XS 174cdba7
END DESCRIPTION:
XS GIS Cut Line= 6
      2024767.46     13471111.47      2024285.71     13471520.30
      2024142.48     13471463.01      2024090.40     13471470.83
      2024030.50     13471515.10      2023988.84     13472309.32
#Sta/Elev= 30
  4123.8  528.62  4305.5  524.50  4568.1  516.83  4574.6  517.67  4603.2  517.76
  4646.0  515.24  4688.9  515.22  4709.7  514.03  4777.8  513.15  4820.6  516.18
  4838.6  512.55  4844.0  515.09  4848.9  513.39  4862.5  512.04  4868.0  514.84
  4891.5  513.71  4897.0  516.49  4962.6  516.11  4983.0  514.18  5002.9  509.68
  5003.4  508.88  5008.7  508.88  5009.2  509.68  5012.3  511.11  5067.0  512.74
  5239.9  513.43  5424.9  515.90  5527.7  516.89  5577.7  519.49  5832.4  526.24
#Mann=4,-1,0
  4123.8     0.1       0  5002.9    0.07       0  5009.2     0.1       0
  5424.9    0.05       0
Bank Sta=5002.9,5009.2
Exp/Cntr=0.3,0.1

Type RM Length L Ch R = 1,938,131,131,131
BEGIN DESCRIPTION:
Mapping XS a7d25170
END DESCRIPTION:
XS GIS Cut Line= 6
      2024739.93     13471096.69      2024281.59     13471484.71
      2024232.11     13471448.26      2024083.67     13471435.24
      2024015.96     13471500.34      2023943.05     13472310.16
#Sta/Elev= 30
  4135.0  528.54  4541.8  518.51  4562.6  517.04  4619.8  516.97  4654.9  514.64
  4712.1  514.34  4718.6  515.21  4740.5  513.86  4814.4  513.08  4834.8  513.50
  4840.3  514.47  4845.4  512.69  4905.3  512.36  4925.3  508.91  4943.5  511.03
  4959.6  509.89  4966.8  507.98  4987.9  509.87  4998.9  507.50  4999.4  506.70
  5004.7  506.70  5005.2  507.50  5009.3  509.42  5016.2  510.59  5040.4  512.10
  5236.1  513.24  5418.3  515.61  5527.2  516.49  5788.3  526.28  5853.7  527.35
#Mann=4,-1,0
  4135.0     0.1       0  4998.9    0.07       0  5005.2     0.1       0
  5418.3    0.05       0
Bank Sta=4998.9,5005.2
Exp/Cntr=0.3,0.1

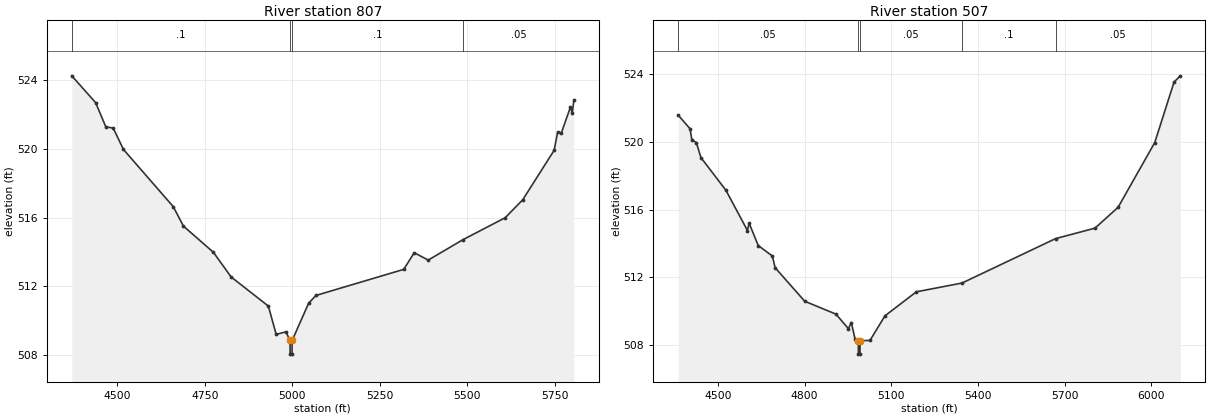
Type RM Length L Ch R = 1,807,300,300,300
BEGIN DESCRIPTION:
Mapping XS 24898d32
END DESCRIPTION:
XS GIS Cut Line= 3
      2024487.84     13470991.96      2023907.15     13471413.80
      2023920.14     13472131.24
#Sta/Elev= 30
  4369.9  524.27  4438.0  522.71  4467.4  521.29  4488.2  521.23  4517.6  519.98
  4659.8  516.65  4689.2  515.51  4775.0  513.98  4825.3  512.55  4931.9  510.85
  4954.3  509.20  4982.2  509.35  4993.7  508.85  4994.2  508.05  4999.5  508.05
  5000.0  508.85  5047.1  511.02  5068.0  511.47  5318.9  512.99  5348.9  513.96
  5388.9  513.53  5488.1  514.72  5608.9  516.00  5658.9  517.04  5748.9  519.93
  5758.9  520.99  5769.0  520.91  5795.6  522.46  5800.6  522.08  5805.2  522.85
#Mann=4,-1,0
  4369.9     0.1       0  4993.7    0.07       0  5000.0     0.1       0
  5488.1    0.05       0
Bank Sta=4993.7,5000
Exp/Cntr=0.3,0.1

Type RM Length L Ch R = 1,507,0,0,0
BEGIN DESCRIPTION:
UNT 043 in RCW 1.0
END DESCRIPTION:
XS GIS Cut Line= 3
      2024375.86     13470809.66      2023740.48     13471174.22
      2023904.54     13472166.41
#Sta/Elev= 30
  4362.7  521.59  4403.8  520.78  4409.8  520.12  4425.4  519.97  4441.2  519.08
  4527.5  517.15  4602.3  514.76  4608.0  515.20  4639.7  513.87  4688.6  513.25
  4698.0  512.56  4800.7  510.57  4908.6  509.81  4951.8  508.95  4961.8  509.31
  4974.7  508.35  4986.0  508.24  4986.5  507.44  4991.8  507.44  4992.3  508.24
  5026.5  508.25  5078.5  509.71  5187.2  511.13  5345.3  511.65  5669.0  514.28
  5805.5  514.90  5885.4  516.13  6012.5  519.97  6079.2  523.55  6100.9  523.92
#Mann=5,-1,0
  4362.7    0.05       0  4986.0    0.03       0  4992.3    0.05       0
  5345.3     0.1       0  5669.0    0.05       0
Bank Sta=4986,4992.3
Exp/Cntr=0.3,0.1

Chan Stop Cuts=-1