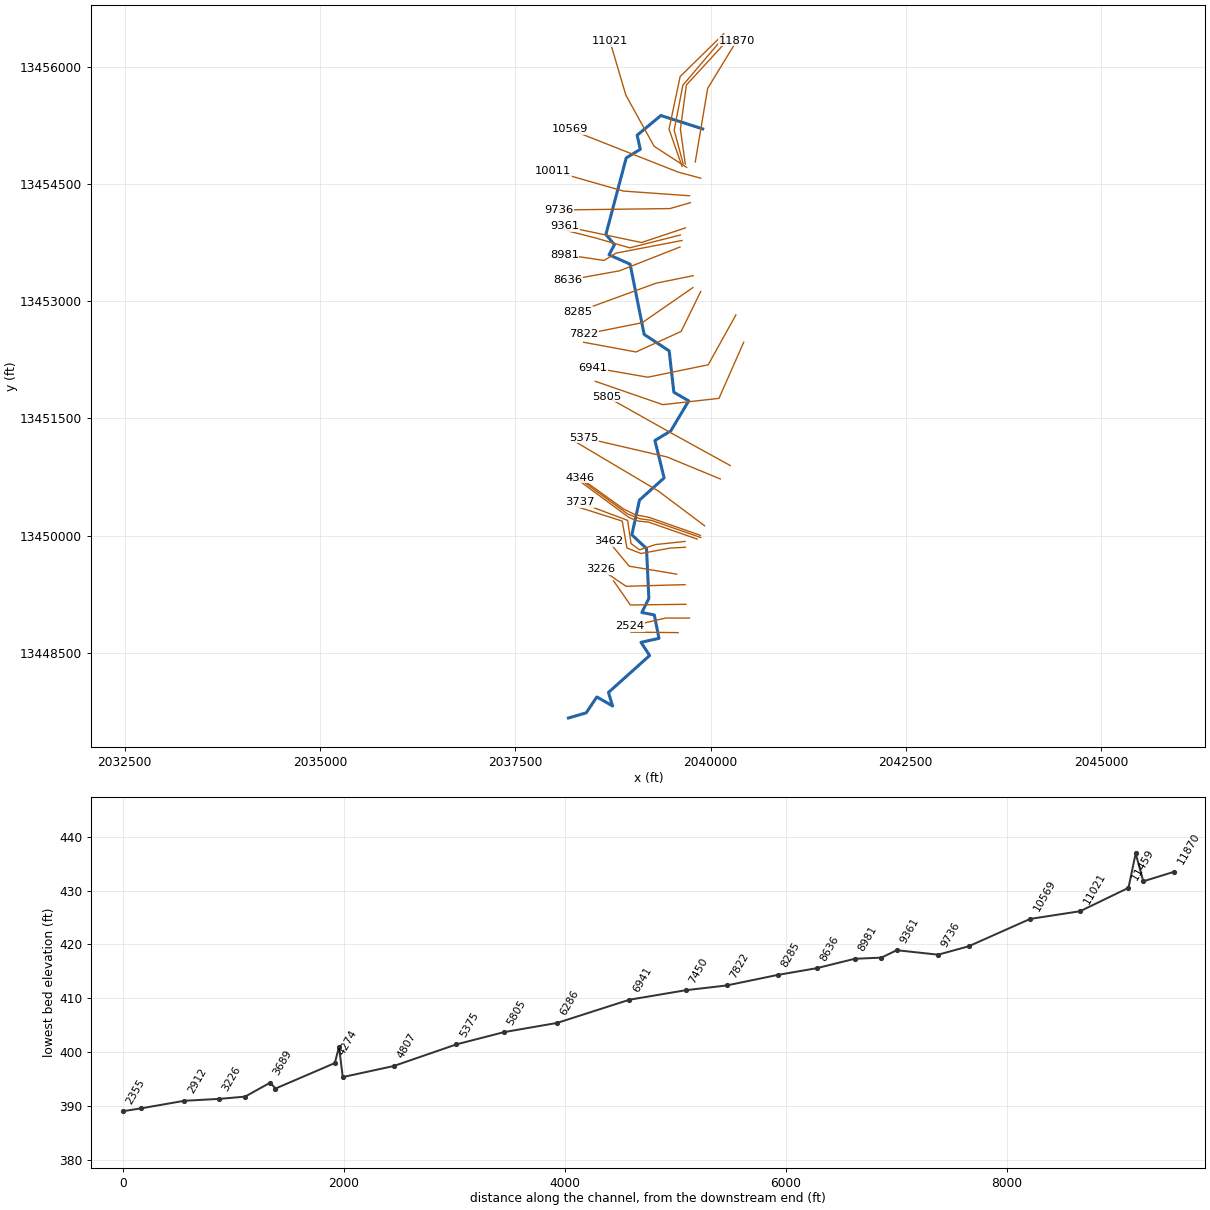
--- UNT 044 in RCW.prj (project) ---

Proj Title=UNT 044 in RCW Base Level Engineering
Current Plan=p01
Default Exp/Contr=0.3,0.1
English Units
Geom File=g01
Flow File=f01
Plan File=p01
BEGIN DESCRIPTION:
UNT 044 in RCW
END DESCRIPTION:

--- UNT 044 in RCW.p01 (plan) ---

Plan Title=Multiple Run
Short Identifier=Multiple
Geom File=g01
Flow File=f01
Subcritical Flow
K Sum by GR= 0
Std Step Tol= 0.01
Critical Tol= 0.01
Num of Std Step Trials= 20
Max Error Tol= 0.3
Flow Tol Ratio= 0.001
Split Flow NTrial= 30
Split Flow Tol= 0.02
Split Flow Ratio= 0.02
Log Output Level= 0
Friction Slope Method= 1
Unsteady Friction Slope Method= 2
Unsteady Bridges Friction Slope Method= 1
Parabolic Critical Depth
Global Vel Dist=  1 , 1 , 1
Global Log Level= 0
CheckData=True
Encroach Param= -1, 0, 0, 0
BEGIN DESCRIPTION:
Multiple Run
END DESCRIPTION:

--- UNT 044 in RCW.f01 (steady flow) ---

Flow Title=Multiple
Number of Profiles=7
Profile Names=10-year,25-year,50-year,1pct_min,100-year,1pct_plu,500-year
River Rch & RM= UNT 044 in RCW,Reach-1,11870
     160     217     264     160     320     638     476
River Rch & RM= UNT 044 in RCW,Reach-1,11593
     272     380     470     290     578    1153     888
River Rch & RM= UNT 044 in RCW,Reach-1,5805
     372     526     656     407     813    1621    1267
Boundary for River Rch & Prof#=UNT 044 in RCW,Reach-1,1
Up Type=0
Dn Type=3
Dn Slope=0.005
Boundary for River Rch & Prof#=UNT 044 in RCW,Reach-1,2
Up Type=0
Dn Type=3
Dn Slope=0.005
Boundary for River Rch & Prof#=UNT 044 in RCW,Reach-1,3
Up Type=0
Dn Type=3
Dn Slope=0.005
Boundary for River Rch & Prof#=UNT 044 in RCW,Reach-1,4
Up Type=0
Dn Type=3
Dn Slope=0.005
Boundary for River Rch & Prof#=UNT 044 in RCW,Reach-1,5
Up Type=0
Dn Type=3
Dn Slope=0.005
Boundary for River Rch & Prof#=UNT 044 in RCW,Reach-1,6
Up Type=0
Dn Type=3
Dn Slope=0.005
Boundary for River Rch & Prof#=UNT 044 in RCW,Reach-1,7
Up Type=0
Dn Type=3
Dn Slope=0.005

--- UNT 044 in RCW.g01 (geometry) ---

Geom Title=Existing Conditions

River Reach=UNT 044 in RCW,Reach-1
Reach XY= 30
      2039900.35     13455206.38      2039364.76     13455377.39
      2039060.76     13455125.22      2039100.80     13454944.54
      2038920.80     13454834.54      2038660.80     13453854.54
      2038770.80     13453724.54      2038700.80     13453594.54
      2038970.80     13453474.54      2039150.80     13452574.54
      2039470.80     13452364.54      2039530.80     13451834.54
      2039720.80     13451724.54      2039491.26     13451339.57
      2039288.48     13451217.35      2039406.15     13450738.18
      2039090.87     13450454.15      2038992.95     13450009.71
      2039180.80     13449834.54      2039210.80     13449194.54
      2039120.80     13449014.54      2039280.80     13448984.54
      2039340.80     13448684.54      2039110.32     13448633.32
      2039220.80     13448464.54      2038693.65     13447991.65
      2038746.43     13447818.73      2038545.04     13447934.01
      2038408.23     13447730.54      2038180.80     13447664.54

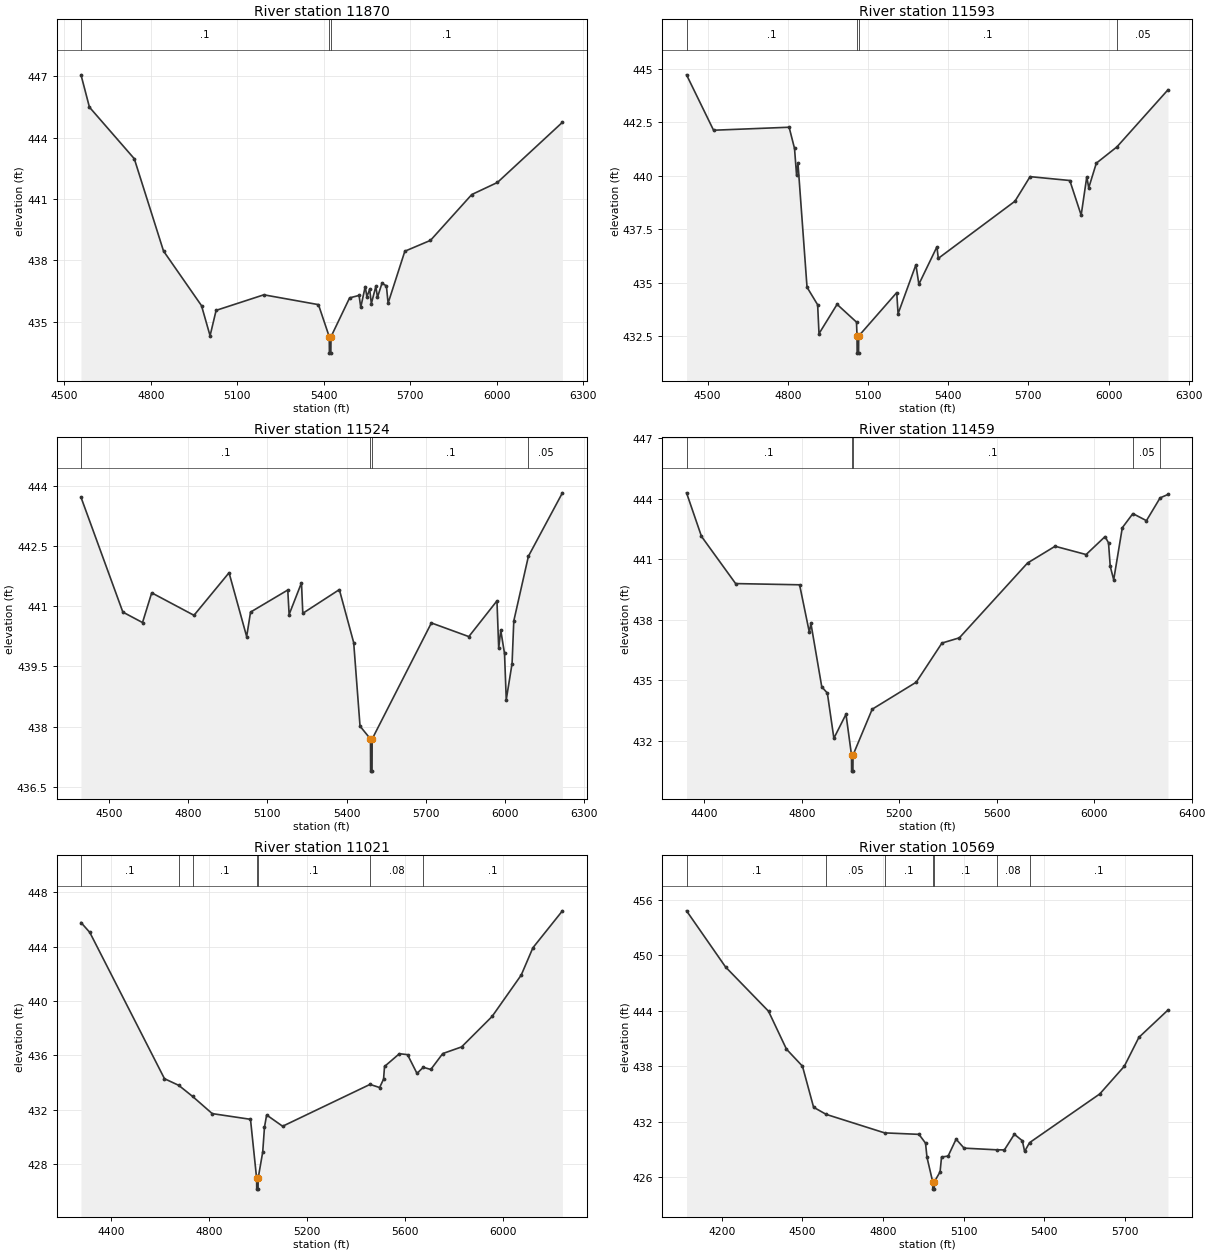
Type RM Length L Ch R = 1,11870,277,277,277
BEGIN DESCRIPTION:
UNT 044 in RCW 17.0
END DESCRIPTION:
XS GIS Cut Line= 3
      2039804.88     13454782.68      2039963.73     13455725.40
      2040336.15     13456334.81
#Sta/Elev= 30
  4558.1  447.07  4587.4  445.49  4743.0  442.97  4844.4  438.46  4976.2  435.79
  5005.9  434.32  5026.9  435.56  5192.5  436.32  5381.9  435.84  5419.4  434.27
  5419.9  433.47  5424.9  433.47  5425.4  434.27  5490.0  436.17  5522.8  436.29
  5528.7  435.71  5544.1  436.72  5550.0  436.23  5559.6  436.59  5565.4  435.89
  5580.9  436.73  5586.7  436.20  5602.2  436.88  5617.6  436.76  5623.5  435.91
  5681.6  438.45  5770.5  438.98  5913.8  441.22  6002.8  441.81  6228.3  444.75
#Mann=3,-1,0
  4558.1     0.1       0  5419.4    0.07       0  5425.4     0.1       0
Bank Sta=5419.4,5425.4
Exp/Cntr=0.3,0.1

Type RM Length L Ch R = 1,11593,69,69,69
BEGIN DESCRIPTION:
Mapping XS e6c134f3
END DESCRIPTION:
XS GIS Cut Line= 4
      2039677.27     13454754.92      2039614.77     13455202.84
      2039691.16     13455768.81      2040218.18     13456340.90
#Sta/Elev= 30
  4420.9  444.72  4522.0  442.13  4804.7  442.27  4824.9  441.28  4832.6  440.02
  4837.7  440.60  4871.7  434.79  4911.4  433.97  4916.5  432.62  4984.1  433.99
  5056.8  433.16  5058.7  432.51  5059.2  431.71  5064.5  431.71  5065.0  432.51
  5207.3  434.54  5212.3  433.55  5279.0  435.84  5290.1  434.93  5357.7  436.68
  5362.8  436.14  5649.5  438.81  5706.2  439.96  5854.8  439.78  5897.3  438.16
  5918.3  439.95  5925.7  439.44  5954.0  440.59  6031.0  441.35  6222.1  444.02
#Mann=4,-1,0
  4420.9     0.1       0  5058.7    0.07       0  5065.0     0.1       0
  6031.0    0.05       0
Bank Sta=5058.7,5065
Exp/Cntr=0.3,0.1

Type RM Length L Ch R = 1,11524,65,65,65
BEGIN DESCRIPTION:
Mapping XS 6890bb80
END DESCRIPTION:
XS GIS Cut Line= 4
      2039649.49     13454761.87      2039534.91     13455188.95
      2039646.02     13455765.34      2040159.89     13456369.47
#Sta/Elev= 30
  4395.0  443.71  4553.5  440.85  4627.9  440.59  4662.7  441.33  4822.7  440.77
  4955.4  441.83  5022.1  440.24  5036.8  440.85  5177.7  441.40  5182.8  440.79
  5229.6  441.58  5234.6  440.82  5372.9  441.41  5427.2  440.09  5451.2  438.01
  5490.8  437.69  5491.3  436.89  5496.6  436.89  5497.1  437.69  5721.3  440.58
  5863.0  440.24  5969.5  441.13  5976.1  439.95  5983.8  440.40  5998.1  439.82
  6004.7  438.67  6026.7  439.57  6033.2  440.63  6088.5  442.24  6217.3  443.82
#Mann=4,-1,0
  4395.0     0.1       0  5490.8    0.07       0  5497.1     0.1       0
  6088.5    0.05       0
Bank Sta=5490.8,5497.1
Exp/Cntr=0.3,0.1

Type RM Length L Ch R = 1,11459,438,438,438
BEGIN DESCRIPTION:
Mapping XS 0b558776
END DESCRIPTION:
XS GIS Cut Line= 4
      2039635.60     13454727.15      2039468.94     13455202.84
      2039611.30     13455876.45      2040170.13     13456424.86
#Sta/Elev= 30
  4327.3  444.30  4388.6  442.14  4528.7  439.80  4791.2  439.74  4831.3  437.38
  4837.6  437.83  4882.2  434.68  4905.1  434.37  4931.9  432.13  4981.6  433.32
  5004.2  431.30  5004.7  430.50  5010.0  430.50  5010.5  431.30  5089.1  433.57
  5269.8  434.91  5375.3  436.85  5446.8  437.11  5726.5  440.82  5839.6  441.65
  5966.9  441.24  6044.6  442.13  6058.8  441.82  6065.9  440.65  6080.1  439.99
  6115.4  442.57  6158.8  443.27  6214.4  442.92  6270.5  444.05  6302.8  444.22
#Mann=5,-1,0
  4327.3     0.1       0  5004.2    0.07       0  5010.5     0.1       0
  6158.8    0.05       0  6270.5     0.1       0
Bank Sta=5004.2,5010.5
Exp/Cntr=0.3,0.1

Type RM Length L Ch R = 1,11021,452,452,452
BEGIN DESCRIPTION:
Mapping XS adf56144
END DESCRIPTION:
XS GIS Cut Line= 4
      2039694.62     13454713.26      2039277.97     13454984.09
      2038916.86     13455636.86      2038712.18     13456330.67
#Sta/Elev= 30
  4276.8  445.79  4312.8  445.06  4617.8  434.29  4676.2  433.80  4732.3  432.99
  4812.8  431.72  4969.1  431.30  4994.1  426.96  4994.6  426.16  4999.9  426.16
  5000.4  426.96  5019.0  428.89  5026.2  430.72  5035.0  431.62  5100.3  430.79
  5457.2  433.87  5496.5  433.64  5512.6  434.26  5516.5  435.19  5577.2  436.13
  5610.5  436.06  5649.1  434.68  5674.8  435.13  5705.5  434.97  5754.2  436.14
  5831.2  436.63  5955.7  438.87  6074.8  441.92  6122.5  443.93  6243.1  446.65
#Mann=7,-1,0
  4276.8     0.1       0  4676.2    0.05       0  4732.3     0.1       0
  4994.1    0.07       0  5000.4     0.1       0  5457.2    0.08       0
  5674.8     0.1       0
Bank Sta=4994.1,5000.4
Exp/Cntr=0.3,0.1

Type RM Length L Ch R = 1,10569,558,558,558
BEGIN DESCRIPTION:
UNT 044 in RCW 16.0
END DESCRIPTION:
XS GIS Cut Line= 3
      2039875.00     13454575.00      2039580.92     13454655.09
      2038199.14     13455199.63
#Sta/Elev= 30
  4069.4  454.81  4214.5  448.74  4374.2  443.96  4440.9  439.86  4500.4  438.02
  4541.8  433.58  4588.6  432.81  4805.8  430.81  4933.6  430.65  4958.0  429.70
  4963.4  428.17  4984.5  425.53  4985.0  424.73  4990.4  424.73  4990.9  425.53
  5012.1  426.60  5017.5  428.20  5041.9  428.30  5071.6  430.13  5101.4  429.16
  5222.0  428.98  5251.2  428.97  5288.2  430.66  5318.0  429.96  5326.4  428.80
  5344.6  429.75  5605.9  435.02  5697.0  438.01  5751.2  441.13  5859.4  444.09
#Mann=7,-1,0
  4069.4     0.1       0  4588.6    0.05       0  4805.8     0.1       0
  4984.5    0.07       0  4990.9     0.1       0  5222.0    0.08       0
  5344.6     0.1       0
Bank Sta=4984.5,4990.9
Exp/Cntr=0.3,0.1

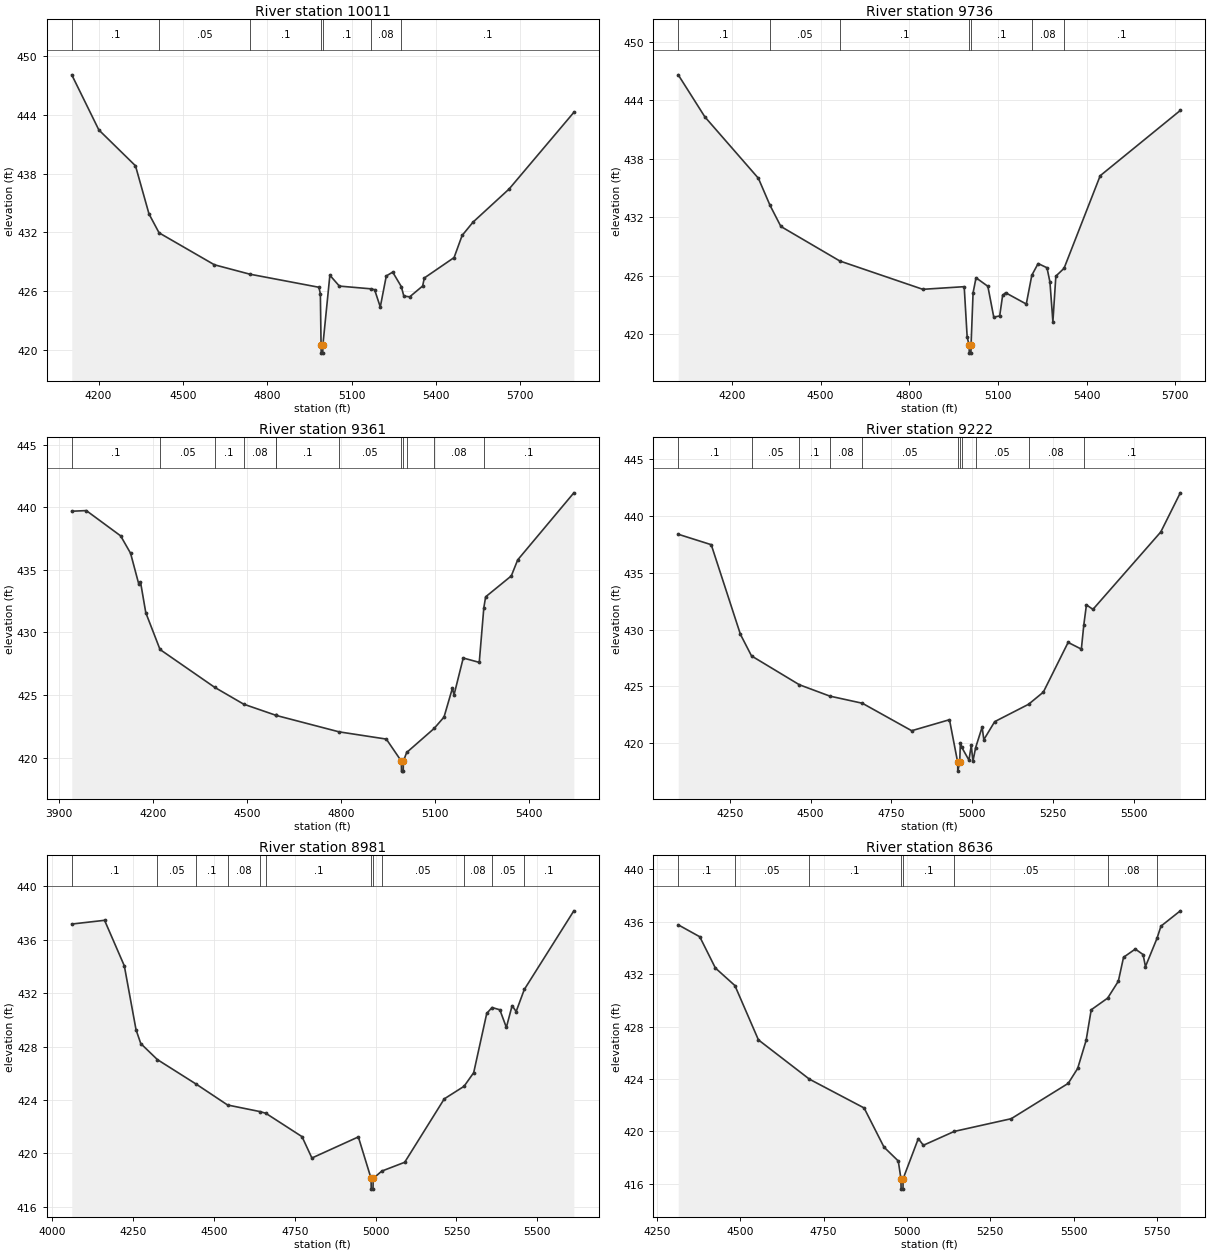
Type RM Length L Ch R = 1,10011,275,275,275
BEGIN DESCRIPTION:
UNT 044 in RCW 15.0
END DESCRIPTION:
XS GIS Cut Line= 3
      2039731.07     13454350.41      2038884.74     13454410.30
      2037983.75     13454668.10
#Sta/Elev= 30
  4104.5  448.12  4200.8  442.48  4331.1  438.81  4379.2  433.88  4415.0  431.95
  4611.8  428.68  4737.7  427.72  4983.4  426.38  4988.6  425.72  4991.1  420.44
  4991.6  419.64  4997.0  419.64  4997.5  420.44  5022.4  427.61  5056.2  426.50
  5168.4  426.22  5181.5  426.13  5201.7  424.36  5223.1  427.54  5245.9  427.93
  5276.4  426.45  5285.5  425.48  5306.3  425.40  5352.4  426.51  5358.3  427.33
  5464.2  429.42  5492.7  431.68  5531.7  433.05  5660.0  436.44  5890.1  444.28
#Mann=7,-1,0
  4104.5     0.1       0  4415.0    0.05       0  4737.7     0.1       0
  4991.1    0.07       0  4997.5     0.1       0  5168.4    0.08       0
  5276.4     0.1       0
Bank Sta=4991.1,4997.5
Exp/Cntr=0.3,0.1

Type RM Length L Ch R = 1,9736,375,375,375
BEGIN DESCRIPTION:
UNT 044 in RCW 14.0
END DESCRIPTION:
XS GIS Cut Line= 3
      2039741.51     13454261.86      2039481.09     13454186.34
      2038054.06     13454168.11
#Sta/Elev= 30
  4018.5  446.61  4108.6  442.30  4289.6  436.01  4328.9  433.24  4365.7  431.07
  4565.2  427.53  4845.8  424.63  4985.8  424.90  4995.8  419.75  5002.5  418.89
  5003.0  418.09  5008.5  418.09  5009.0  418.89  5015.8  424.27  5025.8  425.81
  5065.8  424.94  5085.8  421.78  5105.8  421.90  5115.8  424.01  5125.8  424.28
  5195.8  423.12  5214.5  426.07  5235.8  427.27  5265.8  426.84  5275.8  425.38
  5285.8  421.31  5295.8  425.98  5323.5  426.78  5445.8  436.27  5716.8  442.96
#Mann=7,-1,0
  4018.5     0.1       0  4328.9    0.05       0  4565.2     0.1       0
  5002.5    0.07       0  5009.0     0.1       0  5214.5    0.08       0
  5323.5     0.1       0
Bank Sta=5002.5,5009
Exp/Cntr=0.3,0.1

Type RM Length L Ch R = 1,9361,139,139,139
BEGIN DESCRIPTION:
UNT 044 in RCW 13.0
END DESCRIPTION:
XS GIS Cut Line= 3
      2039679.03     13453938.95      2039116.51     13453751.45
      2038129.80     13453959.72
#Sta/Elev= 30
  3941.3  439.69  3987.7  439.74  4097.2  437.72  4128.9  436.33  4155.2  433.85
  4160.5  434.04  4177.4  431.58  4222.8  428.64  4396.9  425.62  4489.7  424.27
  4591.5  423.39  4593.5  423.37  4793.7  422.06  4944.6  421.48  4992.5  419.72
  4993.0  418.92  4998.5  418.92  4999.0  419.72  5009.5  420.41  5097.1  422.33
  5128.6  423.24  5155.4  425.55  5160.5  425.01  5189.9  427.96  5241.0  427.61
  5255.6  431.98  5261.4  432.85  5343.2  434.52  5363.6  435.80  5542.7  441.16
#Mann=12,-1,0
  3941.3     0.1       0  4222.8    0.05       0  4396.9     0.1       0
  4489.7    0.08       0  4591.5    0.05       0  4593.5     0.1       0
  4793.7    0.05       0  4992.5    0.04       0  4999.0    0.05       0
  5009.5     0.1       0  5097.1    0.08       0  5255.6     0.1       0
Bank Sta=4992.5,4999
Exp/Cntr=0.3,0.1

Type RM Length L Ch R = 1,9222,241,241,241
BEGIN DESCRIPTION:
Mapping XS 04f9a8e9
END DESCRIPTION:
XS GIS Cut Line= 4
      2039613.86     13453847.79      2038965.47     13453683.74
      2038533.18     13453808.74      2038113.89     13453915.51
#Sta/Elev= 30
  4091.2  438.41  4193.2  437.49  4283.4  429.59  4317.7  427.69  4465.5  425.15
  4559.6  424.15  4660.2  423.52  4812.6  421.10  4929.4  422.07  4954.6  418.34
  4955.1  417.54  4961.1  418.34  4963.0  420.03  4967.3  419.64  4989.5  418.51
  4996.7  419.80  5001.9  418.42  5010.3  419.62  5030.3  421.42  5035.5  420.31
  5069.1  421.90  5173.8  423.43  5219.4  424.50  5296.0  428.88  5336.9  428.29
  5344.6  430.45  5352.6  432.19  5372.7  431.79  5582.3  438.61  5642.7  442.06
#Mann=11,-1,0
  4091.2     0.1       0  4317.7    0.05       0  4465.5     0.1       0
  4559.6    0.08       0  4660.2    0.05       0  4954.6    0.07       0
  4961.1    0.05       0  4967.3     0.1       0  5010.3    0.05       0
  5173.8    0.08       0  5344.6     0.1       0
Bank Sta=4954.6,4961.1
Exp/Cntr=0.3,0.1

Type RM Length L Ch R = 1,8981,345,345,345
BEGIN DESCRIPTION:
Mapping XS 5ec3aca4
END DESCRIPTION:
XS GIS Cut Line= 4
      2039634.73     13453777.49      2038790.99     13453616.03
      2038637.34     13453522.28      2038128.42     13453597.58
#Sta/Elev= 30
  4059.7  437.18  4161.2  437.46  4222.3  434.05  4258.6  429.26  4273.2  428.23
  4324.6  427.03  4444.9  425.19  4541.8  423.63  4641.3  423.14  4660.1  423.01
  4772.1  421.26  4802.7  419.66  4946.4  421.24  4985.8  418.13  4986.3  417.33
  4991.8  417.33  4992.3  418.13  5018.9  418.68  5089.8  419.34  5212.3  424.09
  5273.5  425.03  5303.3  426.05  5343.7  430.49  5360.1  430.93  5384.2  430.76
  5404.4  429.44  5422.2  431.07  5434.7  430.63  5459.9  432.28  5613.2  438.17
#Mann=12,-1,0
  4059.7     0.1       0  4324.6    0.05       0  4444.9     0.1       0
  4541.8    0.08       0  4641.3    0.05       0  4660.1     0.1       0
  4985.8    0.07       0  4992.3     0.1       0  5018.9    0.05       0
  5273.5    0.08       0  5360.1    0.05       0  5459.9     0.1       0
Bank Sta=4985.8,4992.3
Exp/Cntr=0.3,0.1

Type RM Length L Ch R = 1,8636,351,351,351
BEGIN DESCRIPTION:
UNT 044 in RCW 12.0
END DESCRIPTION:
XS GIS Cut Line= 3
      2039608.69     13453694.15      2038835.26     13453389.47
      2038172.14     13453269.85
#Sta/Elev= 30
  4314.4  435.77  4378.9  434.86  4425.8  432.47  4484.3  431.13  4554.8  426.98
  4707.7  423.98  4871.6  421.78  4931.2  418.79  4974.0  417.73  4982.0  416.38
  4982.5  415.58  4988.1  415.58  4988.6  416.38  5034.1  419.44  5049.2  418.93
  5142.0  419.99  5312.6  420.96  5483.5  423.66  5511.8  424.80  5537.1  426.94
  5552.4  429.28  5601.6  430.17  5633.7  431.46  5649.3  433.29  5684.5  433.92
  5707.9  433.50  5715.0  432.58  5749.5  434.73  5761.5  435.67  5819.5  436.84
#Mann=8,-1,0
  4314.4     0.1       0  4484.3    0.05       0  4707.7     0.1       0
  4982.0    0.07       0  4988.6     0.1       0  5142.0    0.05       0
  5601.6    0.08       0  5749.5     0.1       0
Bank Sta=4982,4988.6
Exp/Cntr=0.3,0.1

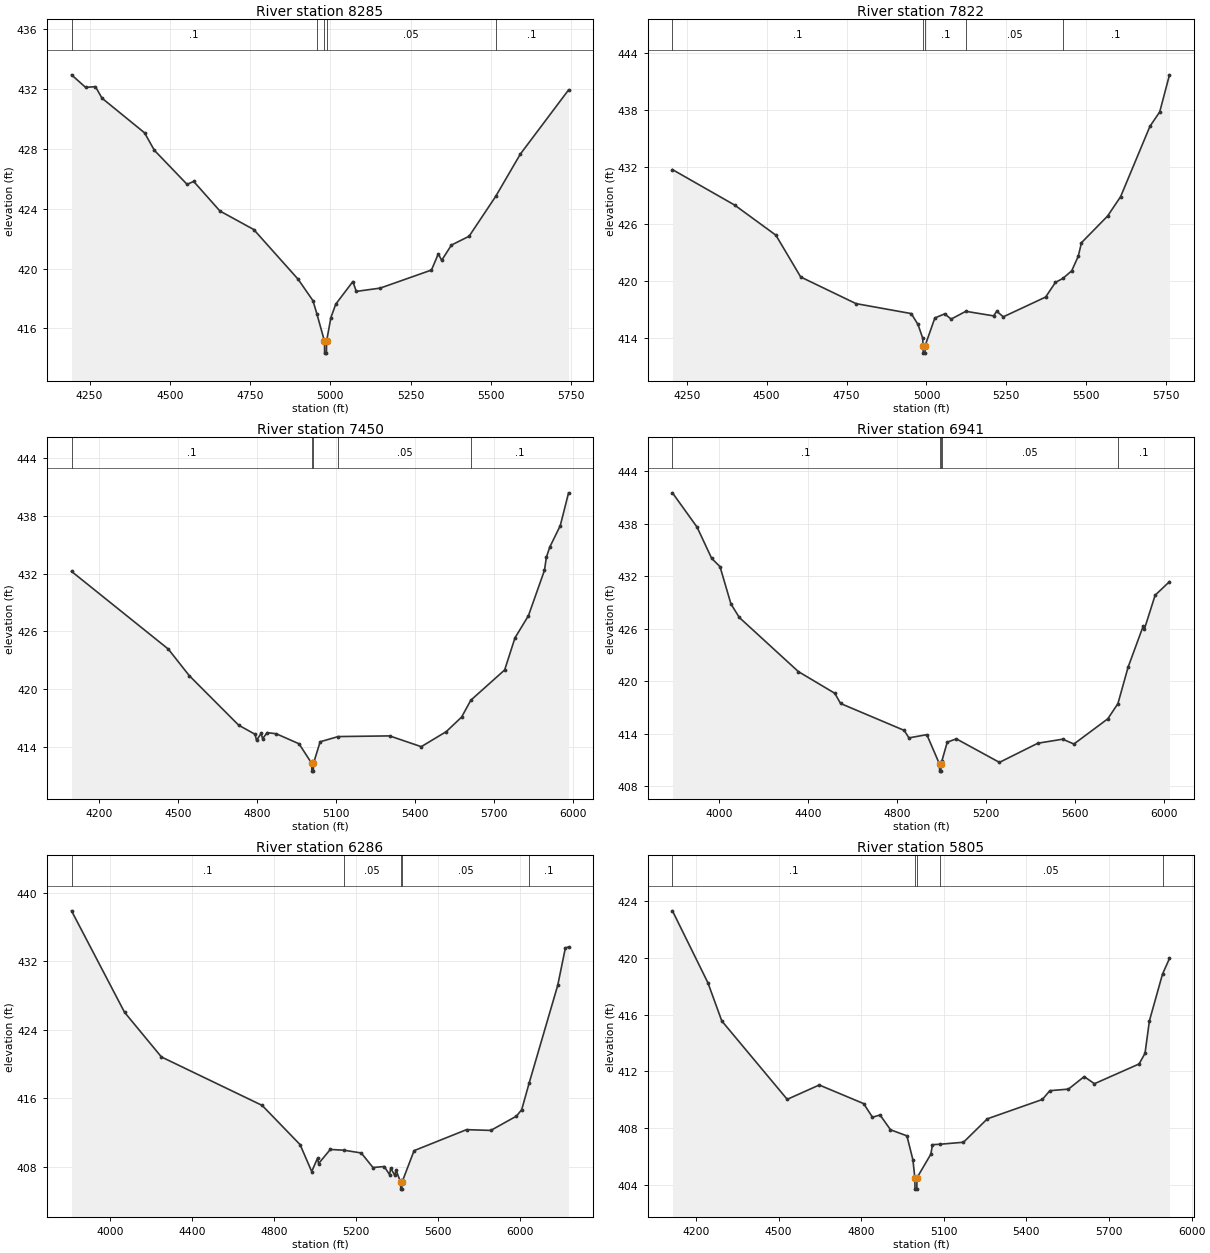
Type RM Length L Ch R = 1,8285,463,463,463
BEGIN DESCRIPTION:
UNT 044 in RCW 11.0
END DESCRIPTION:
XS GIS Cut Line= 3
      2039778.00     13453326.97      2039301.41     13453230.61
      2038303.99     13452866.02
#Sta/Elev= 30
  4193.7  432.96  4237.6  432.12  4268.2  432.17  4288.6  431.40  4421.2  429.08
  4451.8  427.91  4553.8  425.63  4574.2  425.83  4655.9  423.85  4761.3  422.61
  4899.7  419.28  4945.7  417.85  4958.2  416.95  4981.6  415.14  4982.1  414.34
  4987.7  414.34  4988.2  415.14  5001.5  416.71  5016.8  417.62  5070.1  419.13
  5080.7  418.47  5155.2  418.69  5314.9  419.90  5336.2  420.98  5346.6  420.55
  5377.1  421.57  5432.1  422.16  5514.7  424.82  5591.8  427.66  5741.9  431.95
#Mann=5,-1,0
  4193.7     0.1       0  4958.2    0.05       0  4981.6    0.03       0
  4988.2    0.05       0  5514.7     0.1       0
Bank Sta=4981.6,4988.2
Exp/Cntr=0.3,0.1

Type RM Length L Ch R = 1,7822,372,372,372
BEGIN DESCRIPTION:
UNT 044 in RCW 10.0
END DESCRIPTION:
XS GIS Cut Line= 3
      2039775.04     13453175.03      2039125.00     13452725.00
      2038374.97     13452574.99
#Sta/Elev= 30
  4205.1  431.69  4399.7  427.96  4528.8  424.79  4606.5  420.39  4779.5  417.59
  4952.5  416.54  4973.4  415.40  4988.3  413.96  4989.4  413.18  4989.9  412.38
  4995.5  412.38  4996.0  413.18  5026.3  416.08  5056.9  416.51  5077.3  415.96
  5123.3  416.78  5209.9  416.30  5220.1  416.78  5240.5  416.20  5373.0  418.28
  5403.6  419.82  5427.0  420.24  5454.6  421.04  5475.0  422.57  5485.2  424.00
  5566.8  426.80  5607.6  428.84  5699.4  436.24  5730.0  437.76  5760.6  441.66
#Mann=5,-1,0
  4205.1     0.1       0  4989.4    0.07       0  4996.0     0.1       0
  5123.3    0.05       0  5427.0     0.1       0
Bank Sta=4989.4,4996
Exp/Cntr=0.3,0.1

Type RM Length L Ch R = 1,7450,509,509,509
BEGIN DESCRIPTION:
UNT 044 in RCW 9.0
END DESCRIPTION:
XS GIS Cut Line= 4
      2039875.02     13453125.04      2039624.32     13452613.43
      2039046.20     13452350.40      2038375.05     13452474.99
#Sta/Elev= 30
  4096.2  432.24  4463.7  424.17  4543.3  421.41  4731.1  416.26  4793.2  415.32
  4798.7  414.69  4816.3  415.41  4821.8  414.86  4839.4  415.49  4873.9  415.37
  4960.2  414.33  5008.5  412.29  5009.0  411.49  5014.6  411.49  5015.1  412.29
  5040.3  414.54  5108.8  415.08  5304.2  415.15  5424.3  414.03  5519.5  415.60
  5577.4  417.10  5612.6  418.86  5741.0  422.00  5780.3  425.34  5831.2  427.63
  5892.2  432.35  5899.4  433.70  5912.6  434.78  5952.2  436.99  5983.7  440.40
#Mann=5,-1,0
  4096.2     0.1       0  5008.5    0.07       0  5015.1     0.1       0
  5108.8    0.05       0  5612.6     0.1       0
Bank Sta=5008.5,5015.1
Exp/Cntr=0.3,0.1

Type RM Length L Ch R = 1,6941,655,655,655
BEGIN DESCRIPTION:
UNT 044 in RCW 8.0
END DESCRIPTION:
XS GIS Cut Line= 4
      2040324.98     13452824.96      2039970.68     13452186.34
      2039197.24     13452027.49      2038491.47     13452149.89
#Sta/Elev= 30
  3790.0  441.54  3901.0  437.61  3966.2  434.06  4004.0  433.10  4053.2  428.84
  4090.9  427.29  4356.4  421.11  4520.3  418.63  4546.5  417.46  4832.4  414.39
  4854.0  413.53  4934.5  413.90  4991.5  410.53  4992.0  409.73  4997.7  409.73
  4998.2  410.53  5002.5  410.92  5026.3  413.04  5067.2  413.42  5261.1  410.73
  5434.0  412.92  5545.6  413.38  5596.3  412.83  5748.6  415.71  5794.1  417.44
  5839.9  421.61  5907.8  426.30  5912.9  425.94  5961.7  429.84  6026.2  431.39
#Mann=5,-1,0
  3790.0     0.1       0  4991.5    0.07       0  4998.2     0.1       0
  5002.5    0.05       0  5794.1     0.1       0
Bank Sta=4991.5,4998.2
Exp/Cntr=0.3,0.1

Type RM Length L Ch R = 1,6286,481,481,481
BEGIN DESCRIPTION:
UNT 044 in RCW 7.0
END DESCRIPTION:
XS GIS Cut Line= 4
      2040424.99     13452474.98      2040108.70     13451756.65
      2039389.95     13451675.93      2038525.04     13451974.99
#Sta/Elev= 30
  3811.8  437.89  4070.4  426.05  4250.2  420.84  4741.1  415.19  4926.3  410.61
  4982.8  407.47  5011.3  409.03  5016.3  408.40  5073.4  410.05  5140.0  409.96
  5224.3  409.64  5281.5  407.94  5336.7  408.06  5362.6  407.10  5367.9  407.86
  5388.5  407.01  5393.8  407.66  5416.3  406.22  5416.8  405.42  5422.5  405.42
  5423.0  406.22  5482.0  409.91  5737.8  412.36  5856.1  412.27  5981.2  413.94
  6006.6  414.69  6042.5  417.76  6182.2  429.19  6219.6  433.56  6235.1  433.68
#Mann=5,-1,0
  3811.8     0.1       0  5140.0    0.05       0  5416.3    0.07       0
  5423.0    0.05       0  6042.5     0.1       0
Bank Sta=5416.3,5423
Exp/Cntr=0.3,0.1

Type RM Length L Ch R = 1,5805,430,430,430
BEGIN DESCRIPTION:
UNT 044 in RCW 6.0
END DESCRIPTION:
XS GIS Cut Line= 3
      2040251.91     13450897.29      2039475.00     13451325.00
      2038675.04     13451774.98
#Sta/Elev= 30
  4114.8  423.30  4243.7  418.23  4293.9  415.55  4531.5  410.03  4647.8  411.04
  4809.0  409.73  4841.1  408.77  4868.6  408.93  4906.5  407.89  4966.1  407.46
  4987.9  405.77  4994.9  404.51  4995.5  403.71  5002.1  403.71  5002.7  404.51
  5053.0  406.17  5059.0  406.84  5086.4  406.87  5171.5  407.01  5258.2  408.66
  5457.7  410.02  5485.1  410.64  5552.4  410.75  5609.8  411.63  5647.0  411.13
  5809.0  412.52  5830.6  413.27  5846.6  415.56  5894.2  418.85  5919.5  419.95
#Mann=5,-1,0
  4114.8     0.1       0  4994.9    0.07       0  5002.7     0.1       0
  5086.4    0.05       0  5894.2     0.1       0
Bank Sta=4994.9,5002.7
Exp/Cntr=0.3,0.1

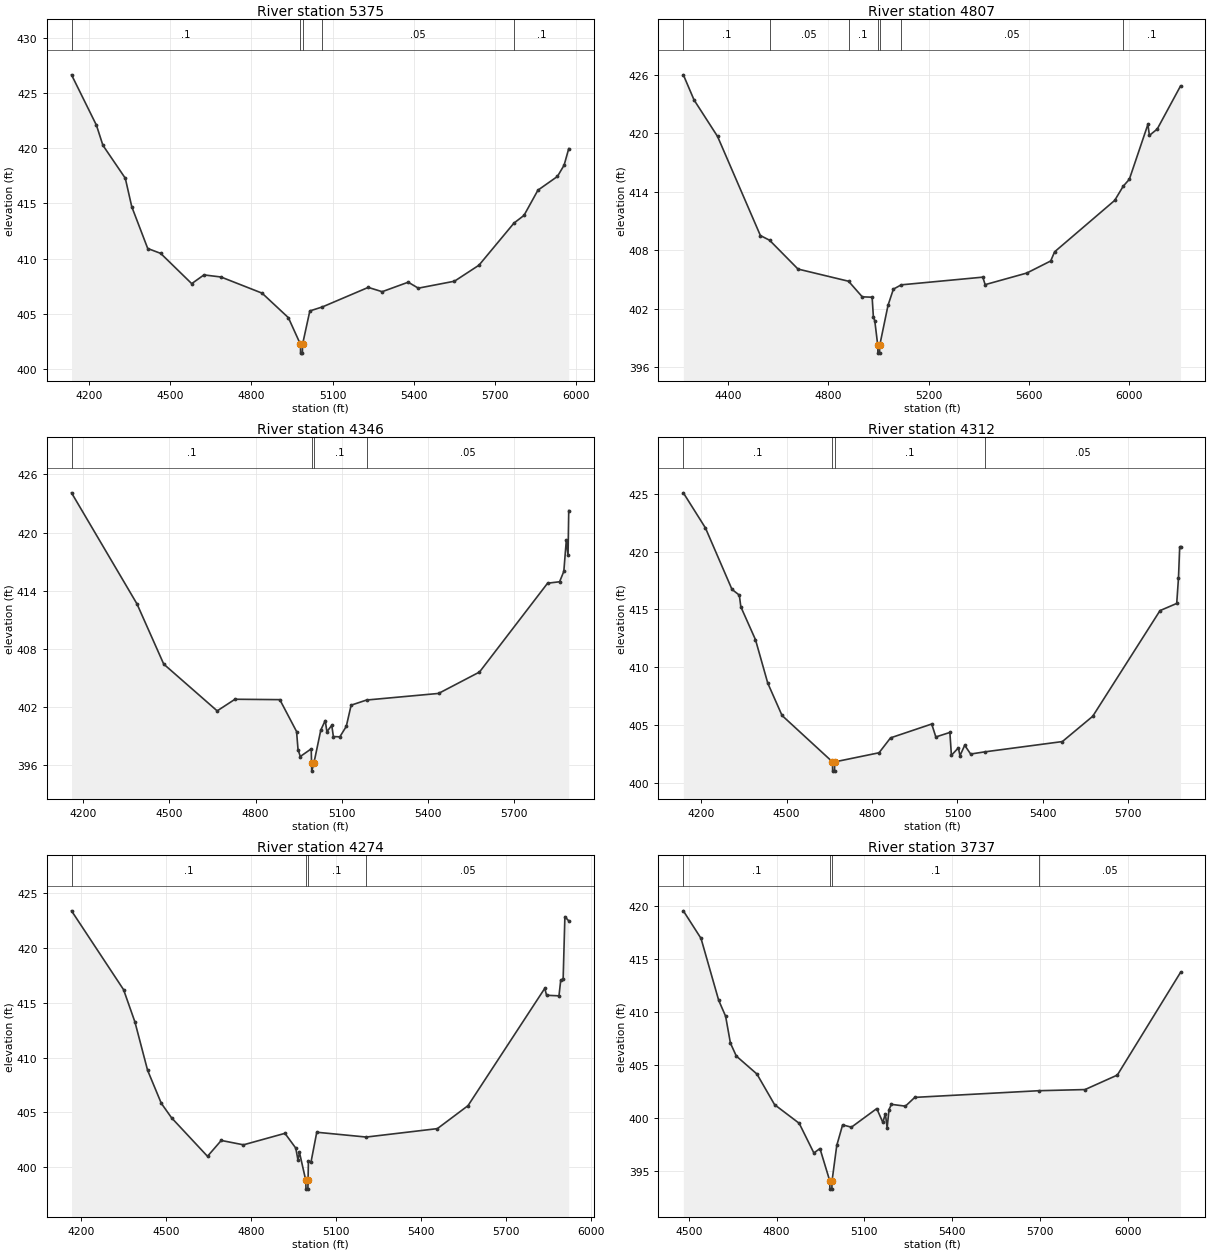
Type RM Length L Ch R = 1,5375,568,568,568
BEGIN DESCRIPTION:
UNT 044 in RCW 5.0
END DESCRIPTION:
XS GIS Cut Line= 3
      2040124.99     13450725.00      2039442.03     13451006.65
      2038374.27     13451254.06
#Sta/Elev= 30
  4136.8  426.63  4228.7  422.07  4252.6  420.25  4335.2  417.27  4359.1  414.69
  4418.0  410.91  4465.7  410.47  4580.3  407.73  4625.5  408.52  4688.5  408.33
  4839.9  406.87  4937.0  404.65  4981.5  402.24  4982.1  401.44  4988.7  401.44
  4989.4  402.24  5016.2  405.26  5062.4  405.62  5231.8  407.39  5283.1  407.00
  5379.2  407.86  5416.5  407.32  5549.9  407.95  5640.4  409.40  5769.5  413.21
  5806.6  413.91  5857.9  416.19  5929.8  417.43  5954.5  418.45  5971.6  419.95
#Mann=5,-1,0
  4136.8     0.1       0  4981.5    0.07       0  4989.4     0.1       0
  5062.4    0.05       0  5769.5     0.1       0
Bank Sta=4981.5,4989.4
Exp/Cntr=0.3,0.1

Type RM Length L Ch R = 1,4807,461,461,461
BEGIN DESCRIPTION:
UNT 044 in RCW 4.0
END DESCRIPTION:
XS GIS Cut Line= 3
      2039925.00     13450125.00      2039325.00     13450575.00
      2038264.96     13451204.57
#Sta/Elev= 30
  4222.1  425.99  4264.8  423.41  4358.6  419.66  4529.4  409.49  4566.0  409.01
  4679.4  406.05  4881.0  404.80  4935.6  403.20  4975.0  403.16  4979.9  401.17
  4985.7  400.71  4997.4  398.22  4998.0  397.42  5004.6  397.42  5005.3  398.22
  5038.4  402.33  5059.8  403.99  5091.1  404.43  5416.3  405.22  5425.7  404.45
  5591.7  405.64  5687.1  406.88  5702.7  407.82  5942.4  413.10  5976.2  414.55
  6000.8  415.27  6074.9  420.91  6080.7  419.77  6111.9  420.42  6205.0  424.85
#Mann=7,-1,0
  4222.1     0.1       0  4566.0    0.05       0  4881.0     0.1       0
  4997.4    0.07       0  5005.3     0.1       0  5091.1    0.05       0
  5976.2     0.1       0
Bank Sta=4997.4,5005.3
Exp/Cntr=0.3,0.1

Type RM Length L Ch R = 1,4346,34,34,34
BEGIN DESCRIPTION:
Mapping XS dbfccf47
END DESCRIPTION:
XS GIS Cut Line= 6
      2039869.93     13450002.79      2039214.56     13450232.81
      2039090.86     13450256.69      2039030.10     13450269.71
      2038889.04     13450339.15      2038328.52     13450741.69
#Sta/Elev= 30
  4159.6  424.10  4387.4  412.63  4480.4  406.42  4666.4  401.59  4728.4  402.79
  4884.3  402.75  4942.6  399.46  4947.7  397.60  4955.6  396.88  4993.6  397.67
  4994.8  396.17  4995.4  395.37  5002.7  396.17  5027.0  399.62  5042.3  400.59
  5048.2  399.44  5065.1  400.10  5070.7  398.94  5093.2  398.91  5115.6  399.99
  5132.5  402.18  5186.3  402.71  5436.6  403.39  5579.1  405.60  5816.0  414.77
  5857.8  414.92  5872.5  415.99  5881.1  419.19  5887.2  417.66  5889.6  422.27
#Mann=4,-1,0
  4159.6     0.1       0  4994.8    0.07       0  5002.7     0.1       0
  5186.3    0.05       0
Bank Sta=4994.8,5002.7
Exp/Cntr=0.3,0.1

Type RM Length L Ch R = 1,4312,38,38,38
BEGIN DESCRIPTION:
UNT 044 in RCW 3.0
END DESCRIPTION:
XS GIS Cut Line= 5
      2039874.96     13449975.02      2039246.72     13450194.15
      2039098.28     13450214.99      2038942.03     13450274.88
      2038325.04     13450724.97
#Sta/Elev= 30
  4137.2  425.09  4214.8  422.05  4308.0  416.73  4333.8  416.23  4339.1  415.22
  4390.6  412.37  4433.7  408.61  4483.8  405.81  4661.0  401.79  4661.6  400.99
  4668.2  400.99  4668.9  401.79  4824.5  402.58  4864.9  403.87  5009.5  405.07
  5024.0  403.95  5073.3  404.34  5078.7  402.36  5103.3  403.01  5108.7  402.32
  5125.4  403.23  5146.2  402.47  5196.2  402.66  5468.4  403.55  5575.0  405.74
  5811.3  414.89  5870.0  415.51  5876.2  417.71  5880.5  420.42  5883.5  420.42
#Mann=4,-1,0
  4137.2     0.1       0  4661.0    0.07       0  4668.9     0.1       0
  5196.2    0.05       0
Bank Sta=4661,4668.9
Exp/Cntr=0.3,0.1

Type RM Length L Ch R = 1,4274,537,537,537
BEGIN DESCRIPTION:
Mapping XS ba6306d1
END DESCRIPTION:
XS GIS Cut Line= 6
      2039828.70     13449955.04      2039208.05     13450172.05
      2039077.84     13450185.07      2039025.76     13450202.43
      2038951.97     13450234.98      2038281.37     13450729.80
#Sta/Elev= 30
  4165.5  423.41  4349.5  416.20  4389.6  413.25  4434.3  408.84  4482.7  405.82
  4519.1  404.49  4646.1  400.97  4694.7  402.42  4773.3  402.02  4919.8  403.07
  4958.1  401.72  4965.9  400.63  4971.2  401.32  4993.5  398.77  4994.2  397.97
  5000.9  397.97  5001.5  398.77  5002.8  400.53  5012.0  400.45  5032.3  403.17
  5207.3  402.73  5458.6  403.50  5566.9  405.60  5838.3  416.33  5844.5  415.69
  5888.4  415.64  5894.7  417.08  5903.1  417.15  5909.3  422.88  5922.9  422.49
#Mann=4,-1,0
  4165.5     0.1       0  4993.5    0.07       0  5001.5     0.1       0
  5207.3    0.05       0
Bank Sta=4993.5,5001.5
Exp/Cntr=0.3,0.1

Type RM Length L Ch R = 1,3737,48,48,48
BEGIN DESCRIPTION:
UNT 044 in RCW 2.0
END DESCRIPTION:
XS GIS Cut Line= 6
      2039675.04     13449925.00      2039297.07     13449885.13
      2039092.21     13449817.42      2038982.83     13449897.28
      2038939.43     13450194.15      2038325.03     13450424.99
#Sta/Elev= 30
  4481.6  419.57  4542.0  416.96  4602.3  411.11  4626.0  409.60  4642.5  407.05
  4662.6  405.83  4733.0  404.13  4793.4  401.23  4877.4  399.47  4927.6  396.66
  4948.4  397.08  4981.7  394.04  4982.4  393.24  4989.1  393.24  4989.8  394.04
  5005.8  397.37  5025.8  399.32  5055.9  399.10  5142.5  400.86  5163.3  399.55
  5171.8  400.37  5178.0  399.05  5184.3  400.77  5192.7  401.26  5240.4  401.09
  5272.4  401.92  5695.3  402.55  5854.1  402.66  5964.4  404.03  6180.5  413.75
#Mann=4,-1,0
  4481.6     0.1       0  4981.7    0.07       0  4989.8     0.1       0
  5695.3    0.05       0
Bank Sta=4981.7,4989.8
Exp/Cntr=0.3,0.1

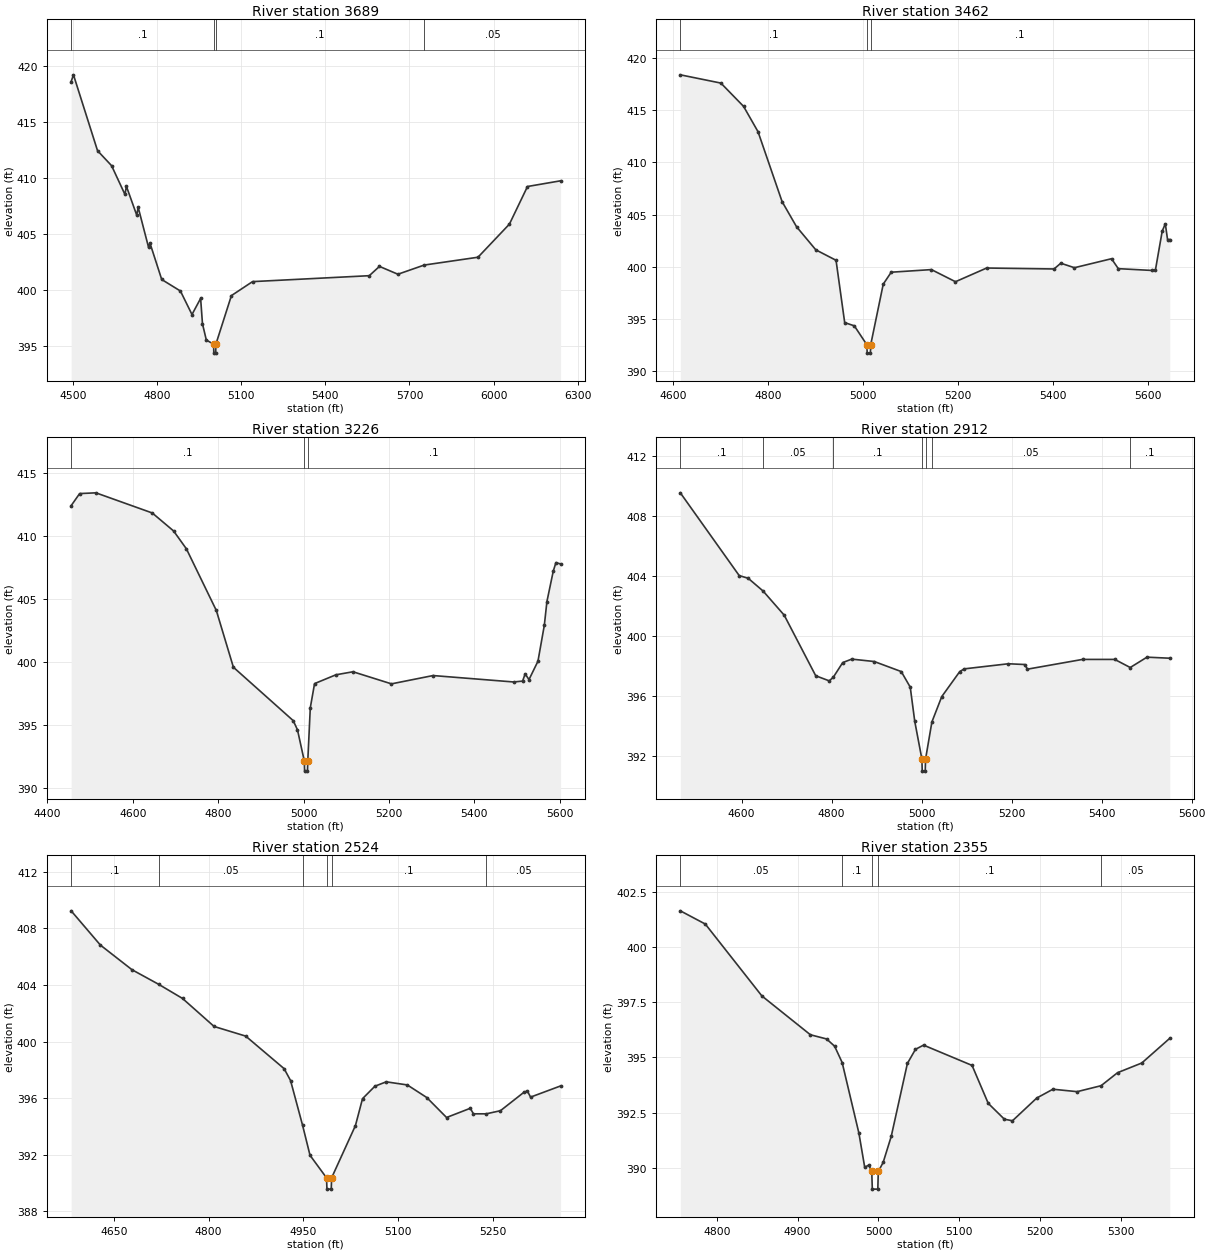
Type RM Length L Ch R = 1,3689,227,227,227
BEGIN DESCRIPTION:
Mapping XS 531d10a9
END DESCRIPTION:
XS GIS Cut Line= 6
      2039678.97     13449850.40      2039484.57     13449839.99
      2039111.30     13449770.54      2038930.75     13449839.99
      2038869.98     13450185.47      2038274.45     13450374.73
#Sta/Elev= 30
  4493.9  418.60  4502.2  419.21  4588.0  412.43  4638.1  411.09  4685.7  408.52
  4690.9  409.25  4727.7  406.67  4732.9  407.37  4769.7  403.81  4774.8  404.18
  4816.8  400.92  4883.5  399.89  4924.7  397.79  4955.5  399.23  4962.1  396.96
  4975.8  395.51  5001.8  395.14  5002.5  394.34  5009.2  394.34  5009.9  395.14
  5065.2  399.48  5140.6  400.73  5556.7  401.26  5593.0  402.09  5658.8  401.39
  5752.5  402.21  5944.3  402.91  6056.3  405.87  6120.7  409.23  6238.7  409.74
#Mann=4,-1,0
  4493.9     0.1       0  5001.8    0.07       0  5009.9     0.1       0
  5752.5    0.05       0
Bank Sta=5001.8,5009.9
Exp/Cntr=0.3,0.1

Type RM Length L Ch R = 1,3462,236,236,236
BEGIN DESCRIPTION:
Mapping XS 7b8d293a
END DESCRIPTION:
XS GIS Cut Line= 3
      2039566.37     13449506.22      2038958.74     13449608.22
      2038693.98     13449927.24
#Sta/Elev= 30
  4614.6  418.36  4700.0  417.57  4747.8  415.34  4778.2  412.92  4828.9  406.23
  4859.3  403.83  4899.9  401.62  4942.5  400.62  4960.7  394.66  4981.0  394.35
  5007.4  392.54  5008.1  391.74  5014.8  391.74  5015.5  392.54  5041.9  398.34
  5058.7  399.48  5143.3  399.73  5194.0  398.57  5259.6  399.88  5401.5  399.79
  5415.8  400.34  5444.5  399.91  5522.6  400.77  5536.9  399.82  5607.2  399.65
  5615.1  399.70  5629.4  403.42  5635.9  404.11  5640.6  402.60  5645.3  402.60
#Mann=3,-1,0
  4614.6     0.1       0  5007.4    0.07       0  5015.5     0.1       0
Bank Sta=5007.4,5015.5
Exp/Cntr=0.3,0.1

Type RM Length L Ch R = 1,3226,314,314,314
BEGIN DESCRIPTION:
Mapping XS 022c7394
END DESCRIPTION:
XS GIS Cut Line= 3
      2039674.89     13449371.67      2038918.94     13449350.96
      2038595.94     13449569.64
#Sta/Elev= 30
  4455.7  412.40  4475.6  413.36  4513.7  413.42  4645.7  411.82  4695.7  410.39
  4725.7  408.97  4795.7  404.08  4835.7  399.57  4975.8  395.33  4985.8  394.60
  5001.8  392.12  5002.5  391.32  5009.2  391.32  5009.9  392.12  5015.8  396.35
  5025.8  398.27  5075.8  398.97  5115.8  399.21  5205.9  398.25  5303.3  398.91
  5492.0  398.40  5513.0  398.47  5519.0  399.04  5528.0  398.59  5549.0  400.05
  5563.9  402.90  5570.0  404.79  5584.9  407.21  5591.1  407.88  5602.0  407.77
#Mann=3,-1,0
  4455.7     0.1       0  5001.8    0.07       0  5009.9     0.1       0
Bank Sta=5001.8,5009.9
Exp/Cntr=0.3,0.1

Type RM Length L Ch R = 1,2912,388,388,388
BEGIN DESCRIPTION:
Mapping XS cbd4ad84
END DESCRIPTION:
XS GIS Cut Line= 3
      2039685.76     13449119.94      2038973.57     13449111.43
      2038759.76     13449419.70
#Sta/Elev= 30
  4464.0  409.53  4594.8  404.01  4614.8  403.83  4647.9  402.98  4694.8  401.37
  4764.8  397.33  4794.8  396.99  4803.8  397.23  4824.8  398.21  4844.8  398.44
  4894.8  398.28  4954.8  397.61  4974.8  396.57  4984.8  394.29  5000.7  391.77
  5001.4  390.97  5008.1  390.97  5008.8  391.77  5022.9  394.25  5044.8  395.94
  5084.8  397.61  5094.8  397.79  5192.7  398.13  5229.2  398.08  5235.2  397.77
  5357.5  398.42  5429.1  398.42  5463.5  397.88  5500.7  398.57  5551.4  398.50
#Mann=7,-1,0
  4464.0     0.1       0  4647.9    0.05       0  4803.8     0.1       0
  5000.7    0.07       0  5008.8     0.1       0  5022.9    0.05       0
  5463.5     0.1       0
Bank Sta=5000.7,5008.8
Exp/Cntr=0.3,0.1

Type RM Length L Ch R = 1,2524,169,169,169
BEGIN DESCRIPTION:
Mapping XS 6aa9788d
END DESCRIPTION:
XS GIS Cut Line= 3
      2039731.26     13448944.15      2039425.32     13448944.15
      2038968.72     13448838.12
#Sta/Elev= 30
  4582.3  409.24  4628.6  406.82  4678.6  405.08  4720.8  404.05  4758.6  403.05
  4808.6  401.07  4858.6  400.39  4919.4  398.09  4929.6  397.25  4948.5  394.11
  4960.4  391.97  4986.5  390.38  4987.2  389.58  4994.0  389.58  4994.6  390.38
  5032.3  394.07  5043.5  395.97  5063.1  396.85  5081.0  397.16  5114.4  396.94
  5145.2  396.05  5176.5  394.64  5214.0  395.29  5219.1  394.90  5239.4  394.90
  5261.8  395.12  5299.2  396.43  5304.4  396.51  5309.5  396.08  5357.0  396.87
#Mann=6,-1,0
  4582.3     0.1       0  4720.8    0.05       0  4948.5     0.1       0
  4986.5    0.07       0  4994.6     0.1       0  5239.4    0.05       0
Bank Sta=4986.5,4994.6
Exp/Cntr=0.3,0.1

Type RM Length L Ch R = 1,2355,334,334,334
BEGIN DESCRIPTION:
Mapping XS 0e6c0d61
END DESCRIPTION:
XS GIS Cut Line= 2
      2039585.88     13448757.52      2038980.42     13448764.03
#Sta/Elev= 30
  4754.9  401.65  4785.8  401.05  4855.8  397.79  4915.8  396.03  4935.8  395.84
  4945.8  395.51  4955.1  394.77  4975.8  391.57  4983.0  390.02  4988.0  390.12
  4991.7  389.83  4992.4  389.03  4999.2  389.03  4999.8  389.83  5005.8  390.24
  5015.8  391.42  5035.8  394.73  5045.8  395.37  5055.8  395.56  5115.8  394.64
  5135.8  392.92  5155.8  392.20  5165.8  392.13  5195.8  393.16  5215.8  393.56
  5245.8  393.45  5275.4  393.72  5295.8  394.31  5325.8  394.75  5360.4  395.87
#Mann=5,-1,0
  4754.9    0.05       0  4955.1     0.1       0  4991.7    0.07       0
  4999.8     0.1       0  5275.4    0.05       0
Bank Sta=4991.7,4999.8
Exp/Cntr=0.3,0.1