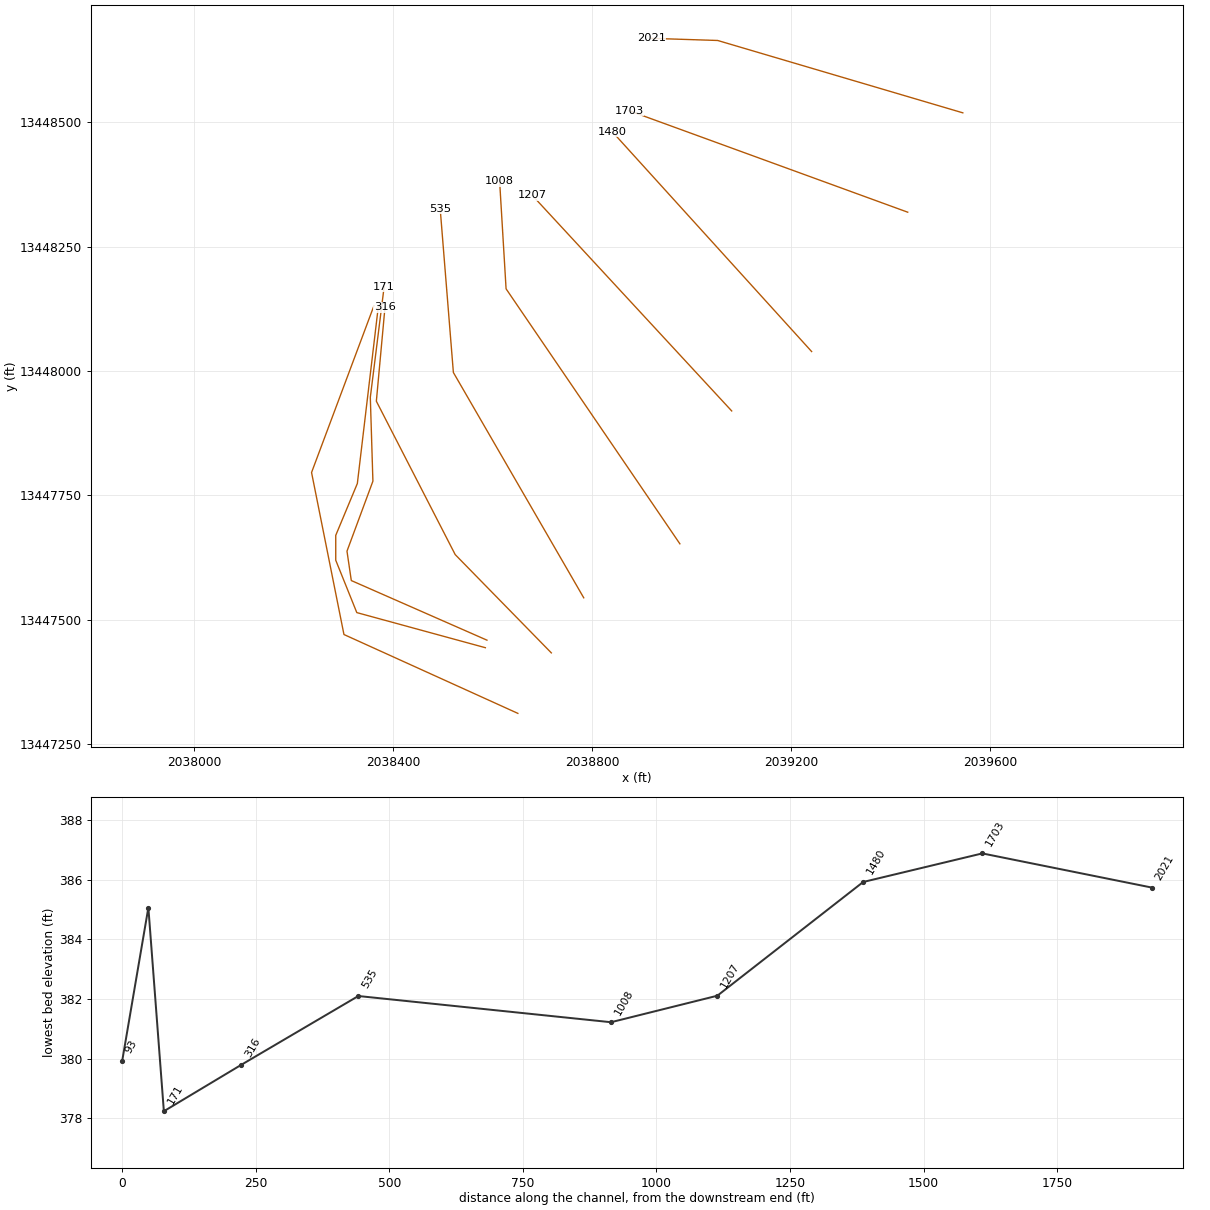
HEC-RAS study UNT 044 in RCW.prj: UNT 044 in RCW Base Level Engineering

--- UNT 044 in RCW.g01 (geometry) --- (continued)

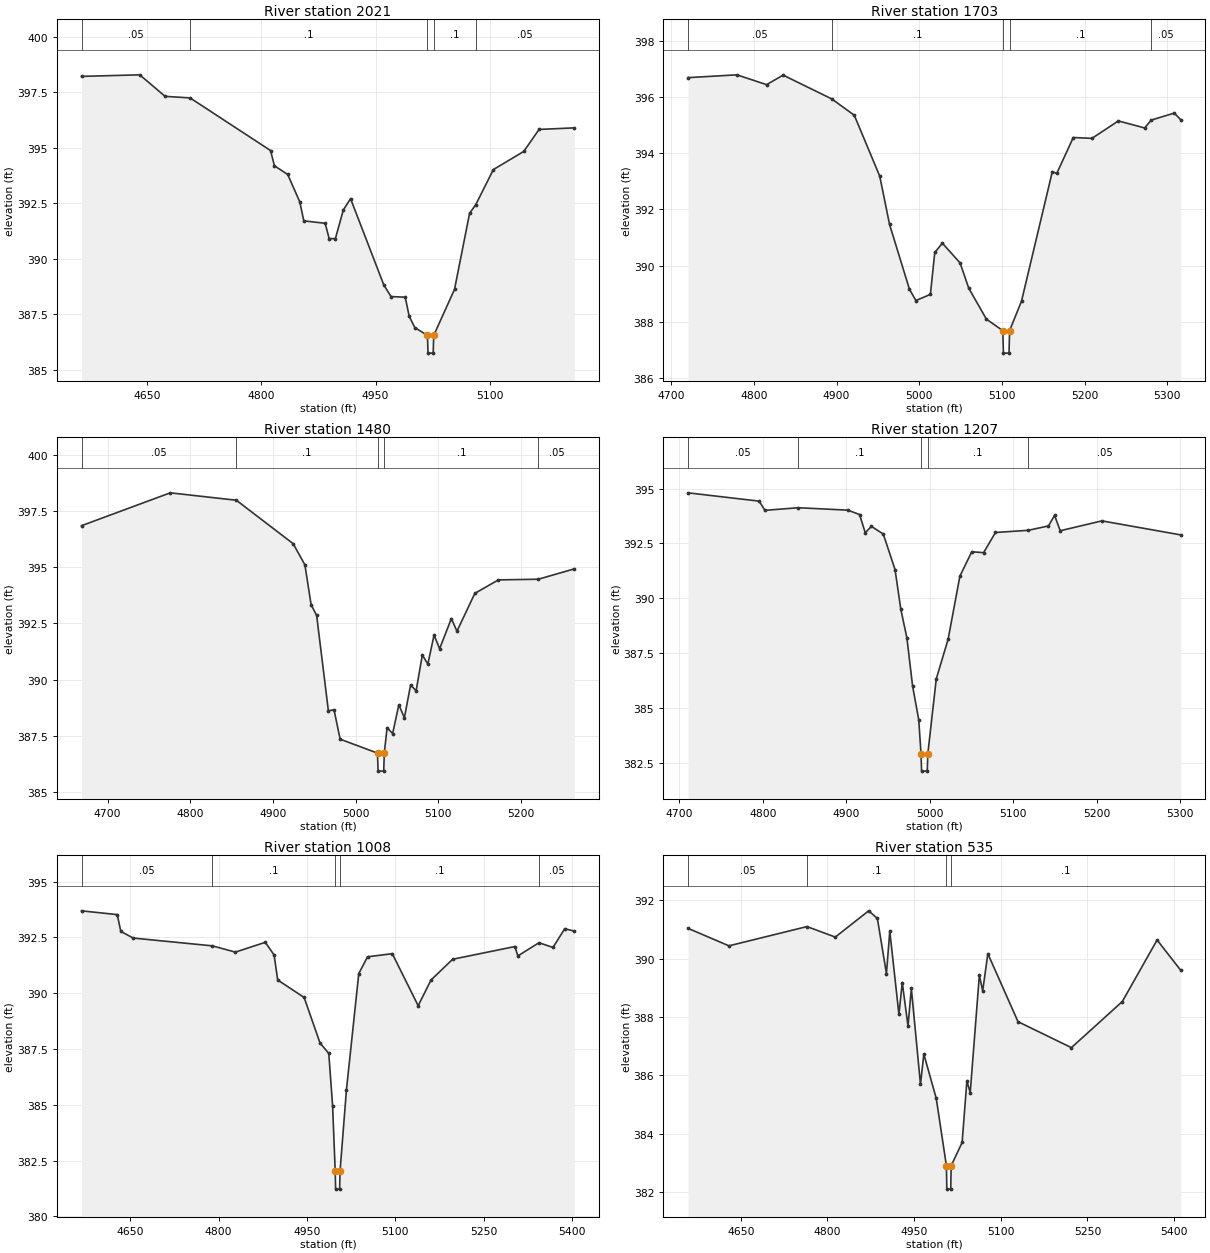
Type RM Length L Ch R = 1,2021,318,318,318
BEGIN DESCRIPTION:
Mapping XS cdf792cf
END DESCRIPTION:
XS GIS Cut Line= 3
      2039544.67     13448518.81      2039052.06     13448664.21
      2038918.75     13448668.51
#Sta/Elev= 30
  4563.9  398.21  4640.3  398.28  4673.6  397.31  4706.4  397.24  4812.0  394.87
  4817.2  394.18  4834.6  393.79  4850.5  392.55  4855.7  391.70  4883.8  391.59
  4889.0  390.90  4897.2  390.90  4907.6  392.19  4917.1  392.70  4960.8  388.81
  4970.2  388.29  4988.9  388.26  4994.1  387.40  5001.5  386.89  5018.1  386.54
  5018.8  385.74  5025.6  385.74  5026.3  386.54  5053.6  388.61  5073.4  392.04
  5081.5  392.43  5104.6  394.01  5144.6  394.83  5164.6  395.82  5210.9  395.89
#Mann=5,-1,0
  4563.9    0.05       0  4706.4     0.1       0  5018.1    0.07       0
  5026.3     0.1       0  5081.5    0.05       0
Bank Sta=5018.1,5026.3
Exp/Cntr=0.3,0.1

Type RM Length L Ch R = 1,1703,223,223,223
BEGIN DESCRIPTION:
Mapping XS 83ec7815
END DESCRIPTION:
XS GIS Cut Line= 2
      2039433.98     13448319.16      2038874.08     13448523.16
#Sta/Elev= 30
  4720.3  396.69  4779.5  396.79  4815.3  396.44  4835.3  396.78  4894.3  395.93
  4921.4  395.35  4952.2  393.18  4964.0  391.47  4988.1  389.16  4995.9  388.76
  5013.4  388.98  5018.7  390.47  5027.9  390.80  5049.3  390.10  5059.8  389.20
  5081.1  388.10  5101.0  387.69  5101.7  386.89  5108.5  386.89  5109.2  387.69
  5123.6  388.74  5160.9  393.35  5166.2  393.28  5186.2  394.56  5208.8  394.53
  5240.7  395.15  5272.5  394.90  5280.5  395.18  5308.4  395.43  5316.2  395.19
#Mann=5,-1,0
  4720.3    0.05       0  4894.3     0.1       0  5101.0    0.07       0
  5109.2     0.1       0  5280.5    0.05       0
Bank Sta=5101,5109.2
Exp/Cntr=0.3,0.1

Type RM Length L Ch R = 1,1480,273,273,273
BEGIN DESCRIPTION:
Mapping XS 8141550d
END DESCRIPTION:
XS GIS Cut Line= 2
      2039240.86     13448039.21      2038840.55     13448480.63
#Sta/Elev= 30
  4668.6  396.84  4775.9  398.30  4855.8  397.97  4924.5  396.04  4938.7  395.10
  4946.2  393.33  4952.9  392.85  4967.1  388.61  4973.9  388.66  4981.3  387.35
  5026.5  386.73  5027.2  385.93  5034.0  385.93  5034.7  386.73  5038.1  387.86
  5044.8  387.60  5052.3  388.88  5059.0  388.30  5066.5  389.76  5073.2  389.50
  5080.7  391.09  5087.4  390.69  5094.9  391.98  5101.6  391.37  5115.8  392.71
  5122.6  392.15  5144.2  393.83  5172.6  394.43  5221.0  394.46  5264.5  394.92
#Mann=5,-1,0
  4668.6    0.05       0  4855.8     0.1       0  5026.5    0.07       0
  5034.7     0.1       0  5221.0    0.05       0
Bank Sta=5026.5,5034.7
Exp/Cntr=0.3,0.1

Type RM Length L Ch R = 1,1207,199,199,199
BEGIN DESCRIPTION:
Mapping XS 39ad4493
END DESCRIPTION:
XS GIS Cut Line= 2
      2039080.25     13447919.87      2038679.41     13448353.21
#Sta/Elev= 30
  4710.5  394.81  4795.8  394.43  4802.6  394.01  4842.6  394.13  4901.9  394.02
  4916.0  393.82  4922.8  392.99  4930.2  393.28  4944.4  392.93  4958.5  391.31
  4965.4  389.50  4972.7  388.19  4979.5  386.00  4986.9  384.45  4989.6  382.91
  4990.3  382.11  4997.1  382.11  4997.8  382.91  5007.9  386.32  5022.1  388.13
  5036.2  391.01  5050.4  392.12  5064.6  392.08  5078.8  393.00  5118.2  393.10
  5142.3  393.30  5149.6  393.78  5156.4  393.08  5206.3  393.53  5300.8  392.89
#Mann=5,-1,0
  4710.5    0.05       0  4842.6     0.1       0  4989.6    0.07       0
  4997.8     0.1       0  5118.2    0.05       0
Bank Sta=4989.6,4997.8
Exp/Cntr=0.3,0.1

Type RM Length L Ch R = 1,1008,473,473,473
BEGIN DESCRIPTION:
Mapping XS e33d5a1e
END DESCRIPTION:
XS GIS Cut Line= 3
      2038976.11     13447652.90      2038626.94     13448165.21
      2038613.99     13448381.14
#Sta/Elev= 30
  4567.4  393.69  4628.0  393.52  4634.0  392.77  4655.0  392.47  4789.5  392.12
  4828.5  391.84  4879.3  392.28  4894.2  391.71  4900.3  390.59  4945.1  389.81
  4972.1  387.77  4987.0  387.30  4993.5  384.94  4997.9  382.02  4998.6  381.22
  5005.4  381.22  5006.1  382.02  5016.9  385.65  5037.9  390.88  5052.8  391.63
  5094.8  391.77  5138.7  389.44  5160.5  390.59  5197.2  391.52  5302.9  392.09
  5307.9  391.67  5343.8  392.26  5367.5  392.05  5387.5  392.89  5403.7  392.78
#Mann=5,-1,0
  4567.4    0.05       0  4789.5     0.1       0  4997.9    0.07       0
  5006.1     0.1       0  5343.8    0.05       0
Bank Sta=4997.9,5006.1
Exp/Cntr=0.3,0.1

Type RM Length L Ch R = 1,535,219,219,219
BEGIN DESCRIPTION:
Mapping XS 45a8b386
END DESCRIPTION:
XS GIS Cut Line= 3
      2038782.96     13447544.41      2038521.05     13447997.11
      2038494.56     13448325.83
#Sta/Elev= 30
  4558.8  391.04  4629.6  390.44  4764.7  391.10  4813.7  390.74  4871.4  391.64
  4886.5  391.38  4902.2  389.49  4908.0  390.94  4923.8  388.09  4929.6  389.18
  4939.5  387.69  4945.3  388.98  4961.1  385.69  4966.9  386.73  4988.4  385.21
  5006.0  382.90  5006.7  382.10  5013.5  382.10  5014.2  382.90  5033.2  383.70
  5041.4  385.81  5047.2  385.41  5063.0  389.43  5068.8  388.90  5077.7  390.17
  5129.9  387.84  5222.3  386.95  5310.4  388.53  5370.6  390.64  5411.6  389.60
#Mann=4,-1,0
  4558.8    0.05       0  4764.7     0.1       0  5006.0    0.07       0
  5014.2     0.1       0
Bank Sta=5006,5014.2
Exp/Cntr=0.3,0.1

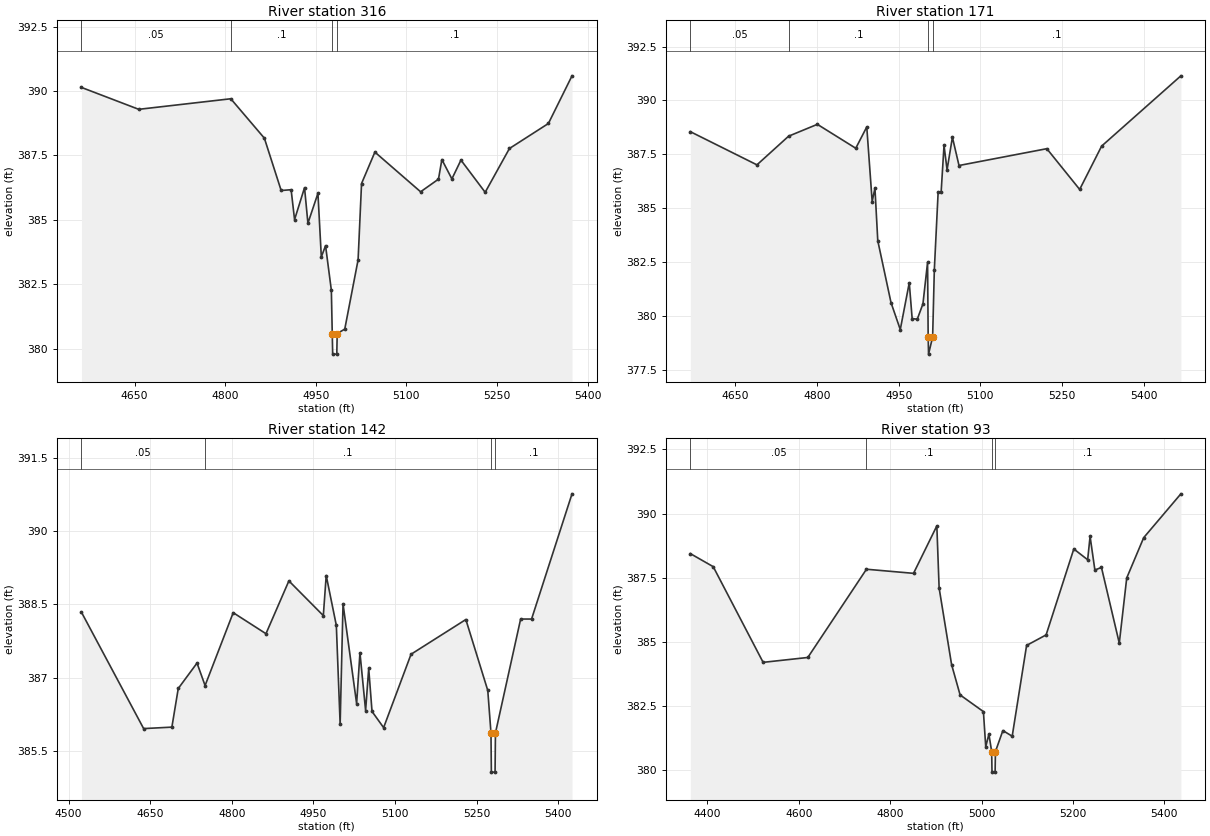
Type RM Length L Ch R = 1,316,145,145,145
BEGIN DESCRIPTION:
Mapping XS 35385b64
END DESCRIPTION:
XS GIS Cut Line= 4
      2038717.86     13447433.73      2038524.71     13447631.22
      2038366.29     13447939.38      2038383.65     13448128.15
#Sta/Elev= 30
  4561.9  390.14  4656.8  389.29  4809.2  389.70  4864.8  388.17  4892.6  386.14
  4909.1  386.17  4914.8  385.01  4931.3  386.25  4936.9  384.87  4953.5  386.03
  4959.1  383.56  4966.1  384.00  4975.7  382.27  4977.2  380.59  4977.9  379.79
  4984.7  379.79  4985.4  380.59  4997.9  380.76  5020.0  383.45  5025.7  386.41
  5047.8  387.63  5123.5  386.09  5153.1  386.58  5158.7  387.34  5175.3  386.59
  5190.3  387.32  5230.4  386.07  5270.6  387.77  5335.1  388.74  5374.2  390.59
#Mann=4,-1,0
  4561.9    0.05       0  4809.2     0.1       0  4977.2    0.07       0
  4985.4     0.1       0
Bank Sta=4977.2,4985.4
Exp/Cntr=0.3,0.1

Type RM Length L Ch R = 1,171,29,29,29
BEGIN DESCRIPTION:
Mapping XS 92ff63ae
END DESCRIPTION:
XS GIS Cut Line= 6
      2038588.50     13447459.29      2038315.96     13447579.07
      2038307.28     13447638.10      2038359.37     13447778.72
      2038354.16     13447947.13      2038381.93     13448169.34
#Sta/Elev= 30
  4567.5  388.55  4689.8  387.01  4747.9  388.34  4800.7  388.89  4871.2  387.78
  4891.4  388.77  4901.3  385.31  4906.4  385.93  4911.6  383.49  4935.9  380.62
  4952.9  379.37  4969.4  381.54  4974.7  379.88  4984.1  379.85  4994.5  380.56
  5003.0  382.49  5004.1  379.03  5004.8  378.23  5012.3  379.03  5015.4  382.13
  5022.4  385.74  5027.9  385.74  5033.2  387.91  5038.8  386.78  5048.6  388.29
  5060.7  386.98  5221.9  387.76  5282.2  385.87  5322.5  387.88  5468.0  391.14
#Mann=4,-1,0
  4567.5    0.05       0  4747.9     0.1       0  5004.1    0.07       0
  5012.3     0.1       0
Bank Sta=5004.1,5012.3
Exp/Cntr=0.3,0.1

Type RM Length L Ch R = 1,142,49,49,49
BEGIN DESCRIPTION:
Mapping XS 7d6de42d
END DESCRIPTION:
XS GIS Cut Line= 6
      2038585.29     13447444.15      2038327.00     13447514.69
      2038284.68     13447619.94      2038284.68     13447669.85
      2038328.09     13447774.02      2038370.14     13448128.76
#Sta/Elev= 30
  4523.7  388.34  4638.0  385.96  4689.9  385.99  4701.6  386.78  4736.1  387.30
  4750.9  386.84  4802.6  388.33  4862.8  387.90  4904.9  388.98  4968.2  388.27
  4973.5  389.09  4992.1  388.07  4999.1  386.05  5004.4  388.51  5029.4  386.47
  5035.5  387.51  5045.9  386.33  5051.6  387.19  5057.7  386.31  5079.0  385.98
  5129.4  387.48  5230.1  388.19  5270.4  386.74  5276.3  385.87  5277.0  385.07
  5283.8  385.07  5284.5  385.87  5330.8  388.20  5350.9  388.20  5425.2  390.76
#Mann=4,-1,0
  4523.7    0.05       0  4750.9     0.1       0  5276.3    0.07       0
  5284.5     0.1       0
Bank Sta=5276.3,5284.5
Exp/Cntr=0.3,0.1

Type RM Length L Ch R = 1,93,0,0,0
BEGIN DESCRIPTION:
UNT 044 in RCW 1.0
END DESCRIPTION:
XS GIS Cut Line= 4
      2038650.62     13447312.19      2038301.19     13447470.63
      2038236.09     13447796.15      2038361.47     13448131.22
#Sta/Elev= 30
  4362.7  388.44  4412.8  387.93  4522.0  384.20  4619.8  384.39  4748.1  387.83
  4851.1  387.67  4902.1  389.52  4907.1  387.10  4934.4  384.11  4953.0  382.93
  5004.0  382.28  5009.1  380.91  5016.0  381.40  5022.1  380.72  5022.8  379.92
  5029.6  379.92  5030.3  380.72  5046.6  381.54  5067.0  381.32  5098.5  384.86
  5141.2  385.27  5201.8  388.62  5232.1  388.20  5237.4  389.11  5247.9  387.80
  5262.3  387.90  5301.3  384.95  5317.6  387.49  5354.7  389.06  5436.1  390.77
#Mann=4,-1,0
  4362.7    0.05       0  4748.1     0.1       0  5022.1    0.07       0
  5030.3     0.1       0
Bank Sta=5022.1,5030.3
Exp/Cntr=0.3,0.1

Chan Stop Cuts=-1