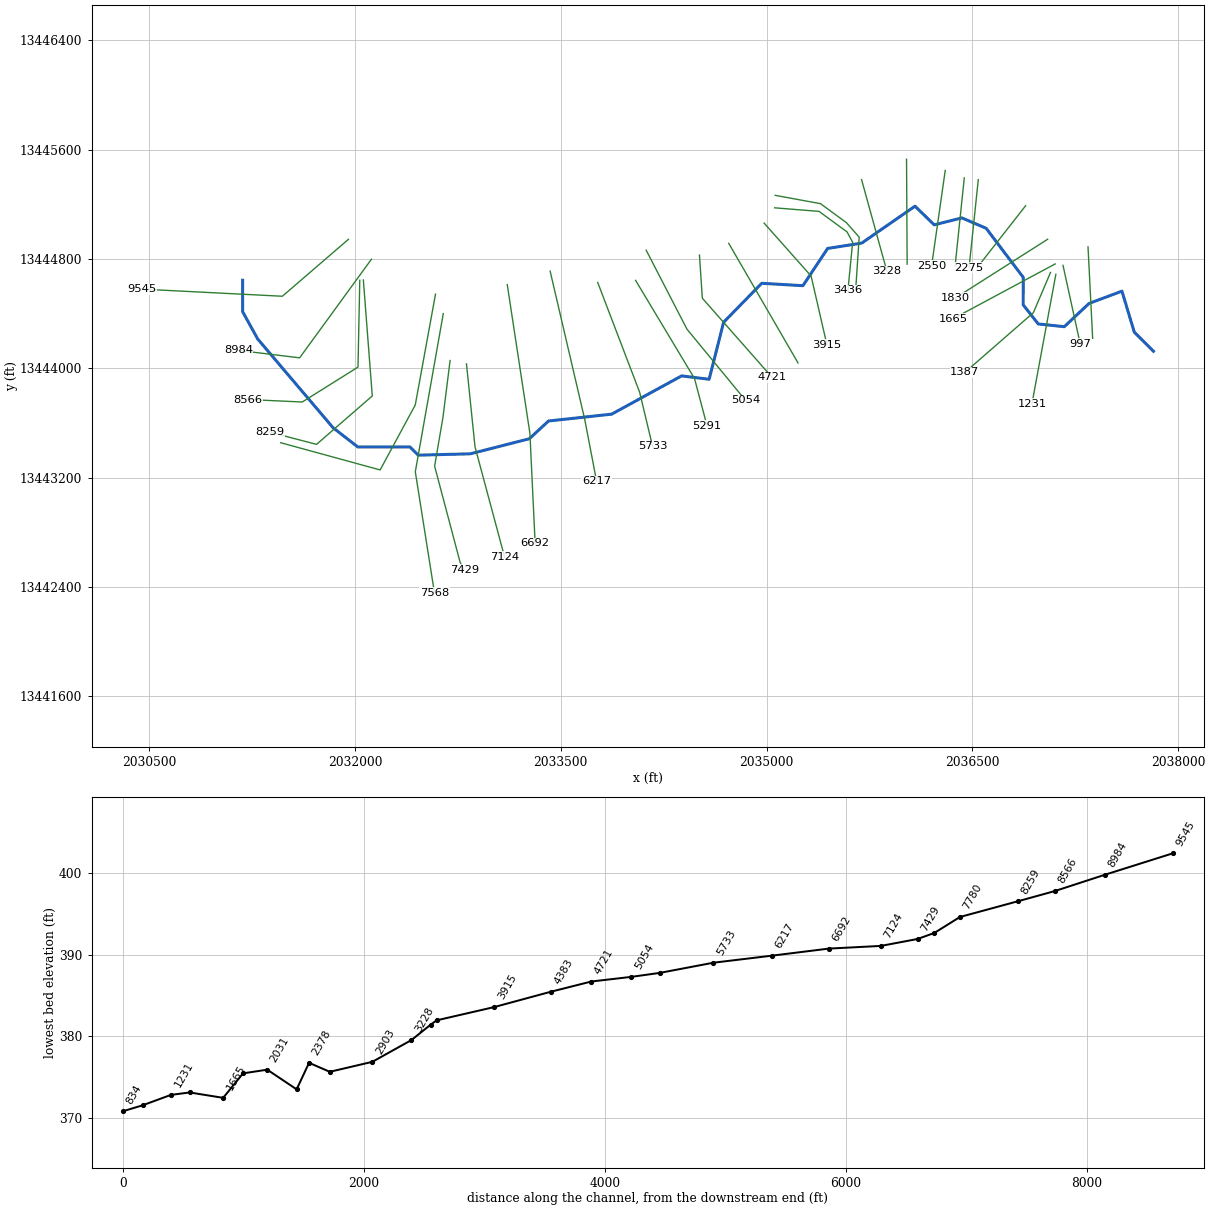
--- UNT 045 in RCW.prj (project) ---

Proj Title=UNT 045 in RCW Base Level Engineering
Current Plan=p01
Default Exp/Contr=0.3,0.1
English Units
Geom File=g01
Flow File=f01
Plan File=p01
Y Axis Title=Elevation
X Axis Title(PF)=Main Channel Distance
X Axis Title(XS)=Station
BEGIN DESCRIPTION:
UNT 045 in RCW
END DESCRIPTION:
DSS Export Rating Curves= 0
DSS Export Rating Curve Sorted= 0
DSS Export Volume Flow Curves= 0
DXF OffsetX= 0
DXF OffsetY= 0
DXF ScaleX= 1
DXF ScaleY= 10

--- UNT 045 in RCW.p01 (plan) ---

Plan Title=Multiple Run
Short Identifier=Multiple
Geom File=g01
Flow File=f01
Subcritical Flow
K Sum by GR= 0
Std Step Tol= 0.01
Critical Tol= 0.01
Num of Std Step Trials= 20
Max Error Tol= 0.3
Flow Tol Ratio= 0.001
Split Flow NTrial= 30
Split Flow Tol= 0.02
Split Flow Ratio= 0.02
Log Output Level= 0
Friction Slope Method= 1
Unsteady Friction Slope Method= 2
Unsteady Bridges Friction Slope Method= 1
Parabolic Critical Depth
Global Vel Dist=  1 , 1 , 1
Global Log Level= 0
CheckData=True
Encroach Param= -1, 0, 0, 0
BEGIN DESCRIPTION:
Multiple Run
END DESCRIPTION:

--- UNT 045 in RCW.f01 (steady flow) ---

Flow Title=Multiple
Program Version=5.05
Number of Profiles= 7
Profile Names=10-year,25-year,50-year,1pct_min,100-year,1pct_plu,500-year
River Rch & RM=UNT 045 in RCW,Reach-1         ,9545
     165     224     271     164     328     654     486
River Rch & RM=UNT 045 in RCW,Reach-1         ,7568
     323     451     558     343     684    1366    1047
River Rch & RM=UNT 045 in RCW,Reach-1         ,5733
     323     451     558     343     684    1366    1047
Boundary for River Rch & Prof#=UNT 045 in RCW,Reach-1         , 1
Up Type= 0
Dn Type= 3
Dn Slope=0.005
Boundary for River Rch & Prof#=UNT 045 in RCW,Reach-1         , 2
Up Type= 0
Dn Type= 3
Dn Slope=0.005
Boundary for River Rch & Prof#=UNT 045 in RCW,Reach-1         , 3
Up Type= 0
Dn Type= 3
Dn Slope=0.005
Boundary for River Rch & Prof#=UNT 045 in RCW,Reach-1         , 4
Up Type= 0
Dn Type= 3
Dn Slope=0.005
Boundary for River Rch & Prof#=UNT 045 in RCW,Reach-1         , 5
Up Type= 0
Dn Type= 3
Dn Slope=0.005
Boundary for River Rch & Prof#=UNT 045 in RCW,Reach-1         , 6
Up Type= 0
Dn Type= 3
Dn Slope=0.005
Boundary for River Rch & Prof#=UNT 045 in RCW,Reach-1         , 7
Up Type= 0
Dn Type= 3
Dn Slope=0.005
DSS Import GetInterval= 0
DSS Import GetPeak= 0
DSS Import FillOption= 0

--- UNT 045 in RCW.g01 (geometry) ---

Geom Title=Existing Conditions
Program Version=5.05

River Reach=UNT 045 in RCW  ,Reach-1
Reach XY= 30
       2031180.8     13444644.54       2031180.8     13444414.54
       2031290.8     13444214.54       2031840.8     13443564.54
       2032020.8     13443424.54       2032400.8     13443424.54
       2032460.8     13443364.54       2032840.8     13443374.54
       2033270.8     13443484.54       2033410.8     13443614.54
       2033870.8     13443664.54       2034380.8     13443944.54
      2034581.67     13443919.92      2034686.92     13444336.59
       2034964.7     13444621.96      2035265.26     13444604.54
      2035445.38     13444876.96      2035693.87     13444916.02
      2036082.32      13445186.2      2036222.29     13445049.48
      2036424.12     13445100.48       2036600.8     13445024.54
      2036871.17     13444665.37       2036870.8     13444464.54
       2036980.8     13444324.54       2037170.8     13444304.54
       2037350.8     13444474.54       2037590.8     13444564.54
       2037680.8     13444264.54       2037820.8     13444124.54

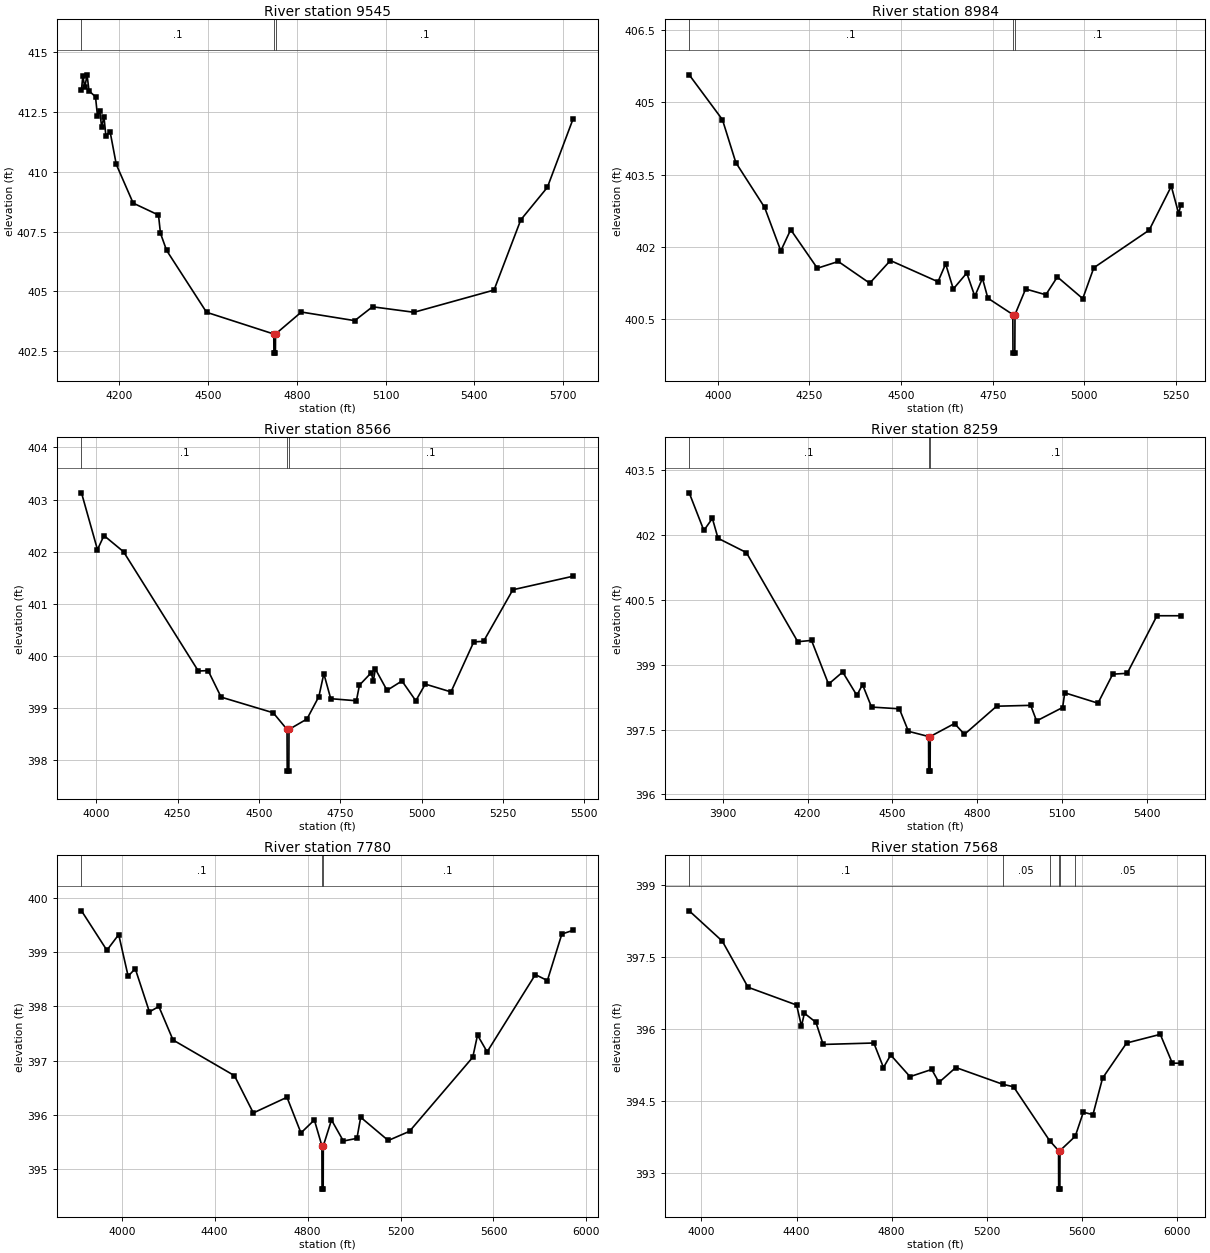
Type RM Length L Ch R = 1 ,9545    ,561,561,561
BEGIN DESCRIPTION:
UNT 045 in RCW 8.0
END DESCRIPTION:
XS GIS Cut Line= 3
      2031952.35     13444943.87       2031470.6     13444527.23
      2030448.14     13444579.22
#Sta/Elev= 30
  4072.9  413.44  4077.4  414.02    4084  413.53  4091.7  414.06  4098.3  413.39
  4120.2  413.14  4126.8  412.35  4134.4  412.56    4141  411.87  4148.7  412.31
  4155.3  411.51  4169.5  411.68  4190.4  410.31  4247.4  408.69    4333  408.19
  4339.6  407.43  4360.4  406.71  4495.3  404.12  4722.4  403.21  4722.9  402.41
  4727.9  402.41  4728.4  403.21  4815.6  404.13  4995.8  403.77  5055.9  404.35
  5196.1  404.12  5466.4  405.05  5556.8  407.99  5646.6  409.35  5733.6  412.22
#Mann= 3 ,-1 , 0
  4072.9      .1       0  4722.4     .07       0  4728.4      .1       0
Bank Sta=4722.4,4728.4
XS Rating Curve= 0 ,0
Exp/Cntr=0.3,0.1

Type RM Length L Ch R = 1 ,8984    ,418,418,418
BEGIN DESCRIPTION:
Mapping XS 6560e7ea
END DESCRIPTION:
XS GIS Cut Line= 3
       2032119.9     13444798.06      2031596.47     13444076.71
      2031149.24     13444131.31
#Sta/Elev= 30
  3921.7  405.57  4012.4  404.64    4049  403.75  4127.6  402.82  4171.7  401.92
  4198.7  402.36  4271.4  401.56  4328.6   401.7  4414.4  401.25  4470.8  401.72
  4600.7  401.28  4621.6  401.65  4642.5  401.13  4679.2  401.46  4701.2  400.98
  4722.1  401.35  4736.8  400.94  4804.9   400.6  4805.4   399.8  4810.4   399.8
  4810.9   400.6  4839.9  401.13    4895  401.01  4926.5  401.38  4995.8  400.93
    5026  401.57  5177.1  402.35  5237.5  403.26  5257.7  402.69  5263.5  402.88
#Mann= 3 ,-1 , 0
  3921.7      .1       0  4804.9     .07       0  4810.9      .1       0
Bank Sta=4804.9,4810.9
XS Rating Curve= 0 ,0
Exp/Cntr=0.3,0.1

Type RM Length L Ch R = 1 ,8566    ,307,307,307
BEGIN DESCRIPTION:
Mapping XS abef13db
END DESCRIPTION:
XS GIS Cut Line= 4
      2032034.86     13444644.13      2032021.84     13444008.73
      2031615.59     13443753.52       2031219.9     13443771.74
#Sta/Elev= 30
  3954.5  403.13  4003.6  402.04  4023.6  402.31  4083.7     402  4313.7  399.71
  4343.7  399.72  4383.7  399.21  4543.8  398.91  4586.4  398.59  4586.9  397.79
  4591.9  397.79  4592.4  398.59  4647.6  398.79  4684.2  399.22  4699.5  399.66
  4720.7  399.18  4799.6  399.14    4809  399.44  4845.5  399.68  4851.4  399.51
  4857.9  399.75  4893.8  399.34  4939.7  399.52  4982.2  399.14  5011.4  399.46
  5090.4  399.31  5160.5  400.27  5190.5  400.28  5280.6  401.27  5465.9  401.53
#Mann= 3 ,-1 , 0
  3954.5      .1       0  4586.4     .07       0  4592.4      .1       0
Bank Sta=4586.4,4592.4
XS Rating Curve= 0 ,0
Exp/Cntr=0.3,0.1

Type RM Length L Ch R = 1 ,8259    ,479,479,479
BEGIN DESCRIPTION:
Mapping XS bf89c30c
END DESCRIPTION:
XS GIS Cut Line= 4
       2032060.9     13444646.73        2032126.     13443797.79
      2031719.75     13443443.62      2031381.23     13443532.16
#Sta/Elev= 30
  3781.1  402.97    3833   402.1  3863.1  402.38  3883.1  401.92  3983.4  401.59
  4165.3  399.53  4214.1  399.56  4274.3  398.55  4324.4  398.83  4374.6  398.29
  4394.6  398.54  4426.5  398.02    4525  397.98  4557.1  397.46  4628.4  397.34
  4628.9  396.54  4633.9  396.54  4634.4  397.34  4720.3  397.64  4755.4  397.39
  4869.3  398.04  4989.9  398.06  5010.8   397.7  5102.9  398.01  5110.5  398.35
  5228.1  398.11  5280.3  398.78  5331.5   398.8  5436.9  400.13  5521.4  400.13
#Mann= 3 ,-1 , 0
  3781.1      .1       0  4628.4     .07       0  4634.4      .1       0
Bank Sta=4628.4,4634.4
XS Rating Curve= 0 ,0
Exp/Cntr=0.3,0.1

Type RM Length L Ch R = 1 ,7780    ,212,212,212
BEGIN DESCRIPTION:
Mapping XS 0fc62245
END DESCRIPTION:
XS GIS Cut Line= 4
      2032586.94     13444542.55      2032439.37     13443731.82
       2032183.3     13443256.55      2031458.16      13443455.7
#Sta/Elev= 30
  3826.9  399.77  3936.2  399.04    3987  399.33  4027.7  398.56  4058.2   398.7
  4119.2   397.9  4159.8     398  4220.8  397.38  4485.1  396.72  4566.4  396.03
  4711.3  396.32  4771.4  395.66  4829.1   395.9  4861.6  395.42  4862.1  394.62
  4867.1  394.62  4867.6  395.42  4902.8   395.9    4954  395.51  5012.3  395.56
  5028.5  395.95  5147.1  395.52  5238.6  395.69  5510.8  397.06  5531.3  397.47
  5572.7  397.16  5780.2  398.59    5832  398.48  5894.2  399.34  5942.8  399.41
#Mann= 3 ,-1 , 0
  3826.9      .1       0  4861.6     .07       0  4867.6      .1       0
Bank Sta=4861.6,4867.6
XS Rating Curve= 0 ,0
Exp/Cntr=0.3,0.1

Type RM Length L Ch R = 1 ,7568    ,139,139,139
BEGIN DESCRIPTION:
Mapping XS 247dc7df
END DESCRIPTION:
XS GIS Cut Line= 3
       2032643.6     13444400.29      2032439.72     13443242.83
      2032578.82      13442359.6
#Sta/Elev= 30
  3948.3  398.46  4087.5  397.83    4196  396.87  4400.4   396.5  4420.8  396.06
  4433.1  396.33  4481.7  396.14  4512.1  395.68  4725.4  395.71    4766   395.2
  4796.5  395.46  4877.7  395.01  4969.1  395.16  4999.5  394.89  5070.6   395.2
  5268.9  394.85  5313.5   394.8  5465.2  393.68    5503  393.47  5503.5  392.67
  5508.5  392.67    5509  393.47  5573.3  393.77  5607.3  394.27  5647.8  394.22
  5688.3  394.98  5789.5  395.71  5931.2  395.89  5981.9  395.29  6017.7  395.29
#Mann= 6 ,-1 , 0
  3948.3      .1       0  5268.9     .05       0  5465.2      .1       0
    5503     .07       0    5509      .1       0  5573.3     .05       0
Bank Sta=5503,5509
XS Rating Curve= 0 ,0
Exp/Cntr=0.3,0.1

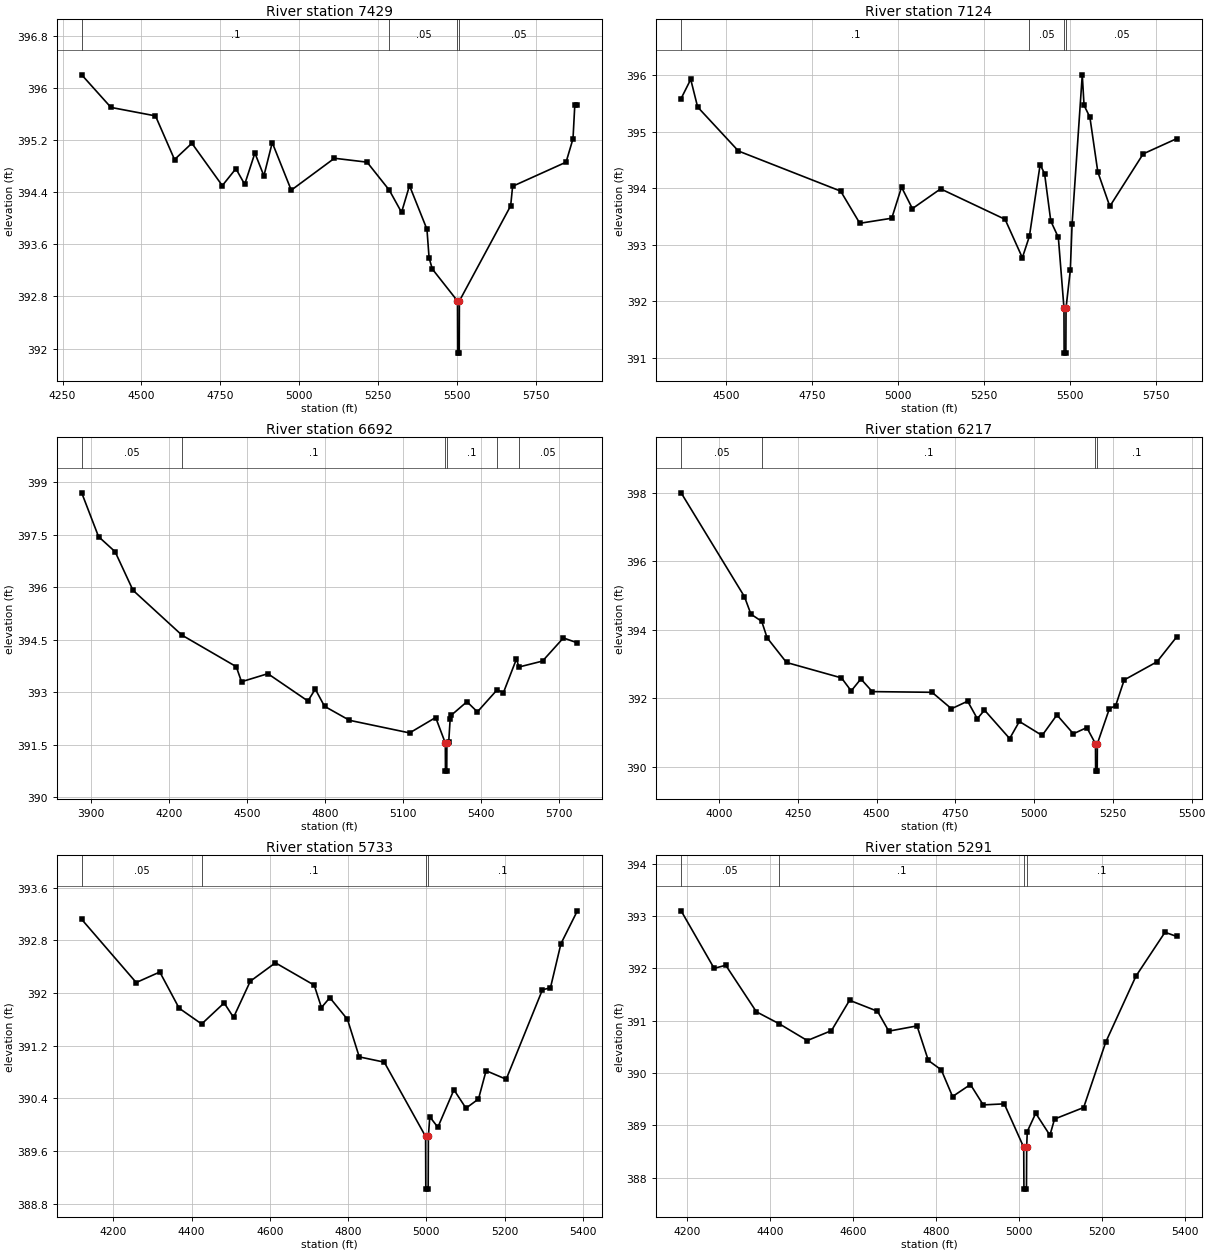
Type RM Length L Ch R = 1 ,7429    ,305,305,305
BEGIN DESCRIPTION:
Mapping XS 73bd670c
END DESCRIPTION:
XS GIS Cut Line= 5
      2032693.25     13444056.95      2032641.17     13443640.32
      2032580.41     13443284.42      2032766.18     13442580.97
      2032795.46     13442525.85
#Sta/Elev= 30
  4310.5   396.2  4403.2   395.7  4544.3  395.57  4604.7   394.9  4659.7  395.15
  4756.1   394.5  4799.2  394.76  4827.1  394.52  4859.4     395  4887.9  394.65
  4914.4  395.16  4974.6  394.43  5111.5  394.92  5214.9  394.86  5285.4  394.43
  5324.2  394.09  5349.4   394.5  5404.7  393.83  5411.5  393.39  5421.8  393.22
  5501.5  392.73    5502  391.93    5507  391.93  5507.5  392.73    5670  394.19
  5676.2  394.49  5845.6  394.86  5867.6  395.22  5873.2  395.73  5881.4  395.73
#Mann= 4 ,-1 , 0
  4310.5      .1       0  5285.4     .05       0  5501.5     .07       0
  5507.5     .05       0
Bank Sta=5501.5,5507.5
XS Rating Curve= 0 ,0
Exp/Cntr=0.3,0.1

Type RM Length L Ch R = 1 ,7124    ,432,432,432
BEGIN DESCRIPTION:
UNT 045 in RCW 7.0
END DESCRIPTION:
XS GIS Cut Line= 3
      2032812.62     13444032.83        2032875.       13443425.
      2033090.15     13442620.49
#Sta/Elev= 30
  4367.8  395.59  4395.8  395.93  4415.9  395.44  4534.8  394.66  4832.5  393.95
  4888.3  393.38  4981.4  393.47  5009.9  394.02  5041.5  393.64  5123.7  393.99
  5311.5  393.45  5361.8  392.77  5382.3  393.15  5413.6  394.42  5426.5  394.26
  5444.6  393.42  5466.6  393.13    5483  391.88  5483.5  391.08  5488.5  391.08
    5489  391.88  5501.5  392.55  5506.7  393.37  5536.3  396.01  5541.5  395.47
  5558.5  395.26  5581.6  394.29  5616.5  393.68  5713.8  394.61  5811.6  394.88
#Mann= 4 ,-1 , 0
  4367.8      .1       0  5382.3     .05       0    5483     .07       0
    5489     .05       0
Bank Sta=5483,5489
XS Rating Curve= 0 ,0
Exp/Cntr=0.3,0.1

Type RM Length L Ch R = 1 ,6692    ,475,475,475
BEGIN DESCRIPTION:
UNT 045 in RCW 6.0
END DESCRIPTION:
XS GIS Cut Line= 3
        2033110.     13444611.99        2033275.       13443525.
      2033313.13     13442721.35
#Sta/Elev= 30
  3865.9  398.69  3930.6  397.44  3994.2  397.01  4062.9  395.91  4250.9  394.63
  4459.6  393.73  4479.8   393.3    4581  393.53  4734.9  392.75  4763.1  393.09
  4798.6   392.6  4894.5   392.2  5125.5  391.84  5225.6  392.28  5262.7  391.55
  5263.2  390.75  5268.2  390.75  5268.7  391.55  5275.7  391.58  5281.3  392.24
  5286.3  392.35  5345.8  392.73  5385.8  392.44  5461.7  393.07  5485.9  392.99
    5536  393.95  5545.3  393.72  5636.1  393.89  5716.2  394.55  5769.9  394.41
#Mann= 6 ,-1 , 0
  3865.9     .05       0  4250.9      .1       0  5262.7     .07       0
  5268.7      .1       0  5461.7     .08       0  5545.3     .05       0
Bank Sta=5262.7,5268.7
XS Rating Curve= 0 ,0
Exp/Cntr=0.3,0.1

Type RM Length L Ch R = 1 ,6217    ,484,484,484
BEGIN DESCRIPTION:
UNT 045 in RCW 5.0
END DESCRIPTION:
XS GIS Cut Line= 3
      2033422.52     13444710.86        2033675.       13443625.
      2033761.05     13443174.47
#Sta/Elev= 30
  3879.3     398  4080.4  394.97  4100.9  394.46  4135.2  394.25  4152.3  393.77
  4213.9  393.05  4388.4   392.6  4419.2  392.22    4450  392.57  4486.1   392.2
  4675.9  392.18  4737.5   391.7  4788.8  391.92  4819.6  391.41  4842.4  391.66
  4922.3  390.83  4953.1  391.33  5025.3  390.92  5072.3  391.52  5124.4  390.97
  5167.2  391.15  5194.7  390.68  5195.2  389.88  5200.2  389.88  5200.7  390.68
  5238.8   391.7  5258.8  391.79  5285.8  392.54    5390  393.07  5452.8   393.8
#Mann= 4 ,-1 , 0
  3879.3     .05       0  4135.2      .1       0  5194.7     .07       0
  5200.7      .1       0
Bank Sta=5194.7,5200.7
XS Rating Curve= 0 ,0
Exp/Cntr=0.3,0.1

Type RM Length L Ch R = 1 ,5733    ,442,442,442
BEGIN DESCRIPTION:
UNT 045 in RCW 4.0
END DESCRIPTION:
XS GIS Cut Line= 3
      2033769.47     13444627.72        2034075.       13443825.
      2034169.45     13443428.08
#Sta/Elev= 30
  4119.3  393.12  4258.6  392.16  4318.9  392.32  4368.3  391.77  4425.9  391.53
  4483.4  391.85  4507.4  391.63  4550.2  392.18  4614.4  392.46  4713.6  392.12
  4732.1  391.78  4753.5  391.93  4798.6   391.6  4828.7  391.03  4892.6  390.95
  4998.3  389.82  4998.8  389.02  5004.9  389.02  5005.4  389.82    5009  390.12
  5029.6  389.96  5070.7  390.53  5101.5  390.25  5133.5  390.39  5152.9  390.82
  5204.3  390.69  5296.9  392.05  5317.4  392.08  5344.2  392.75  5386.2  393.25
#Mann= 4 ,-1 , 0
  4119.3     .05       0  4425.9      .1       0  4998.3     .07       0
  5005.4      .1       0
Bank Sta=4998.3,5005.4
XS Rating Curve= 0 ,0
Exp/Cntr=0.3,0.1

Type RM Length L Ch R = 1 ,5291    ,237,237,237
BEGIN DESCRIPTION:
UNT 045 in RCW 3.0
END DESCRIPTION:
XS GIS Cut Line= 3
       2034045.5     13444643.36        2034475.       13443925.
      2034566.47     13443579.47
#Sta/Elev= 30
  4185.8   393.1  4265.4     392  4293.3  392.06  4367.2  391.17  4422.4  390.94
  4489.8  390.62  4548.1  390.81  4591.7  391.39    4659  391.18  4686.2   390.8
  4754.3   390.9  4781.5  390.24  4812.7  390.06  4839.9  389.55    4883  389.78
  4913.8  389.39  4964.5  389.41  5011.4  388.58  5011.9  387.78    5018  387.78
  5018.5  388.58  5019.9  388.88  5040.3  389.23  5074.5  388.81  5085.7  389.12
  5155.8  389.34    5209  390.59  5281.7  391.85  5351.8  392.69  5380.2  392.61
#Mann= 4 ,-1 , 0
  4185.8     .05       0  4422.4      .1       0  5011.4     .07       0
  5018.5      .1       0
Bank Sta=5011.4,5018.5
XS Rating Curve= 0 ,0
Exp/Cntr=0.3,0.1

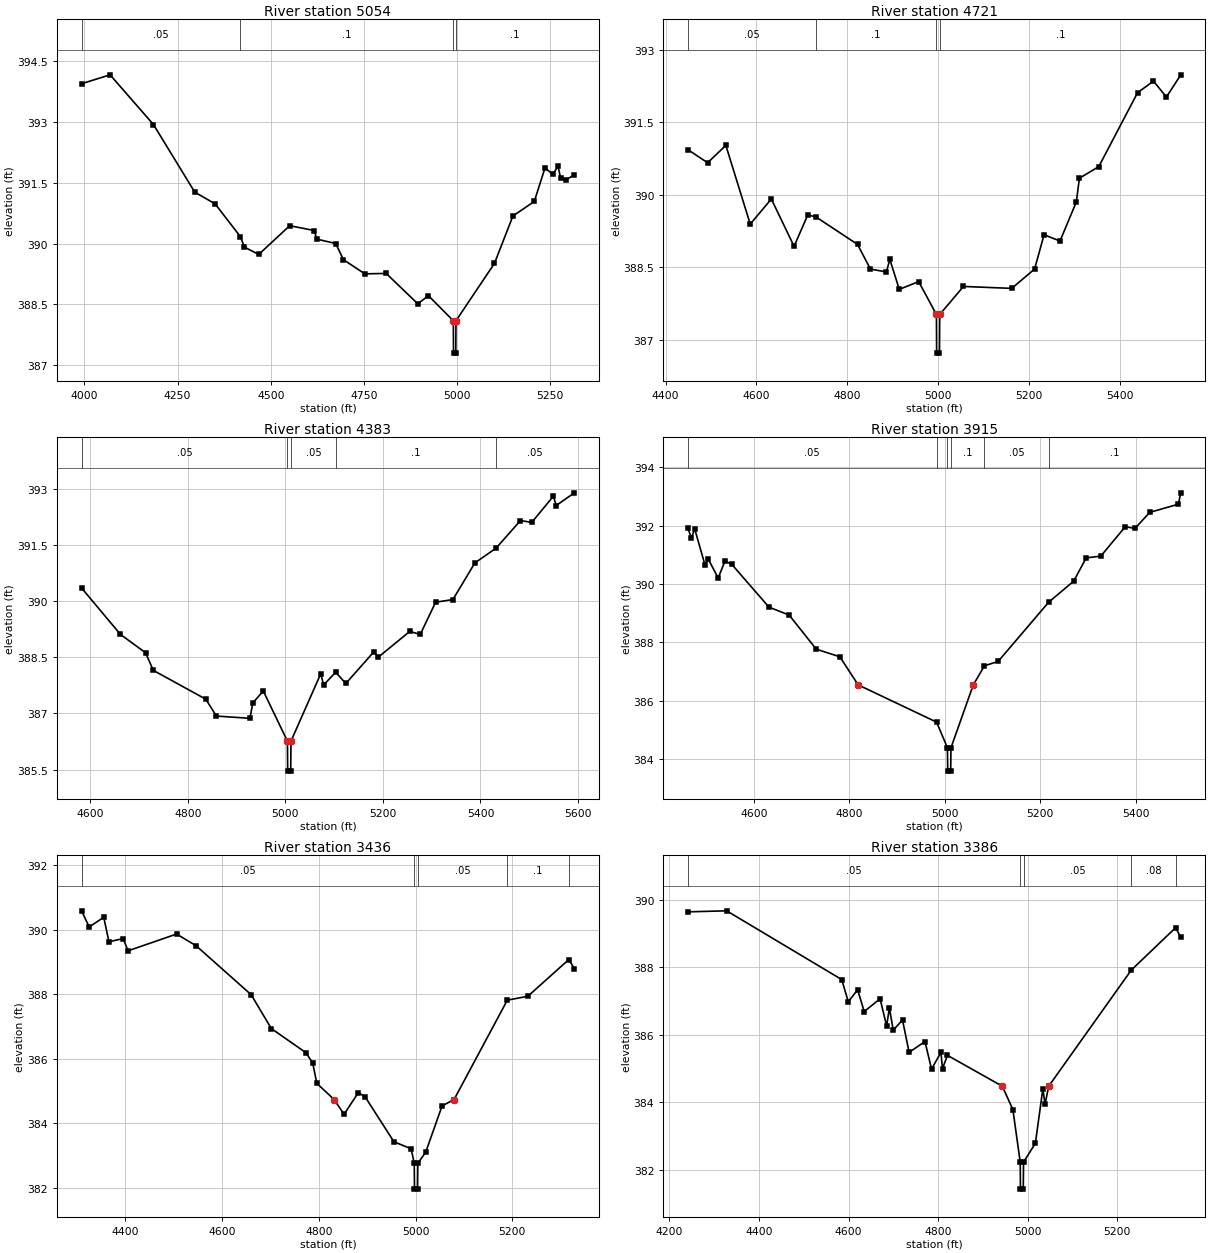
Type RM Length L Ch R = 1 ,5054    ,333,333,333
BEGIN DESCRIPTION:
Mapping XS 31471b58
END DESCRIPTION:
XS GIS Cut Line= 3
      2034122.77     13444863.84      2034419.91     13444286.43
      2034846.97     13443765.62
#Sta/Elev= 30
  3992.1  393.95  4068.7  394.17  4185.2  392.94    4296  391.27  4350.7  390.98
  4418.5  390.17  4429.4  389.91  4467.8  389.73  4550.9  390.44  4617.4  390.32
    4623  390.11  4674.4     390  4695.2   389.6  4752.6  389.25    4810  389.26
  4894.7  388.51  4923.4  388.71  4990.2  388.09  4990.7  387.29  4996.8  387.29
  4997.3  388.09  5100.7  389.51  5150.2  390.68  5207.6  391.04  5236.3  391.87
  5257.2  391.71  5271.5  391.91    5278  391.62  5292.3  391.57    5315   391.7
#Mann= 4 ,-1 , 0
  3992.1     .05       0  4418.5      .1       0  4990.2     .07       0
  4997.3      .1       0
Bank Sta=4990.2,4997.3
XS Rating Curve= 0 ,0
Exp/Cntr=0.3,0.1

Type RM Length L Ch R = 1 ,4721    ,338,338,338
BEGIN DESCRIPTION:
Mapping XS 92b301f5
END DESCRIPTION:
XS GIS Cut Line= 3
      2034511.05     13444828.11      2034531.88     13444512.99
       2035039.7     13443934.86
#Sta/Elev= 30
  4449.3  390.93  4492.5  390.66  4532.6  391.02  4586.3  389.39  4632.8  389.91
  4682.9  388.93    4713  389.58  4730.9  389.54  4822.6  388.97  4851.1  388.46
  4886.2   388.4  4893.8  388.66  4914.6  388.04  4957.3   388.2  4996.4  387.52
  4996.9  386.72  5003.1  386.72  5003.7  387.52    5056   388.1  5162.3  388.06
  5212.6  388.46  5233.5  389.17  5268.6  389.04  5304.6  389.85  5311.3  390.34
    5354  390.58  5439.4  392.11  5474.5  392.35  5502.9  392.02  5534.6  392.48
#Mann= 4 ,-1 , 0
  4449.3     .05       0  4730.9      .1       0  4996.4     .07       0
  5003.7      .1       0
Bank Sta=4996.4,5003.7
XS Rating Curve= 0 ,0
Exp/Cntr=0.3,0.1

Type RM Length L Ch R = 1 ,4383    ,468,468,468
BEGIN DESCRIPTION:
Mapping XS 9dfda5f9
END DESCRIPTION:
XS GIS Cut Line= 2
      2034724.61       13444914.      2035229.53      13444039.5
#Sta/Elev= 30
  4582.5  390.35  4662.2  389.11  4713.7  388.62  4729.5  388.15  4837.2  387.38
  4858.8  386.93  4927.6  386.87  4933.4  387.28  4954.9   387.6  5004.4  386.26
  5004.9  385.46  5011.1  385.46  5011.7  386.26  5072.7  388.06  5078.5  387.76
  5103.3   388.1  5124.1   387.8  5181.8  388.65  5190.4   388.5  5255.1  389.19
  5276.6  389.11  5308.1  389.97  5343.5  390.04  5388.6  391.02  5431.7  391.41
    5482  392.15  5505.1   392.1  5549.4   392.8  5555.2  392.55  5592.3  392.89
#Mann= 5 ,-1 , 0
  4582.5     .05       0  5004.4    .035       0  5011.7     .05       0
  5103.3      .1       0  5431.7     .05       0
Bank Sta=5004.4,5011.7
XS Rating Curve= 0 ,0
Exp/Cntr=0.3,0.1

Type RM Length L Ch R = 1 ,3915    ,479,479,479
BEGIN DESCRIPTION:
UNT 045 in RCW 2.0
END DESCRIPTION:
XS GIS Cut Line= 3
      2034982.39     13445062.23        2035325.       13444675.
      2035440.34     13444171.58
#Sta/Elev= 30
  4461.4  391.91  4468.6  391.57  4475.3   391.9  4497.1  390.65  4503.8  390.86
  4524.6  390.21  4538.9  390.79  4553.1  390.68  4631.3  389.21  4673.5  388.94
  4730.4  387.77  4779.8  387.51 4818.28386.5461  4982.7  385.27  5005.5  384.39
  5006.1  383.59  5012.3  383.59  5012.9  384.39 5059.69386.5462  5083.1   387.2
  5111.8  387.35  5217.8  389.38  5270.2   390.1  5296.5   390.9  5327.2  390.96
  5378.5  391.97  5398.9  391.91  5429.8  392.46  5489.8  392.74  5494.9  393.13
#Mann= 6 ,-1 , 0
  4461.4     .05       0  4982.7      .1       0  5005.5     .07       0
  5012.9      .1       0  5083.1     .05       0  5217.8      .1       0
Bank Sta=4818.28,5059.69
XS Rating Curve= 0 ,0
Exp/Cntr=0.3,0.1

Type RM Length L Ch R = 1 ,3436    ,50,50,50
BEGIN DESCRIPTION:
Mapping XS 06a3422b
END DESCRIPTION:
XS GIS Cut Line= 5
       2035059.2     13445174.19      2035382.58     13445148.15
      2035586.57     13444998.41       2035627.8     13444922.45
      2035593.14     13444569.35
#Sta/Elev= 30
  4309.5  390.59  4325.3  390.09  4355.4  390.39  4366.1  389.63  4395.6  389.73
  4405.6  389.35  4505.9  389.87  4546.1  389.51  4660.1  387.99  4701.8  386.94
  4773.4  386.19  4787.4  385.87  4795.9  385.24 4831.64 384.738  4852.2  384.28
  4881.6  384.95  4895.4  384.83  4955.2  383.43  4990.9  383.21  4997.3  382.76
  4997.8  381.96  5004.1  381.96  5004.7  382.76  5021.1  383.11  5054.8  384.54
 5079.61384.7381  5189.7  387.82  5232.1  387.94  5316.9  389.08  5328.2   388.8
#Mann= 5 ,-1 , 0
  4309.5     .05       0  4997.3     .04       0  5004.7     .05       0
  5189.7      .1       0  5316.9     .05       0
Bank Sta=4831.64,5079.61
XS Rating Curve= 0 ,0
Exp/Cntr=0.3,0.1

Type RM Length L Ch R = 1 ,3386    ,158,158,158
BEGIN DESCRIPTION:
Mapping XS 0351512c
END DESCRIPTION:
XS GIS Cut Line= 5
      2035063.58     13445265.33      2035393.43     13445204.57
      2035582.23     13445065.68      2035675.55     13444959.35
      2035649.51     13444570.88
#Sta/Elev= 30
  4241.4  389.65  4327.7  389.68  4584.7  387.64  4599.4  386.98  4620.2  387.34
  4634.9  386.69  4670.4  387.07    4685  386.26  4691.2   386.8  4699.7  386.14
  4720.5  386.44  4735.2  385.48  4770.7   385.8  4785.3  384.98  4806.2  385.48
  4809.8     385  4820.9  385.39 4943.37384.4745    4967  383.78  4983.4  382.22
  4983.9  381.42  4990.2  381.42  4990.8  382.22  5017.2  382.78  5033.9  384.39
  5038.9  383.94 5046.96384.4741  5231.4  387.92  5330.5  389.18    5342  388.89
#Mann= 5 ,-1 , 0
  4241.4     .05       0  4983.4     .04       0  4990.8     .05       0
  5231.4     .08       0  5330.5     .05       0
Bank Sta=4943.37,5046.96
XS Rating Curve= 0 ,0
Exp/Cntr=0.3,0.1

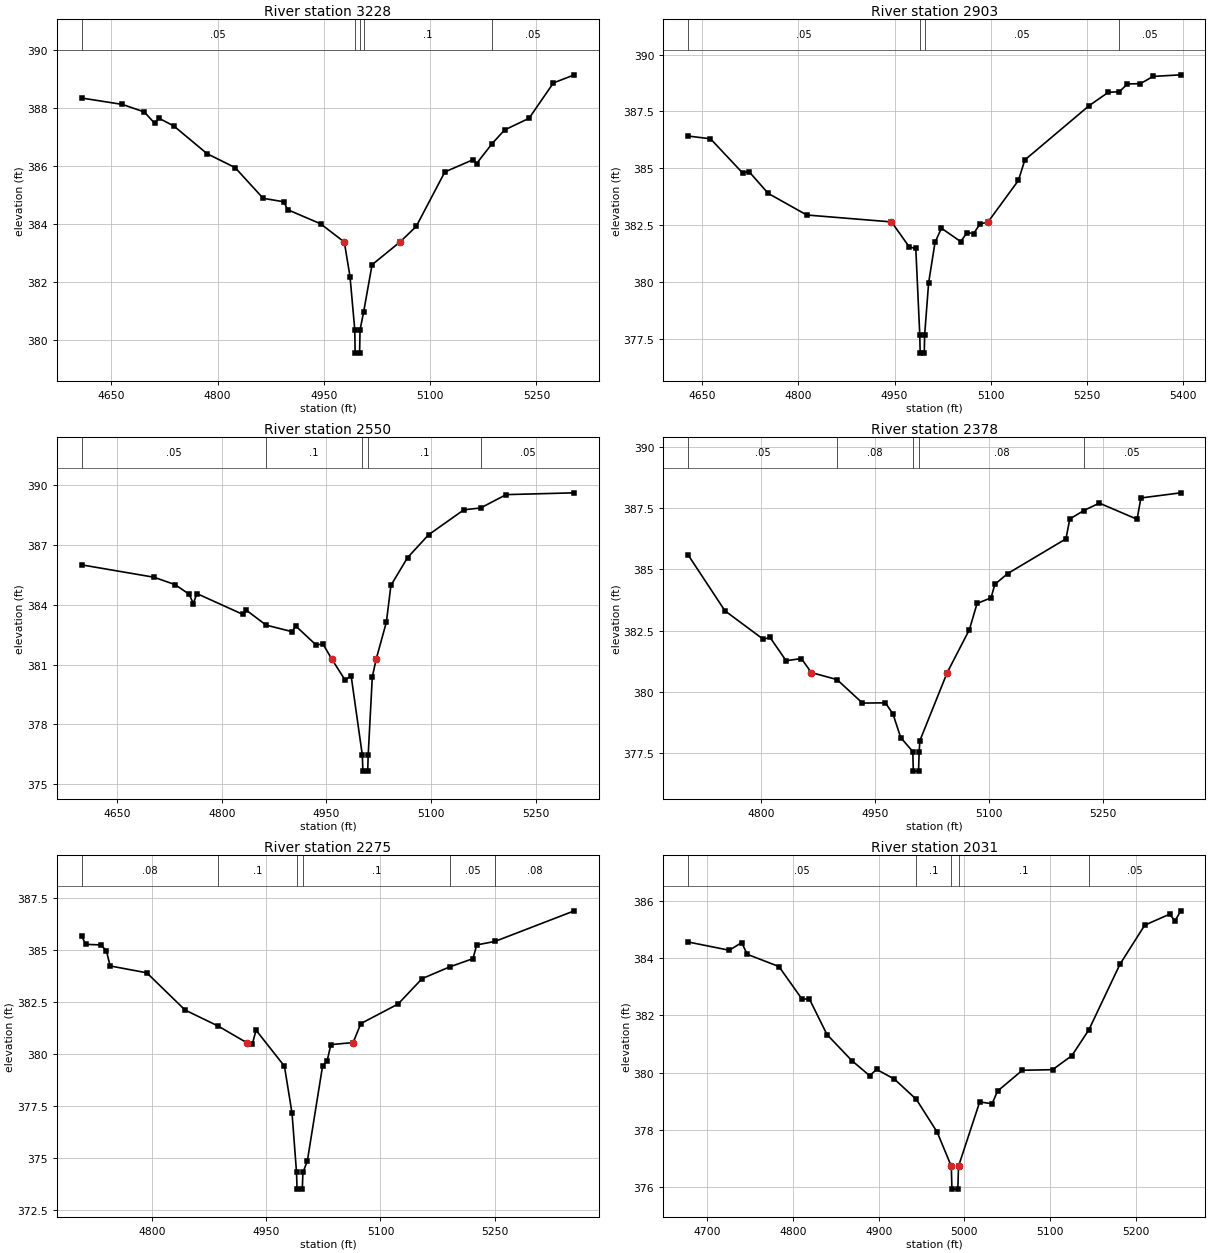
Type RM Length L Ch R = 1 ,3228    ,325,325,325
BEGIN DESCRIPTION:
Mapping XS 164d1dcb
END DESCRIPTION:
XS GIS Cut Line= 2
      2035692.91     13445380.36      2035877.35     13444709.86
#Sta/Elev= 30
    4608  388.35  4665.4  388.13  4696.5  387.87  4711.1  387.48  4717.3  387.65
    4738  387.39  4785.1  386.43  4824.7  385.95  4864.3  384.89  4893.5  384.77
  4898.7   384.5  4945.4  384.01 4978.83383.3815  4986.9  382.18  4993.6  380.35
  4994.1  379.55  5000.4  379.55    5001  380.35    5006  380.96    5018   382.6
  5057.3383.3821  5080.3  383.92  5120.7   385.8  5160.3  386.22  5165.5  386.09
  5187.5  386.78  5205.1  387.25  5239.5  387.65  5273.9  388.87  5303.4  389.15
#Mann= 5 ,-1 , 0
    4608     .05       0  4993.6     .03       0    5001     .05       0
    5006      .1       0  5187.5     .05       0
Bank Sta=4978.83,5057.3
XS Rating Curve= 0 ,0
Exp/Cntr=0.3,0.1

Type RM Length L Ch R = 1 ,2903    ,353,353,353
BEGIN DESCRIPTION:
Mapping XS 15ab1e68
END DESCRIPTION:
XS GIS Cut Line= 2
       2036020.6     13445530.05      2036024.94     13444761.86
#Sta/Elev= 30
  4628.1  386.42  4663.1   386.3  4713.1   384.8  4723.1  384.86  4753.1   383.9
  4813.2  382.95 4945.31382.6461  4973.2  381.54  4983.2  381.48  4989.4  377.68
    4990  376.88  4996.4  376.88    4997  377.68  5003.2  379.97  5013.2  381.75
  5023.2  382.37  5053.2  381.78  5063.2  382.18  5073.2  382.13  5083.2  382.55
 5095.85 382.646  5143.2  384.47  5153.2  385.37  5253.2  387.75  5283.2  388.34
  5300.6  388.37  5313.2  388.71  5333.2  388.72  5353.2  389.04  5396.3  389.11
#Mann= 4 ,-1 , 0
  4628.1     .05       0  4989.4     .07       0    4997     .05       0
  5300.6     .05       0
Bank Sta=4945.31,5095.85
XS Rating Curve= 0 ,0
Exp/Cntr=0.3,0.1

Type RM Length L Ch R = 1 ,2550    ,172,172,172
BEGIN DESCRIPTION:
Mapping XS 6f700b0f
END DESCRIPTION:
XS GIS Cut Line= 2
      2036302.72     13445447.66      2036203.13     13444748.32
#Sta/Elev= 30
  4598.9     386  4702.6  385.38  4732.9  385.01  4753.1  384.53  4759.1  384.06
  4764.2  384.56  4829.9  383.52    4835  383.73  4863.4  382.98  4900.7  382.65
  4905.8  382.94  4934.9  381.99    4945  382.03 4957.63381.2772  4976.6  380.23
  4985.4  380.43  5001.4  376.46  5002.2  375.66  5009.1  375.66  5009.8  376.46
  5015.7  380.38 5021.29381.2766  5035.9  383.13  5042.4  384.97  5066.2  386.36
  5096.5  387.51    5147  388.76  5170.9  388.85  5207.6  389.52  5305.3  389.61
#Mann= 5 ,-1 , 0
  4598.9     .05       0  4863.4      .1       0  5001.4     .07       0
  5009.8      .1       0  5170.9     .05       0
Bank Sta=4957.63,5021.29
XS Rating Curve= 0 ,0
Exp/Cntr=0.3,0.1

Type RM Length L Ch R = 1 ,2378    ,103,103,103
BEGIN DESCRIPTION:
Mapping XS 3fe29867
END DESCRIPTION:
XS GIS Cut Line= 2
      2036441.61     13445393.36      2036374.51     13444748.34
#Sta/Elev= 30
  4703.7   385.6  4752.3  383.31  4802.6  382.15  4811.7  382.22  4832.8  381.27
  4852.9  381.36  4865.9380.7876  4899.8   380.5  4933.3  379.54  4963.5  379.55
  4973.5  379.09  4983.6  378.13  4999.5  377.56  5000.2  376.76  5007.1  376.76
  5007.9  377.56  5008.9  378.01 5044.83380.7874    5074  382.54  5084.1  383.61
  5102.5  383.84  5107.5  384.39  5124.3  384.83  5201.1  386.25  5206.1  387.06
  5224.2   387.4    5245  387.71  5294.7  387.05  5299.7  387.92  5352.2  388.13
#Mann= 5 ,-1 , 0
  4703.7     .05       0  4899.8     .08       0  4999.5     .07       0
  5007.9     .08       0  5224.2     .05       0
Bank Sta=4865.9,5044.83
XS Rating Curve= 0 ,0
Exp/Cntr=0.3,0.1

Type RM Length L Ch R = 1 ,2275    ,244,244,244
BEGIN DESCRIPTION:
Mapping XS e7c22771
END DESCRIPTION:
XS GIS Cut Line= 2
       2036543.6     13445380.33      2036476.33     13444735.83
#Sta/Elev= 30
  4706.9  385.69  4712.3  385.28  4732.4  385.25  4739.5  384.97  4744.5  384.24
  4792.7  383.91    4843  382.12  4886.6  381.35 4923.87380.5546  4931.3  380.47
  4936.4  381.15  4973.7  379.42  4983.7  377.16  4989.6  374.31  4990.3  373.51
  4997.2  373.51    4998  374.31  5003.8  374.86  5023.9  379.44  5029.8  379.67
  5034.8  380.46 5063.98380.5545  5074.2  381.47  5123.2  382.41  5154.7  383.63
  5191.4   384.2  5221.6  384.59  5226.6  385.25  5250.6  385.42  5354.9  386.89
#Mann= 6 ,-1 , 0
  4706.9     .08       0  4886.6      .1       0  4989.6     .07       0
    4998      .1       0  5191.4     .05       0  5250.6     .08       0
Bank Sta=4923.87,5063.98
XS Rating Curve= 0 ,0
Exp/Cntr=0.3,0.1

Type RM Length L Ch R = 1 ,2031    ,201,201,201
BEGIN DESCRIPTION:
Mapping XS a7a62bc3
END DESCRIPTION:
XS GIS Cut Line= 2
      2036888.63     13445189.34      2036534.95     13444735.86
#Sta/Elev= 30
  4677.5  384.57  4725.7  384.28  4740.2  384.55  4746.5  384.14  4783.6  383.71
  4810.8  382.56  4818.9  382.59  4839.7  381.33  4868.6  380.42  4889.5  379.89
  4897.6  380.11  4918.4  379.77    4944  379.06  4968.2  377.92  4984.8  376.72
  4985.5  375.92  4992.4  375.92  4993.2  376.72  5017.9  378.97  5032.4  378.91
  5038.7  379.35  5067.7  380.08  5102.9   380.1  5125.5  380.59  5145.4   381.5
  5181.6  383.79  5210.6  385.16  5239.5  385.54  5245.9  385.31  5252.6  385.66
#Mann= 5 ,-1 , 0
  4677.5     .05       0    4944      .1       0  4984.8     .07       0
  4993.2      .1       0  5145.4     .05       0
Bank Sta=4984.8,4993.2
XS Rating Curve= 0 ,0
Exp/Cntr=0.3,0.1

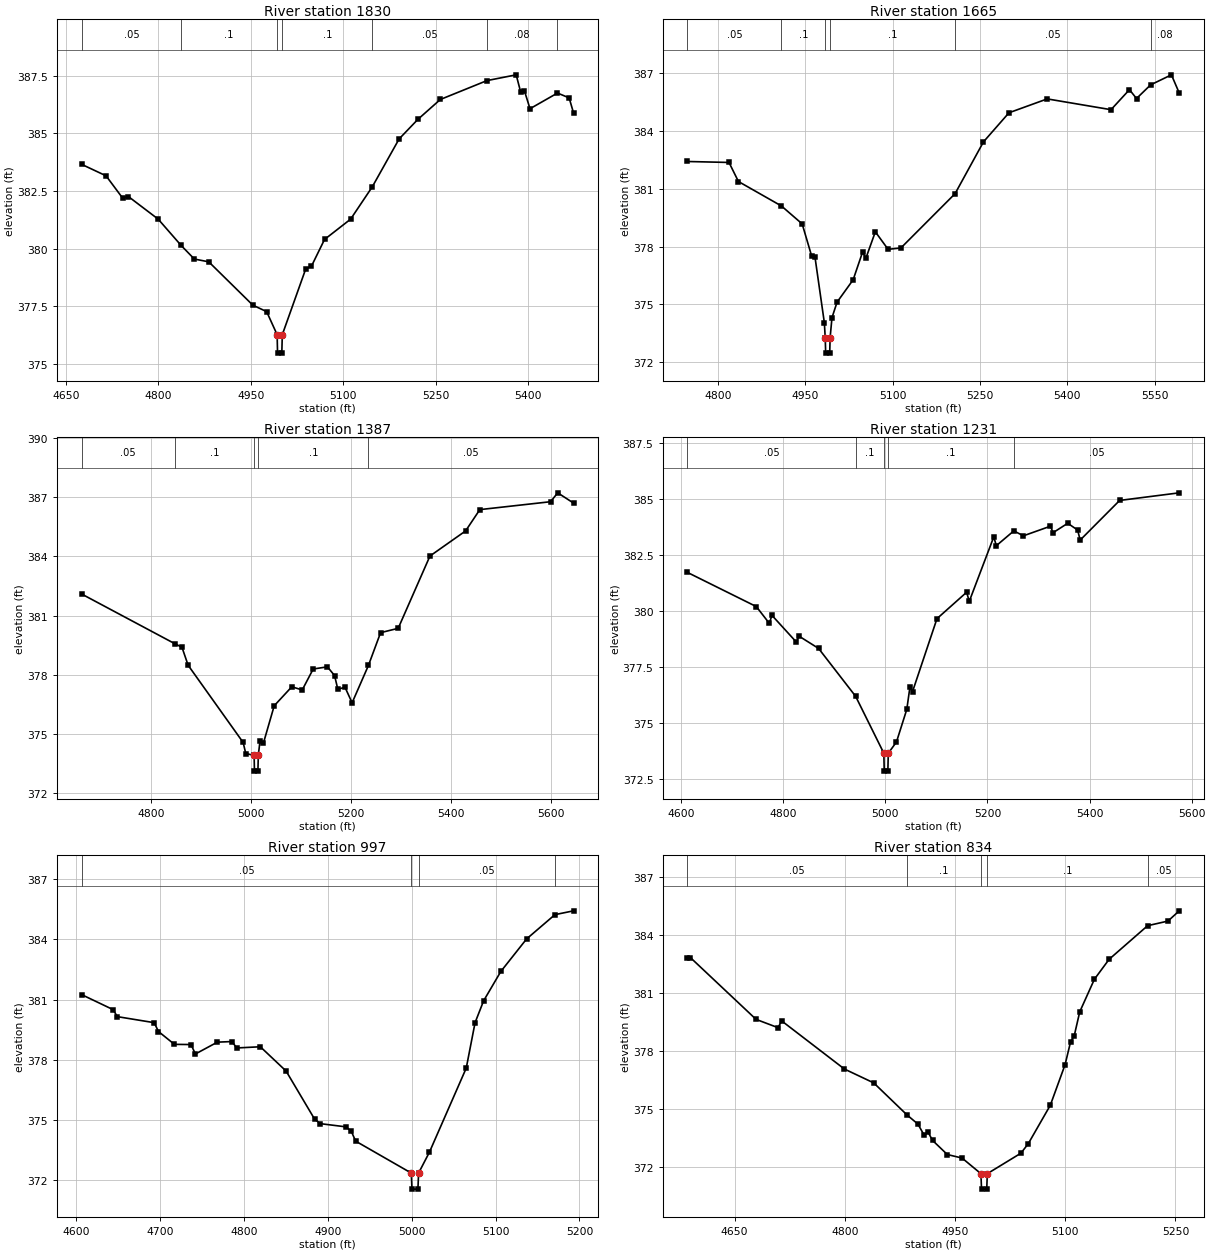
Type RM Length L Ch R = 1 ,1830    ,165,165,165
BEGIN DESCRIPTION:
Mapping XS 25927a29
END DESCRIPTION:
XS GIS Cut Line= 2
      2037049.21     13444944.13      2036376.52     13444514.48
#Sta/Elev= 30
  4675.6  383.66  4715.4  383.16  4742.4  382.19  4751.7  382.26    4800  381.28
  4837.2  380.14  4858.6  379.55    4882  379.43  4953.5  377.55  4975.9  377.27
  4992.9  376.27  4993.6  375.47  5000.5  375.47  5001.3  376.27  5039.4  379.13
  5048.4  379.23  5069.8   380.4  5112.1  381.28  5147.2  382.68  5190.8  384.76
  5221.3  385.61  5257.6  386.47  5333.3  387.29  5380.7  387.54  5387.9   386.8
  5393.9  386.86  5403.1  386.07  5447.7  386.75  5466.6  386.54  5473.8  385.88
#Mann= 7 ,-1 , 0
  4675.6     .05       0  4837.2      .1       0  4992.9     .07       0
  5001.3      .1       0  5147.2     .05       0  5333.3     .08       0
  5447.7     .05       0
Bank Sta=4992.9,5001.3
XS Rating Curve= 0 ,0
Exp/Cntr=0.3,0.1

Type RM Length L Ch R = 1 ,1665    ,278,278,278
BEGIN DESCRIPTION:
Mapping XS 493c065c
END DESCRIPTION:
XS GIS Cut Line= 2
      2037103.94     13444763.61      2036359.59      13444362.8
#Sta/Elev= 30
    4747  382.42  4818.8  382.37    4835  381.38  4908.9  380.11  4944.5  379.18
  4960.7  377.52  4966.4  377.48  4982.6  374.05  4984.1  373.27  4984.9  372.47
  4991.8  372.47  4992.5  373.27  4995.7  374.31  5004.5  375.12  5032.1  376.28
  5048.3  377.72    5054   377.4  5070.2  378.77  5092.1  377.86  5114.1  377.93
  5207.2  380.75    5256  383.44  5299.8  384.95  5365.5  385.67  5475.1  385.11
  5506.8  386.15  5518.9  385.69  5543.2   386.4  5578.9  386.92  5592.4  385.97
#Mann= 6 ,-1 , 0
    4747     .05       0  4908.9      .1       0  4984.1     .07       0
  4992.5      .1       0  5207.2     .05       0  5543.2     .08       0
Bank Sta=4984.1,4992.5
XS Rating Curve= 0 ,0
Exp/Cntr=0.3,0.1

Type RM Length L Ch R = 1 ,1387    ,156,156,156
BEGIN DESCRIPTION:
Mapping XS f277dc40
END DESCRIPTION:
XS GIS Cut Line= 3
      2037070.08      13444701.1      2036945.08     13444406.83
      2036445.46     13443969.66
#Sta/Elev= 30
  4661.3   382.1  4847.9  379.58  4862.1   379.4  4874.4  378.49  4984.4  374.58
  4989.6  374.02  5006.3  373.93    5007  373.13  5013.9  373.13  5014.7  373.93
  5018.1  374.66  5024.7  374.53  5046.5  376.44  5081.6   377.4  5102.5  377.24
  5124.4   378.3  5152.8  378.41  5167.1  377.97  5173.7  377.27  5187.9  377.38
  5202.2  376.59  5234.8  378.48  5259.1  380.14  5294.3  380.36  5357.8  384.02
    5429  385.29  5457.5  386.37  5598.9  386.77  5613.2  387.22  5644.9   386.7
#Mann= 5 ,-1 , 0
  4661.3     .05       0  4847.9      .1       0  5006.3     .07       0
  5014.7      .1       0  5234.8     .05       0
Bank Sta=5006.3,5014.7
XS Rating Curve= 0 ,0
Exp/Cntr=0.3,0.1

Type RM Length L Ch R = 1 ,1231    ,234,234,234
BEGIN DESCRIPTION:
Mapping XS 35f503b3
END DESCRIPTION:
XS GIS Cut Line= 2
      2037109.13     13444688.03      2036934.66     13443740.15
#Sta/Elev= 30
    4612  381.71  4747.3  380.18  4772.8  379.43  4777.9  379.79  4825.9  378.59
  4830.9  378.86  4869.3  378.31  4941.9  376.17  4997.1  373.63  4997.9  372.83
    5005  372.83  5005.8  373.63  5021.8  374.13  5042.1  375.59  5048.2  376.58
  5053.3  376.38  5101.2  379.64  5159.3  380.82  5164.4  380.41  5212.4  383.29
  5217.5   382.9  5251.7  383.56  5270.5  383.34  5323.5  383.77  5328.6  383.48
  5357.3   383.9  5376.6   383.6  5381.7  383.15    5459  384.92  5575.8  385.26
#Mann= 5 ,-1 , 0
    4612     .05       0  4941.9      .1       0  4997.1     .07       0
  5005.8      .1       0  5251.7     .05       0
Bank Sta=4997.1,5005.8
XS Rating Curve= 0 ,0
Exp/Cntr=0.3,0.1

Type RM Length L Ch R = 1 ,997     ,163,163,163
BEGIN DESCRIPTION:
Mapping XS 93e1de3a
END DESCRIPTION:
XS GIS Cut Line= 2
      2037161.22     13444753.18      2037286.23     13444180.26
#Sta/Elev= 30
  4606.6  381.25  4644.2   380.5  4649.3  380.15  4693.2  379.85  4698.3  379.41
  4717.3  378.77  4737.1  378.76  4742.3  378.29  4768.5  378.88  4786.2  378.91
  4791.3  378.59  4819.7  378.65  4850.4  377.44  4884.3  375.05  4891.3  374.82
    4922  374.66  4928.2  374.43  4933.3  373.95  4999.6  372.36  5000.4  371.56
  5007.5  371.56  5008.3  372.36  5021.2   373.4  5065.1  377.59  5075.6  379.85
  5085.8  380.94  5106.3   382.4    5137  384.02  5170.8  385.23    5193  385.42
#Mann= 4 ,-1 , 0
  4606.6     .05       0  4999.6     .07       0  5008.3     .05       0
  5170.8     .05       0
Bank Sta=4999.6,5008.3
XS Rating Curve= 0 ,0
Exp/Cntr=0.3,0.1

Type RM Length L Ch R = 1 ,834     ,226,226,226
BEGIN DESCRIPTION:
Mapping XS 168a9f42
END DESCRIPTION:
XS GIS Cut Line= 2
      2037343.52     13444888.61      2037377.35     13444219.66
#Sta/Elev= 30
  4585.4  382.82  4589.7  382.82  4679.1  379.62    4709  379.19    4714  379.54
  4799.3  377.05  4839.3  376.33  4884.9  374.66  4899.4   374.2  4908.1  373.61
  4913.1  373.79  4919.4  373.35  4939.5  372.62  4959.5  372.44  4985.2  371.63
    4986  370.83  4993.1  370.83  4993.9  371.63  5039.6  372.69  5049.6  373.18
  5079.6  375.17  5099.7  377.27  5107.2  378.45  5112.2  378.77  5119.7  380.01
  5139.7   381.7  5159.7  382.73  5212.1  384.47  5239.8  384.71  5255.2  385.24
#Mann= 5 ,-1 , 0
  4585.4     .05       0  4884.9      .1       0  4985.2     .07       0
  4993.9      .1       0  5212.1     .05       0
Bank Sta=4985.2,4993.9
XS Rating Curve= 0 ,0
Exp/Cntr=0.3,0.1