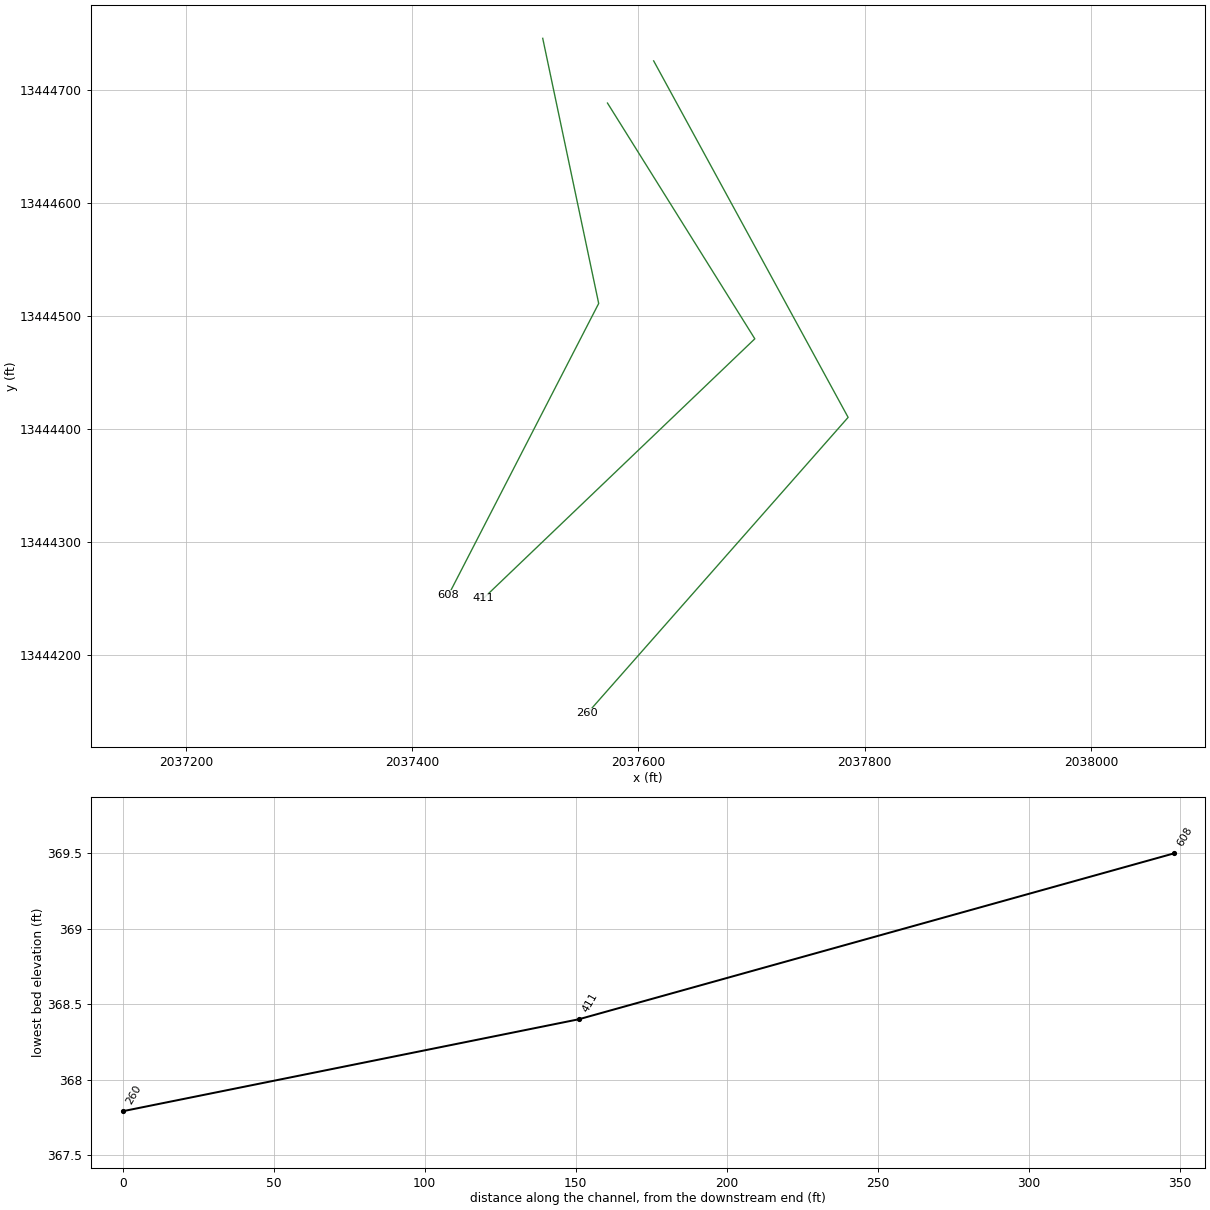
HEC-RAS study UNT 045 in RCW.prj: UNT 045 in RCW Base Level Engineering

--- UNT 045 in RCW.g01 (geometry) --- (continued)

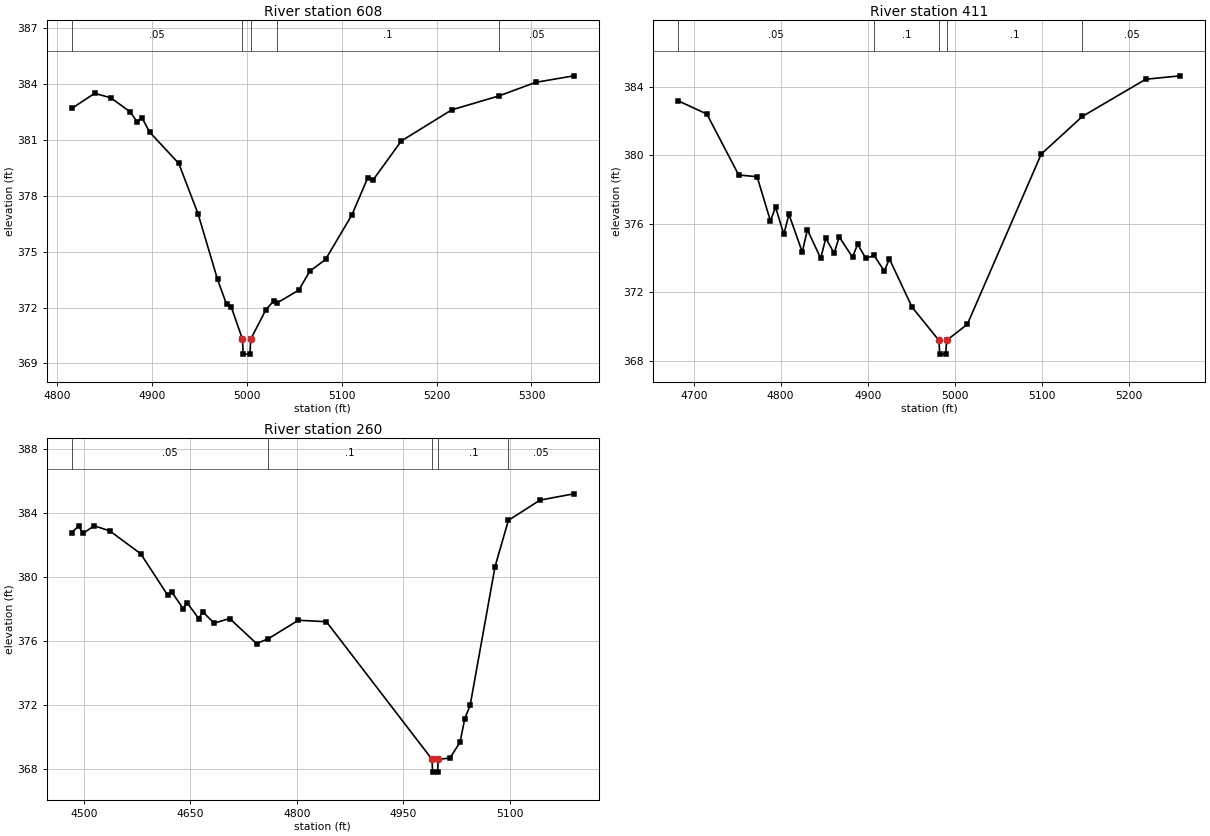
Type RM Length L Ch R = 1 ,608     ,197,197,197
BEGIN DESCRIPTION:
Mapping XS 9e65afdd
END DESCRIPTION:
XS GIS Cut Line= 3
       2037515.4     13444745.35      2037564.87       13444511.
      2037432.07     13444253.21
#Sta/Elev= 30
  4815.2  382.69  4839.3   383.5  4856.4  383.26  4876.9   382.5  4883.9  381.98
  4889.1   382.2  4897.3  381.42    4928  379.74  4948.4  377.03  4968.9  373.51
  4978.4  372.18  4983.5  372.02  4995.2   370.3    4996   369.5  5003.1   369.5
  5003.9   370.3    5020  371.89  5028.1  372.35  5031.5  372.24  5054.7  372.94
  5066.2  373.95  5082.8  374.58  5110.6  376.97  5127.1  378.94  5132.7  378.83
  5162.7  380.94  5215.8  382.61  5266.2  383.37  5304.4  384.09  5344.7  384.44
#Mann= 5 ,-1 , 0
  4815.2     .05       0  4995.2     .03       0  5003.9     .05       0
  5031.5      .1       0  5266.2     .05       0
Bank Sta=4995.2,5003.9
XS Rating Curve= 0 ,0
Exp/Cntr=0.3,0.1

Type RM Length L Ch R = 1 ,411     ,151,151,151
BEGIN DESCRIPTION:
Mapping XS e901f505
END DESCRIPTION:
XS GIS Cut Line= 3
      2037572.66     13444688.11      2037702.89     13444479.75
      2037463.27     13444250.54
#Sta/Elev= 30
  4682.2  383.19  4715.1  382.42  4751.7  378.86  4772.9  378.76  4788.2  376.18
  4794.1  376.98  4803.6   375.4  4809.5  376.56  4824.8  374.36  4830.7  375.66
    4846     374  4851.9  375.17  4861.4  374.29  4867.3  375.24  4882.6  374.06
  4888.5  374.82  4897.9  373.99  4907.4  374.16  4919.1  373.25    4925  373.96
  4951.1  371.14    4982   369.2  4982.8   368.4  4989.9   368.4  4990.7   369.2
  5014.6  370.14  5099.6  380.08  5146.9  382.28  5219.7  384.45  5259.5  384.65
#Mann= 5 ,-1 , 0
  4682.2     .05       0  4907.4      .1       0    4982     .07       0
  4990.7      .1       0  5146.9     .05       0
Bank Sta=4982,4990.7
XS Rating Curve= 0 ,0
Exp/Cntr=0.3,0.1

Type RM Length L Ch R = 1 ,260     ,0,0,0
BEGIN DESCRIPTION:
UNT 045 in RCW 1.0
END DESCRIPTION:
XS GIS Cut Line= 3
      2037613.47     13444725.42      2037785.36      13444410.3
      2037554.79     13444148.64
#Sta/Elev= 30
  4482.9  382.78  4492.8  383.19  4498.5  382.72  4514.6   383.2  4536.5  382.88
  4580.1  381.45  4618.1  378.86  4623.8  379.06  4639.9  378.02  4645.6  378.38
  4661.8   377.4  4667.5  377.82  4683.6  377.11  4705.4   377.4  4743.4  375.83
  4760.1  376.14  4802.3  377.29  4841.8   377.2  4990.7  368.59  4991.5  367.79
  4998.6  367.79  4999.4  368.59  5015.9  368.67  5030.2  369.66  5036.8  371.13
  5044.4  371.96  5079.5  380.64  5098.3  383.54  5143.1  384.81  5190.6   385.2
#Mann= 5 ,-1 , 0
  4482.9     .05       0  4760.1      .1       0  4990.7     .07       0
  4999.4      .1       0  5098.3     .05       0
Bank Sta=4990.7,4999.4
XS Rating Curve= 0 ,0
Exp/Cntr=0.3,0.1
LCMann Table=0

Chan Stop Cuts=-1
Use User Specified Reach Order=0
Composite Channel Slope=5