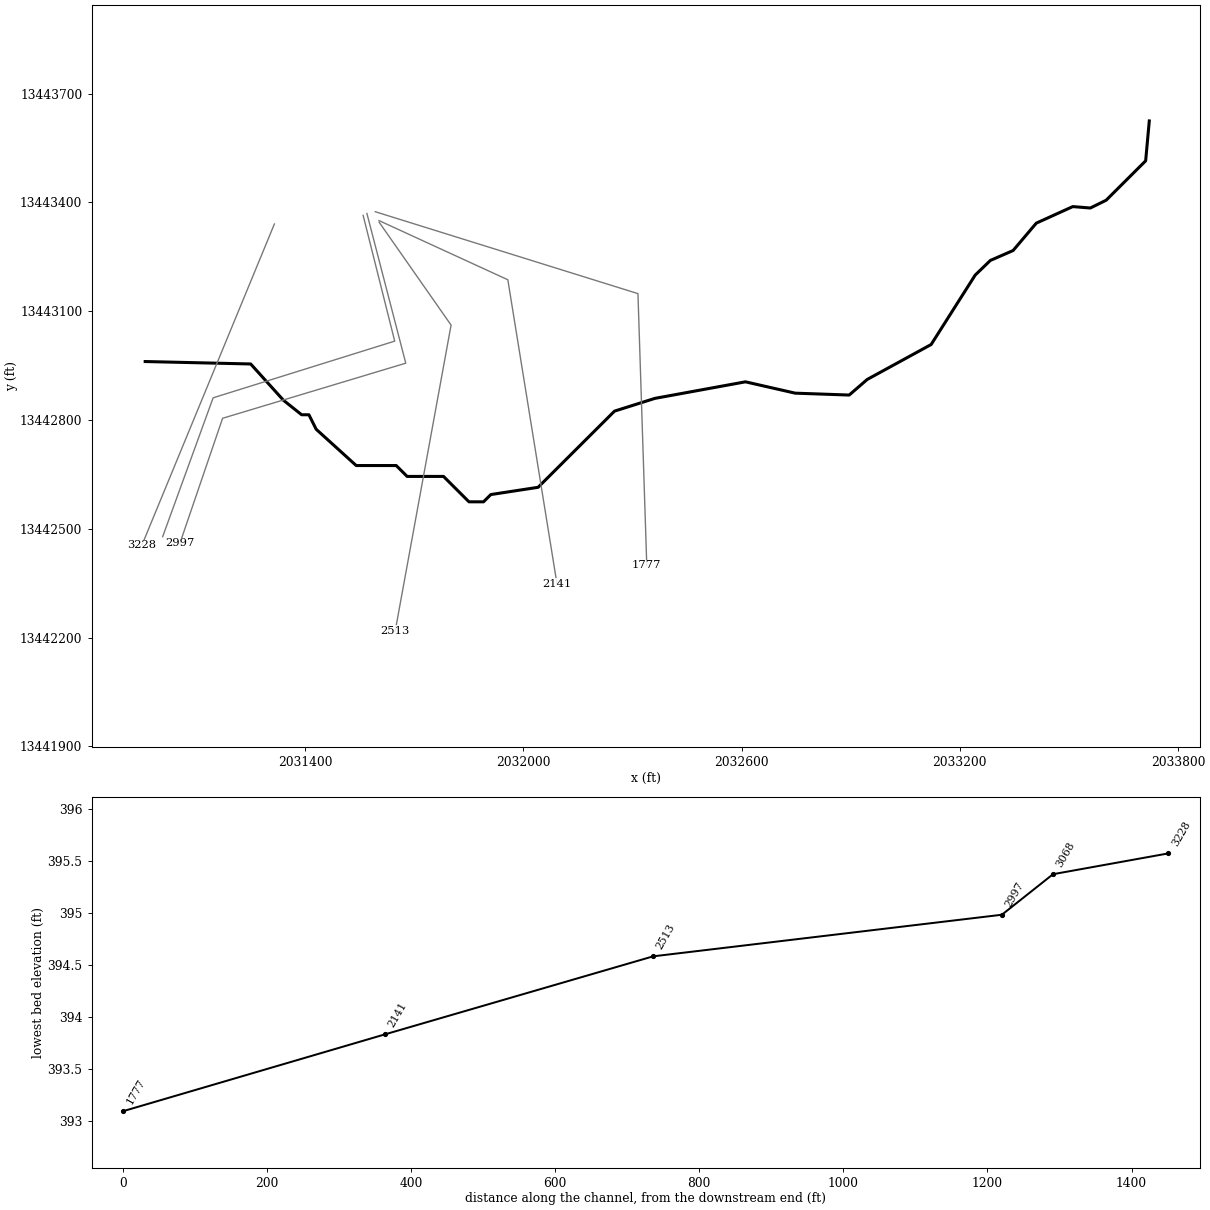
--- UNT 046 in RCW.prj (project) ---

Proj Title=UNT 046 in RCW Base Level Engineering
Current Plan=p01
Default Exp/Contr=0.3,0.1
English Units
Geom File=g01
Flow File=f01
Plan File=p01
BEGIN DESCRIPTION:
UNT 046 in RCW
END DESCRIPTION:

--- UNT 046 in RCW.p01 (plan) ---

Plan Title=Multiple Run
Short Identifier=Multiple
Geom File=g01
Flow File=f01
Subcritical Flow
K Sum by GR= 0
Std Step Tol= 0.01
Critical Tol= 0.01
Num of Std Step Trials= 20
Max Error Tol= 0.3
Flow Tol Ratio= 0.001
Split Flow NTrial= 30
Split Flow Tol= 0.02
Split Flow Ratio= 0.02
Log Output Level= 0
Friction Slope Method= 1
Unsteady Friction Slope Method= 2
Unsteady Bridges Friction Slope Method= 1
Parabolic Critical Depth
Global Vel Dist=  1 , 1 , 1
Global Log Level= 0
CheckData=True
Encroach Param= -1, 0, 0, 0
BEGIN DESCRIPTION:
Multiple Run
END DESCRIPTION:

--- UNT 046 in RCW.f01 (steady flow) ---

Flow Title=Multiple
Number of Profiles=7
Profile Names=10-year,25-year,50-year,1pct_min,100-year,1pct_plu,500-year
River Rch & RM= UNT 046 in RCW,Reach-1,3228
     149     200     241     145     289     577     422
Boundary for River Rch & Prof#=UNT 046 in RCW,Reach-1,1
Up Type=0
Dn Type=3
Dn Slope=0.005
Boundary for River Rch & Prof#=UNT 046 in RCW,Reach-1,2
Up Type=0
Dn Type=3
Dn Slope=0.005
Boundary for River Rch & Prof#=UNT 046 in RCW,Reach-1,3
Up Type=0
Dn Type=3
Dn Slope=0.005
Boundary for River Rch & Prof#=UNT 046 in RCW,Reach-1,4
Up Type=0
Dn Type=3
Dn Slope=0.005
Boundary for River Rch & Prof#=UNT 046 in RCW,Reach-1,5
Up Type=0
Dn Type=3
Dn Slope=0.005
Boundary for River Rch & Prof#=UNT 046 in RCW,Reach-1,6
Up Type=0
Dn Type=3
Dn Slope=0.005
Boundary for River Rch & Prof#=UNT 046 in RCW,Reach-1,7
Up Type=0
Dn Type=3
Dn Slope=0.005

--- UNT 046 in RCW.g01 (geometry) ---

Geom Title=Existing Conditions

River Reach=UNT 046 in RCW,Reach-1
Reach XY= 30
      2030960.79     13442961.28      2031250.80     13442954.54
      2031340.80     13442854.54      2031390.80     13442814.54
      2031410.80     13442814.54      2031430.80     13442774.54
      2031540.80     13442674.54      2031650.80     13442674.54
      2031680.80     13442644.54      2031780.80     13442644.54
      2031850.80     13442574.54      2031890.80     13442574.54
      2031910.80     13442594.54      2032040.80     13442614.54
      2032250.80     13442824.54      2032362.07     13442859.76
      2032610.77     13442905.33      2032747.49     13442874.08
      2032895.93     13442868.87      2032945.41     13442911.84
      2033121.19     13443008.20      2033242.28     13443199.60
      2033283.95     13443239.97      2033346.45     13443267.31
      2033410.25     13443342.83      2033510.51     13443388.41
      2033558.69     13443384.50      2033602.28     13443406.01
      2033710.80     13443514.54      2033720.80     13443624.54

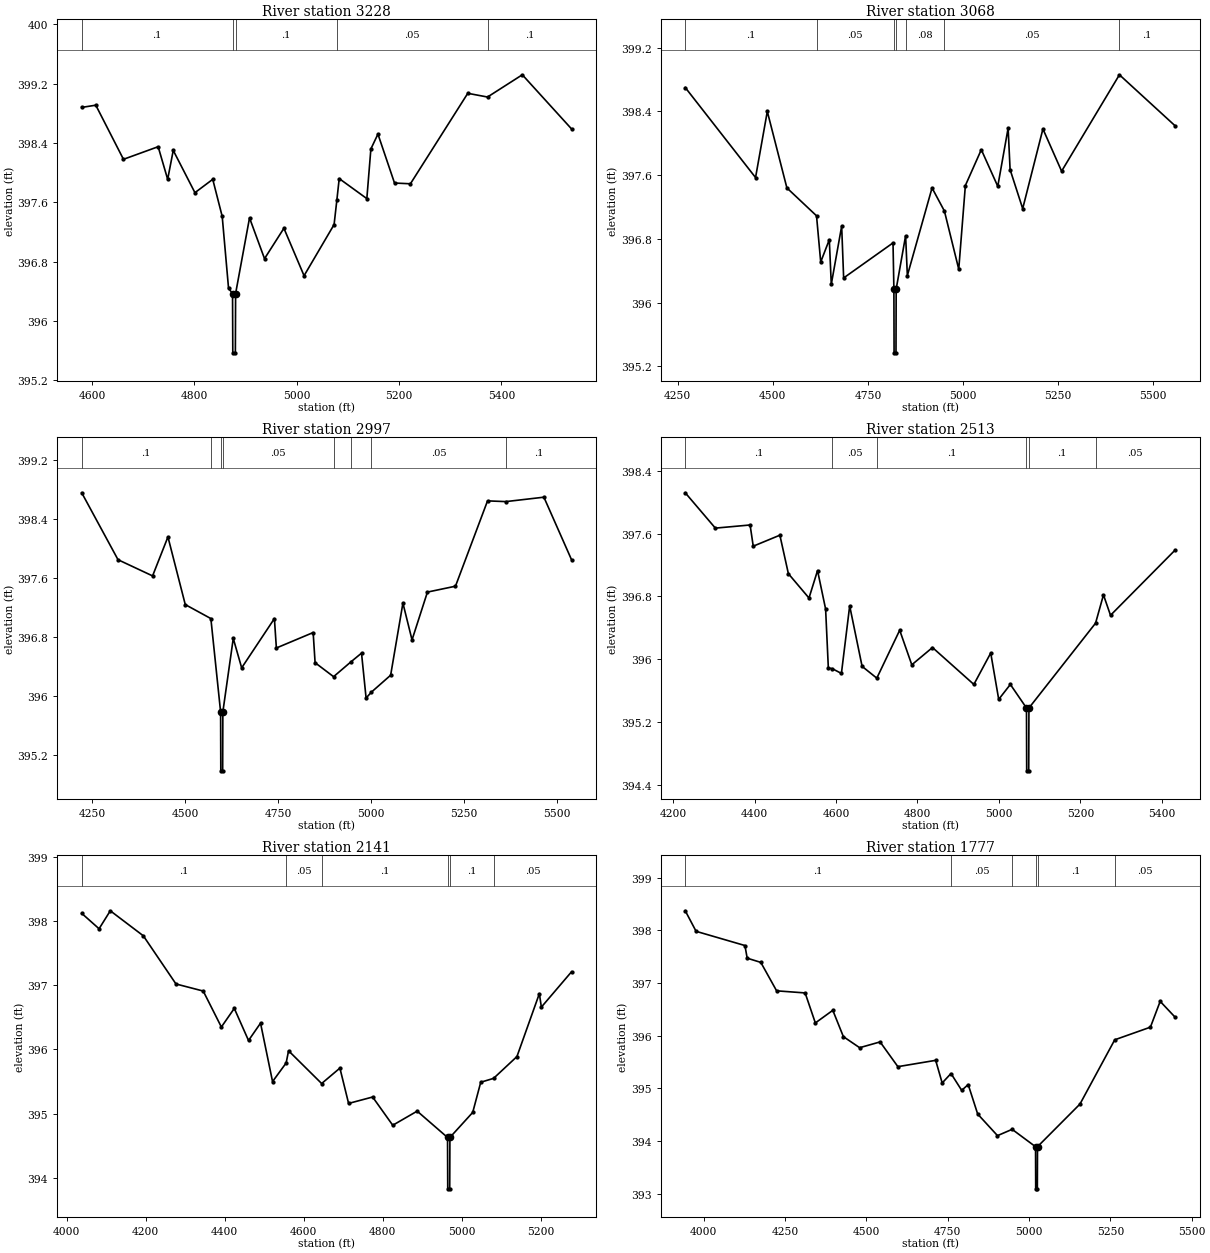
Type RM Length L Ch R = 1,3228,160,160,160
BEGIN DESCRIPTION:
UNT 046 in RCW 1.0
END DESCRIPTION:
XS GIS Cut Line= 2
      2031315.93     13443340.45      2030951.77     13442455.01
#Sta/Elev= 30
  4579.8  398.88  4607.3  398.91  4661.4  398.18  4729.2  398.35  4747.8  397.91
  4758.7  398.30  4801.1  397.73  4835.9  397.91  4854.4  397.41  4866.8  396.44
  4874.6  396.37  4875.1  395.57  4880.1  395.57  4880.6  396.37  4907.8  397.39
  4937.1  396.84  4975.0  397.25  5014.4  396.61  5073.1  397.30  5078.5  397.63
  5083.1  397.92  5137.1  397.65  5145.0  398.32  5158.8  398.52  5191.2  397.86
  5222.3  397.85  5334.4  399.07  5373.0  399.02  5441.0  399.32  5537.2  398.59
#Mann=5,-1,0
  4579.8     0.1       0  4874.6    0.07       0  4880.6     0.1       0
  5078.5    0.05       0  5373.0     0.1       0
Bank Sta=4874.6,4880.6
Exp/Cntr=0.3,0.1

Type RM Length L Ch R = 1,3068,71,71,71
BEGIN DESCRIPTION:
UNT 046 in RCW 8.0
END DESCRIPTION:
XS GIS Cut Line= 4
      2031559.84     13443364.23      2031646.64     13443017.51
      2031147.51     13442861.26      2031008.79     13442478.36
#Sta/Elev= 30
  4269.7  398.70  4454.5  397.57  4485.4  398.40  4536.9  397.44  4614.8  397.09
  4625.8  396.51  4648.4  396.79  4653.6  396.23  4680.9  396.96  4686.1  396.31
  4815.9  396.75  4818.2  396.17  4818.7  395.37  4823.7  395.37  4824.2  396.17
  4849.0  396.84  4853.6  396.34  4918.5  397.44  4951.0  397.15  4988.7  396.42
  5006.1  397.47  5048.0  397.92  5091.3  397.46  5118.5  398.19  5123.7  397.67
  5156.8  397.18  5210.0  398.18  5259.1  397.65  5411.1  398.86  5557.4  398.22
#Mann=7,-1,0
  4269.7     0.1       0  4614.8    0.05       0  4818.2    0.04       0
  4824.2    0.05       0  4849.0    0.08       0  4951.0    0.05       0
  5411.1     0.1       0
Bank Sta=4818.2,4824.2
Exp/Cntr=0.3,0.1

Type RM Length L Ch R = 1,2997,484,484,484
BEGIN DESCRIPTION:
UNT 046 in RCW 7.0
END DESCRIPTION:
XS GIS Cut Line= 4
      2031570.26     13443369.45      2031677.02     13442956.74
      2031173.55     13442804.83      2031056.04     13442459.67
#Sta/Elev= 30
  4221.9  398.76  4319.5  397.85  4412.4  397.63  4453.7  398.16  4500.3  397.24
  4569.1  397.05  4595.3  395.78  4595.8  394.98  4600.8  394.98  4601.3  395.78
  4629.3  396.78  4651.9  396.38  4739.9  397.05  4745.2  396.65  4844.1  396.86
  4849.3  396.45  4899.0  396.26  4945.3  396.46  4974.1  396.58  4986.4  395.97
  5000.7  396.05  5052.4  396.28  5085.4  397.26  5109.9  396.76  5151.3  397.41
  5226.7  397.49  5312.9  398.65  5362.0  398.64  5464.4  398.70  5538.7  397.85
#Mann=8,-1,0
  4221.9     0.1       0  4569.1    0.05       0  4595.3    0.07       0
  4601.3    0.05       0  4899.0    0.08       0  4945.3     0.1       0
  5000.7    0.05       0  5362.0     0.1       0
Bank Sta=4595.3,4601.3
Exp/Cntr=0.3,0.1

Type RM Length L Ch R = 1,2513,372,372,372
BEGIN DESCRIPTION:
Mapping XS b0ecc911
END DESCRIPTION:
XS GIS Cut Line= 3
      2031603.68     13443345.59      2031801.59     13443061.76
      2031648.13     13442219.04
#Sta/Elev= 30
  4229.9  398.12  4303.8  397.67  4389.1  397.71  4396.8  397.44  4462.2  397.58
  4483.1  397.09  4533.7  396.78  4554.7  397.13  4574.5  396.64  4581.2  395.89
  4591.1  395.88  4613.3  395.82  4633.6  396.68  4664.1  395.91  4700.2  395.76
  4756.4  396.37  4786.1  395.93  4836.9  396.15  4938.5  395.68  4979.9  396.08
  4999.5  395.49  5028.1  395.68  5067.7  395.38  5068.2  394.58  5073.2  394.58
  5073.7  395.38  5237.3  396.46  5256.7  396.82  5274.0  396.56  5432.5  397.39
#Mann=6,-1,0
  4229.9     0.1       0  4591.1    0.05       0  4700.2     0.1       0
  5067.7    0.07       0  5073.7     0.1       0  5237.3    0.05       0
Bank Sta=5067.7,5073.7
Exp/Cntr=0.3,0.1

Type RM Length L Ch R = 1,2141,364,364,364
BEGIN DESCRIPTION:
Mapping XS 0694fe47
END DESCRIPTION:
XS GIS Cut Line= 3
      2031603.45     13443349.86      2031957.60     13443186.68
      2032092.72     13442348.23
#Sta/Elev= 30
  4038.4  398.12  4082.3  397.88  4110.7  398.16  4194.3  397.77  4276.9  397.02
  4345.8  396.91  4391.7  396.35  4424.4  396.64  4460.4  396.14  4490.8  396.41
  4521.2  395.50  4555.6  395.79  4561.7  395.98  4645.4  395.47  4691.6  395.71
  4713.6  395.16  4774.4  395.26  4825.3  394.82  4887.1  395.04  4963.9  394.63
  4964.4  393.83  4969.4  393.83  4969.9  394.63  5027.6  395.02  5047.9  395.49
  5080.3  395.55  5139.5  395.89  5196.2  396.87  5201.3  396.66  5277.6  397.21
#Mann=6,-1,0
  4038.4     0.1       0  4555.6    0.05       0  4645.4     0.1       0
  4963.9    0.07       0  4969.9     0.1       0  5080.3    0.05       0
Bank Sta=4963.9,4969.9
Exp/Cntr=0.3,0.1

Type RM Length L Ch R = 1,1777,0,0,0
BEGIN DESCRIPTION:
UNT 046 in RCW 6.0
END DESCRIPTION:
XS GIS Cut Line= 3
      2031593.24     13443374.26      2032315.24     13443148.48
      2032339.52     13442399.25
#Sta/Elev= 30
  3942.9  398.37  3976.2  397.98  4126.4  397.71  4133.3  397.47  4175.2  397.39
  4223.8  396.85  4311.5  396.81  4342.9  396.24  4396.6  396.48  4429.1  395.98
  4479.1  395.77  4542.0  395.88  4596.7  395.41  4712.9  395.53  4732.9  395.10
  4760.0  395.28  4792.9  394.96  4812.9  395.07  4842.1  394.51  4903.0  394.10
  4948.0  394.22  5020.0  393.89  5020.5  393.09  5025.5  393.09  5026.0  393.89
  5156.6  394.70  5263.5  395.92  5373.2  396.16  5403.2  396.65  5449.0  396.35
#Mann=6,-1,0
  3942.9     0.1       0  4760.0    0.05       0  4948.0     0.1       0
  5020.0    0.07       0  5026.0     0.1       0  5263.5    0.05       0
Bank Sta=5020,5026
Exp/Cntr=0.3,0.1

Chan Stop Cuts=-1