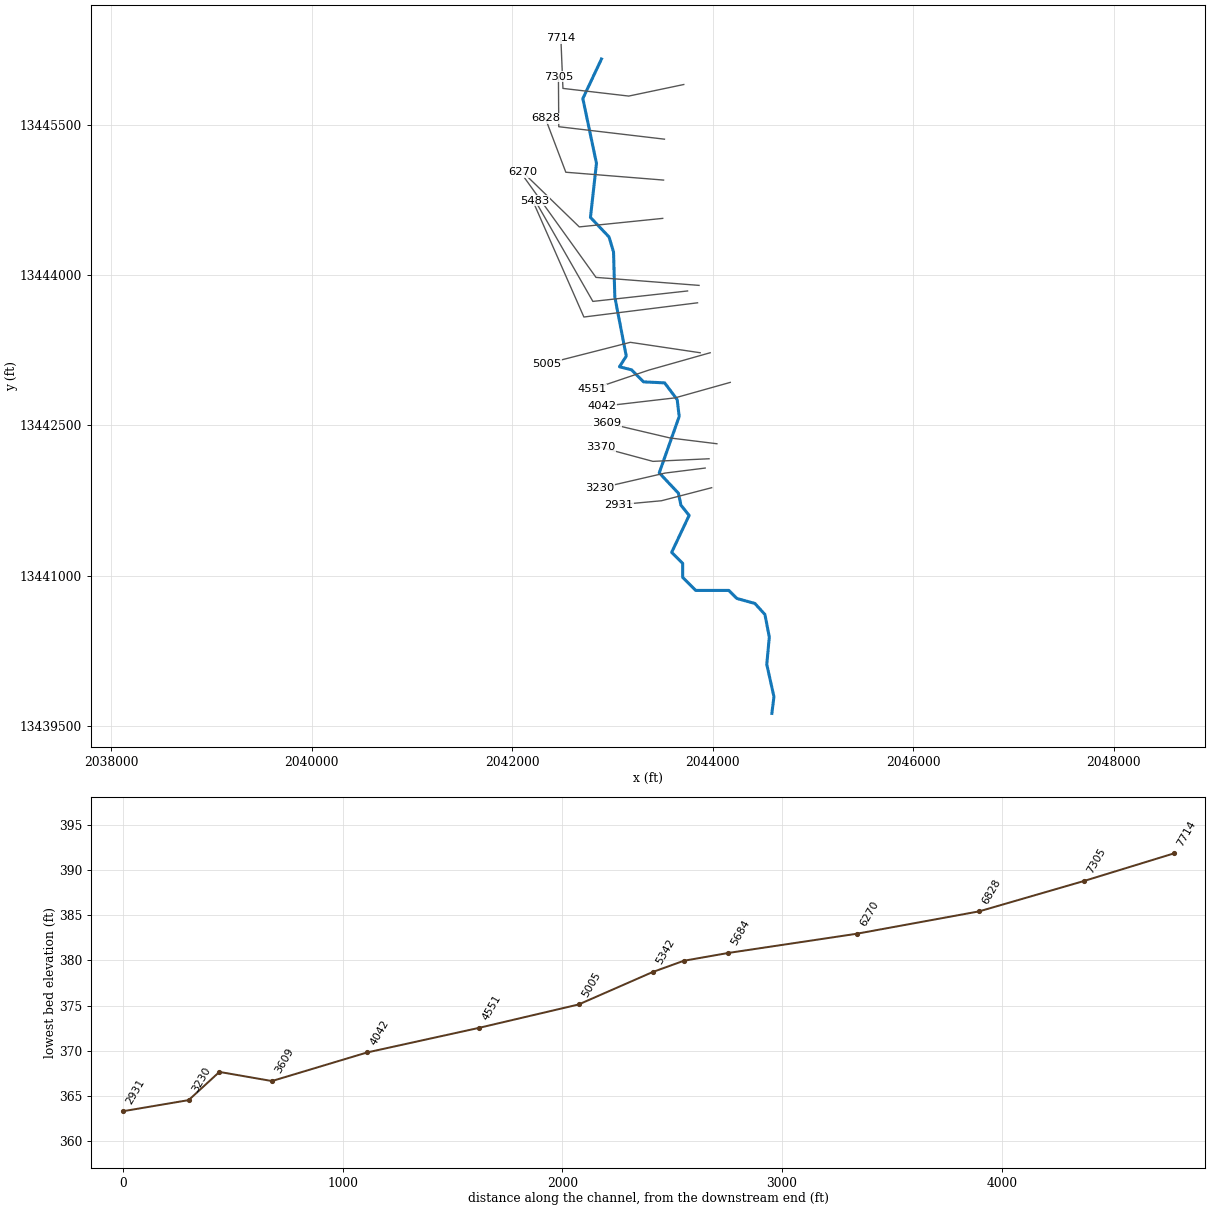
--- UNT 048 in RCW.prj (project) ---

Proj Title=UNT 048 in RCW Base Level Engineering
Current Plan=p01
Default Exp/Contr=0.3,0.1
English Units
Geom File=g01
Flow File=f01
Plan File=p01
BEGIN DESCRIPTION:
UNT 048 in RCW
END DESCRIPTION:

--- UNT 048 in RCW.p01 (plan) ---

Plan Title=Multiple Run
Short Identifier=Multiple
Geom File=g01
Flow File=f01
Subcritical Flow
K Sum by GR= 0
Std Step Tol= 0.01
Critical Tol= 0.01
Num of Std Step Trials= 20
Max Error Tol= 0.3
Flow Tol Ratio= 0.001
Split Flow NTrial= 30
Split Flow Tol= 0.02
Split Flow Ratio= 0.02
Log Output Level= 0
Friction Slope Method= 1
Unsteady Friction Slope Method= 2
Unsteady Bridges Friction Slope Method= 1
Parabolic Critical Depth
Global Vel Dist=  1 , 1 , 1
Global Log Level= 0
CheckData=True
Encroach Param= -1, 0, 0, 0
BEGIN DESCRIPTION:
Multiple Run
END DESCRIPTION:

--- UNT 048 in RCW.f01 (steady flow) ---

Flow Title=Multiple
Number of Profiles=7
Profile Names=10-year,25-year,50-year,1pct_min,100-year,1pct_plu,500-year
River Rch & RM= UNT 048 in RCW,Reach-1,7714
     238     330     407     250     500     997     764
River Rch & RM= UNT 048 in RCW,Reach-1,4551
     339     479     597     371     740    1476    1154
Boundary for River Rch & Prof#=UNT 048 in RCW,Reach-1,1
Up Type=0
Dn Type=3
Dn Slope=0.005
Boundary for River Rch & Prof#=UNT 048 in RCW,Reach-1,2
Up Type=0
Dn Type=3
Dn Slope=0.005
Boundary for River Rch & Prof#=UNT 048 in RCW,Reach-1,3
Up Type=0
Dn Type=3
Dn Slope=0.005
Boundary for River Rch & Prof#=UNT 048 in RCW,Reach-1,4
Up Type=0
Dn Type=3
Dn Slope=0.005
Boundary for River Rch & Prof#=UNT 048 in RCW,Reach-1,5
Up Type=0
Dn Type=3
Dn Slope=0.005
Boundary for River Rch & Prof#=UNT 048 in RCW,Reach-1,6
Up Type=0
Dn Type=3
Dn Slope=0.005
Boundary for River Rch & Prof#=UNT 048 in RCW,Reach-1,7
Up Type=0
Dn Type=3
Dn Slope=0.005

--- UNT 048 in RCW.g01 (geometry) ---

Geom Title=Existing Conditions

River Reach=UNT 048 in RCW,Reach-1
Reach XY= 30
      2042890.80     13446154.54      2042704.95     13445759.78
      2042840.80     13445114.54      2042780.80     13444574.54
      2042966.45     13444379.44      2043010.94     13444229.71
      2043023.96     13443780.49      2043137.90     13443191.29
      2043070.40     13443084.96      2043190.80     13443054.54
      2043310.80     13442934.54      2043520.80     13442924.54
      2043645.92     13442756.83      2043665.89     13442589.30
      2043466.85     13442027.06      2043658.25     13441823.93
      2043682.99     13441705.44      2043765.02     13441602.58
      2043590.80     13441234.54      2043700.80     13441124.54
      2043700.80     13440984.54      2043830.80     13440854.54
      2044160.80     13440854.54      2044240.80     13440774.54
      2044420.80     13440724.54      2044520.80     13440614.54
      2044564.50     13440390.34      2044539.33     13440116.47
      2044610.80     13439794.54      2044590.17     13439628.41

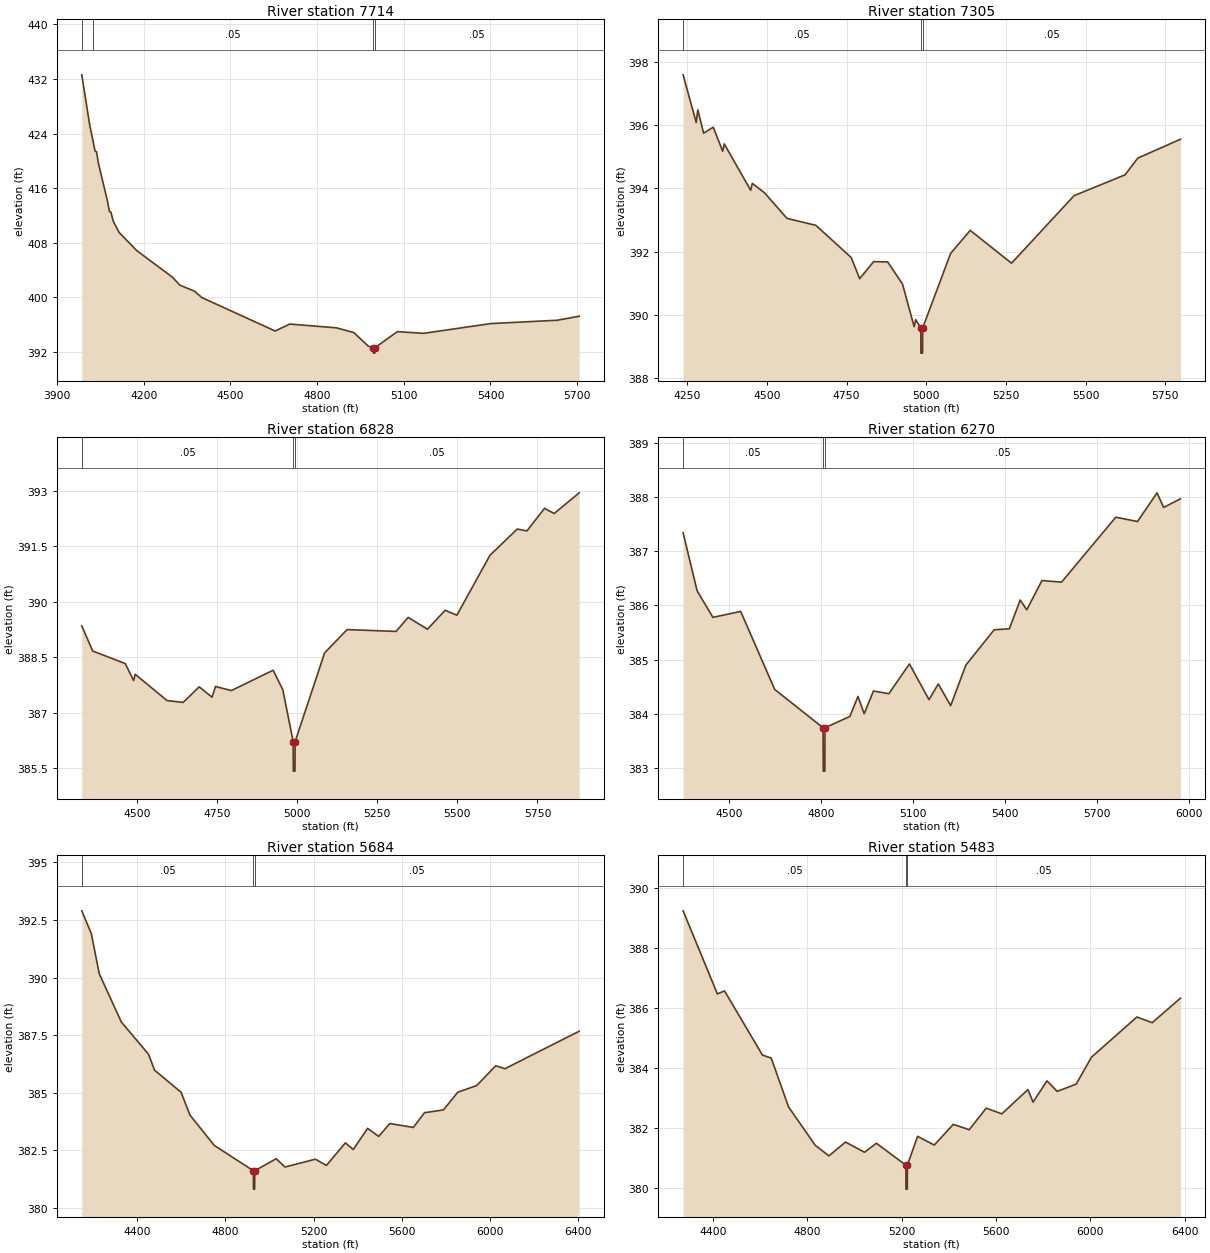
Type RM Length L Ch R = 1,7714,409,409,409
BEGIN DESCRIPTION:
UNT 048 in RCW 11.0
END DESCRIPTION:
XS GIS Cut Line= 4
      2043711.57     13445900.10      2043162.79     13445784.77
      2042506.54     13445861.16      2042485.74     13446360.58
#Sta/Elev= 30
  3985.7  432.61  4012.9  425.31  4024.9  422.85  4031.5  421.45  4036.6  421.35
  4043.5  419.60  4074.2  414.18  4081.4  412.59  4086.5  412.48  4094.6  411.16
  4115.0  409.51  4176.0  406.85  4299.0  402.97  4325.5  401.78  4375.4  400.91
  4401.2  399.97  4655.0  395.07  4705.3  396.09  4866.4  395.54  4926.8  394.85
  4977.1  392.86  4994.3  392.63  4994.8  391.83  4999.8  391.83  5000.3  392.63
  5077.8  394.98  5168.4  394.73  5401.2  396.16  5631.4  396.65  5707.0  397.24
#Mann=4,-1,0
  3985.7     0.1       0  4024.9    0.05       0  4994.3   0.035       0
  5000.3    0.05       0
Bank Sta=4994.3,5000.3
Exp/Cntr=0.3,0.1

Type RM Length L Ch R = 1,7305,477,477,477
BEGIN DESCRIPTION:
Mapping XS f0793b73
END DESCRIPTION:
XS GIS Cut Line= 3
      2043518.85     13445354.96      2042464.88     13445479.22
      2042461.41     13445979.23
#Sta/Elev= 30
  4236.7  397.60  4277.8  396.09  4282.8  396.49  4301.0  395.75  4331.2  395.94
  4360.8  395.18  4365.8  395.41  4448.8  393.94  4453.8  394.16  4492.3  393.86
  4562.8  393.05  4653.4  392.83  4764.2  391.81  4790.8  391.14  4834.7  391.68
  4878.8  391.67  4925.3  390.97  4961.8  389.62  4966.8  389.84  4982.7  389.58
  4983.2  388.78  4988.2  388.78  4988.7  389.58  5076.3  391.94  5137.8  392.67
  5267.6  391.63  5463.8  393.77  5623.8  394.43  5663.8  394.96  5798.0  395.56
#Mann=3,-1,0
  4236.7    0.05       0  4982.7   0.035       0  4988.7    0.05       0
Bank Sta=4982.7,4988.7
Exp/Cntr=0.3,0.1

Type RM Length L Ch R = 1,6828,558,558,558
BEGIN DESCRIPTION:
Mapping XS 67767e14
END DESCRIPTION:
XS GIS Cut Line= 3
      2043510.15     13444946.98      2042535.19     13445025.22
      2042331.85     13445561.69
#Sta/Elev= 30
  4328.5  389.35  4362.5  388.67  4464.1  388.33  4490.2  387.87  4495.2  388.04
  4594.5  387.33  4644.7  387.28  4694.8  387.70  4734.9  387.42  4745.6  387.71
  4795.1  387.60  4925.6  388.15  4955.7  387.62  4988.0  386.22  4988.5  385.42
  4993.6  385.42  4994.1  386.22  5086.1  388.62  5156.3  389.25  5309.1  389.20
  5346.6  389.58  5406.9  389.26  5461.9  389.77  5498.8  389.64  5601.9  391.26
  5687.0  391.97  5717.2  391.92  5772.1  392.53  5802.3  392.39  5880.3  392.95
#Mann=3,-1,0
  4328.5    0.05       0  4988.0   0.035       0  4994.1    0.05       0
Bank Sta=4988,4994.1
Exp/Cntr=0.3,0.1

Type RM Length L Ch R = 1,6270,586,586,586
BEGIN DESCRIPTION:
Mapping XS f8f68715
END DESCRIPTION:
XS GIS Cut Line= 3
      2043501.47     13444565.03      2042669.47     13444480.03
      2042107.00     13445025.14
#Sta/Elev= 30
  4351.4  387.34  4397.0  386.27  4448.4  385.78  4538.8  385.89  4649.4  384.45
  4807.2  383.74  4807.7  382.94  4812.8  382.94  4813.3  383.74  4894.3  383.95
  4920.8  384.32  4940.9  384.00  4971.1  384.42  5021.3  384.37  5088.2  384.92
  5152.0  384.26  5182.2  384.55  5222.6  384.15  5272.2  384.90  5364.1  385.55
  5413.7  385.57  5448.9  386.10  5470.3  385.92  5519.7  386.46  5583.5  386.43
  5760.2  387.63  5830.9  387.55  5894.5  388.08  5915.8  387.81  5971.0  387.97
#Mann=3,-1,0
  4351.4    0.05       0  4807.2   0.035       0  4813.3    0.05       0
Bank Sta=4807.2,4813.3
Exp/Cntr=0.3,0.1

Type RM Length L Ch R = 1,5684,201,201,201
BEGIN DESCRIPTION:
Mapping XS 77a8f686
END DESCRIPTION:
XS GIS Cut Line= 3
      2043863.86     13443896.70      2042836.14     13443976.56
      2042121.96     13444971.56
#Sta/Elev= 30
  4149.1  392.90  4192.4  391.91  4228.2  390.17  4328.5  388.07  4451.8  386.67
  4479.0  385.98  4599.3  385.02  4639.4  384.03  4749.8  382.71  4927.1  381.61
  4927.6  380.81  4933.0  380.81  4933.5  381.61  5030.6  382.13  5070.7  381.77
  5208.2  382.11  5258.5  381.84  5344.5  382.82  5380.1  382.53  5445.2  383.45
  5495.5  383.10  5545.9  383.66  5652.7  383.49  5703.0  384.13  5789.0  384.25
  5854.1  385.02  5940.0  385.31  6026.0  386.17  6067.7  386.04  6404.7  387.67
#Mann=3,-1,0
  4149.1    0.05       0  4927.1    0.03       0  4933.5    0.05       0
Bank Sta=4927.1,4933.5
Exp/Cntr=0.3,0.1

Type RM Length L Ch R = 1,5483,141,141,141
BEGIN DESCRIPTION:
Mapping XS 319d16f6
END DESCRIPTION:
XS GIS Cut Line= 3
      2043749.36     13443841.15      2042804.89     13443736.98
      2042229.26     13444742.59
#Sta/Elev= 30
  4273.8  389.23  4419.0  386.46  4449.2  386.56  4610.2  384.42  4647.3  384.32
  4720.9  382.69  4834.1  381.41  4891.9  381.06  4962.3  381.52  5042.8  381.18
  5093.1  381.48  5218.2  380.75  5218.7  379.95  5224.1  379.95  5224.6  380.75
  5267.8  381.71  5338.6  381.42  5419.2  382.11  5486.7  381.93  5558.8  382.65
  5625.0  382.46  5735.8  383.27  5757.4  382.85  5816.4  383.56  5859.5  383.21
  5940.1  383.45  6005.2  384.35  6197.7  385.69  6262.5  385.50  6382.7  386.32
#Mann=3,-1,0
  4273.8    0.05       0  5218.2    0.03       0  5224.6    0.05       0
Bank Sta=5218.2,5224.6
Exp/Cntr=0.3,0.1

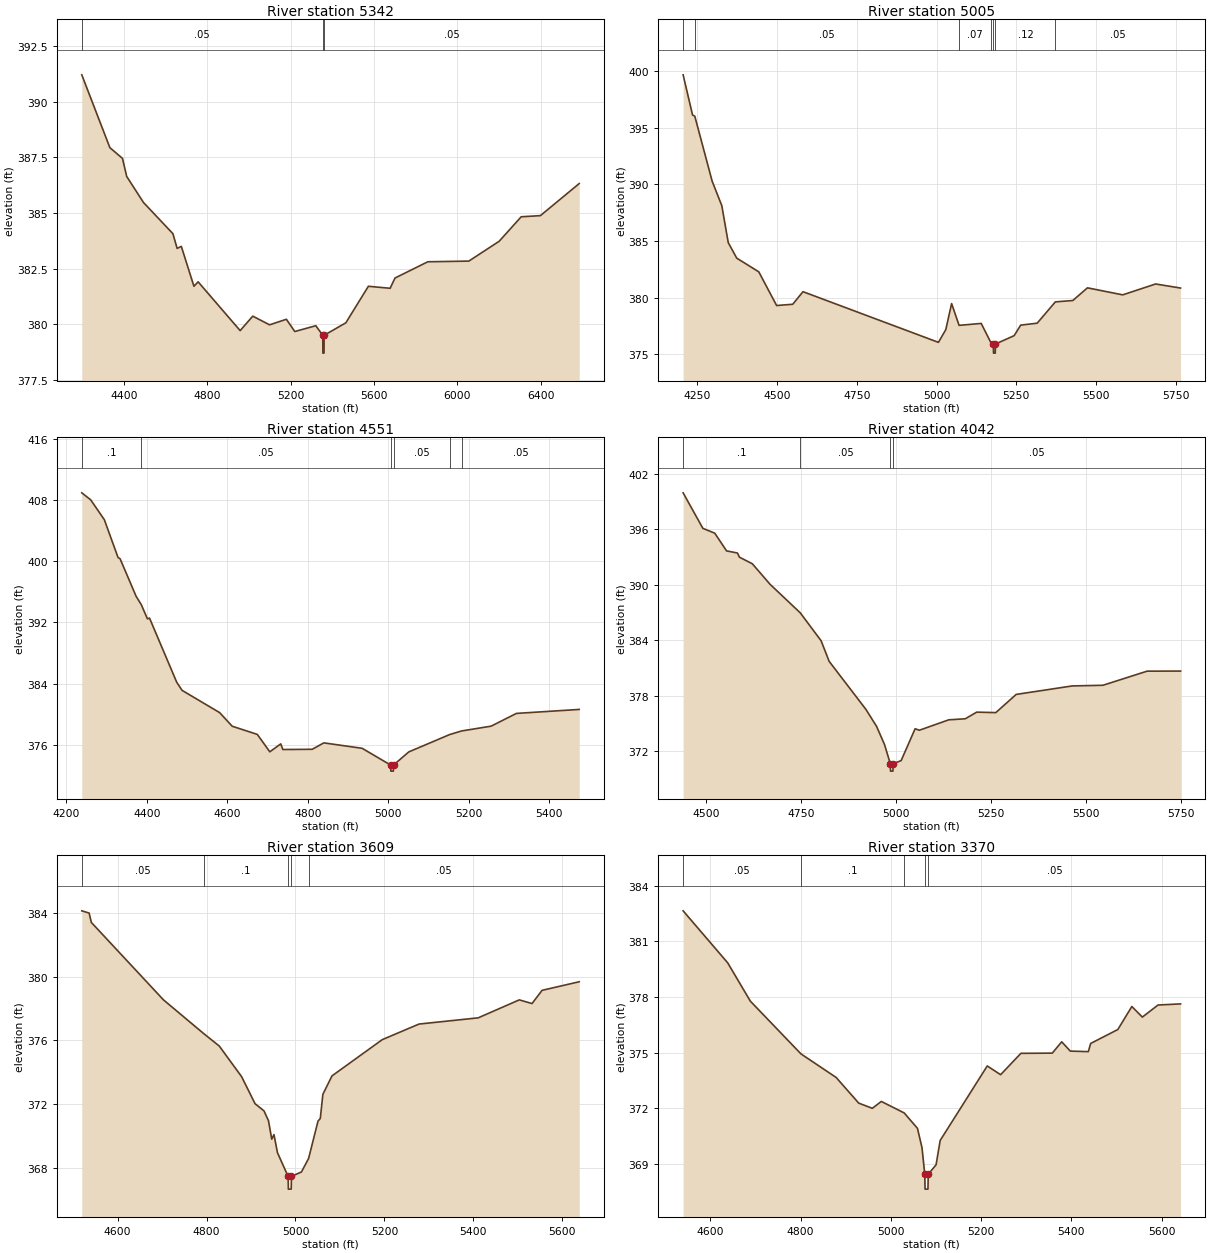
Type RM Length L Ch R = 1,5342,337,337,337
BEGIN DESCRIPTION:
Mapping XS 5c8f2345
END DESCRIPTION:
XS GIS Cut Line= 3
      2043848.73     13443723.02      2042715.40     13443581.31
      2042214.63     13444719.57
#Sta/Elev= 30
  4198.6  391.20  4333.4  387.93  4393.8  387.45  4414.0  386.64  4494.6  385.47
  4635.7  384.07  4655.9  383.41  4676.0  383.50  4736.5  381.71  4756.6  381.91
  4958.2  379.72  5018.7  380.37  5099.3  379.98  5179.9  380.23  5220.2  379.68
  5321.0  379.94  5354.5  379.51  5355.0  378.71  5360.4  378.71  5360.9  379.51
  5465.0  380.07  5573.2  381.71  5677.5  381.62  5700.8  382.08  5858.3  382.81
  6054.9  382.84  6200.4  383.73  6306.2  384.83  6398.1  384.88  6584.3  386.32
#Mann=3,-1,0
  4198.6    0.05       0  5354.5    0.03       0  5360.9    0.05       0
Bank Sta=5354.5,5360.9
Exp/Cntr=0.3,0.1

Type RM Length L Ch R = 1,5005,454,454,454
BEGIN DESCRIPTION:
UNT 048 in RCW 8.0
END DESCRIPTION:
XS GIS Cut Line= 3
      2043874.96     13443225.01      2043178.58     13443328.92
      2042349.35     13443117.28
#Sta/Elev= 30
  4205.0  399.67  4234.5  396.13  4241.6  396.02  4296.0  390.29  4326.3  388.13
  4346.5  384.87  4373.1  383.50  4442.3  382.29  4498.2  379.32  4548.7  379.43
  4580.9  380.54  5005.7  376.07  5028.8  377.20  5047.0  379.49  5070.4  377.57
  5139.8  377.74  5171.0  376.00  5177.9  375.92  5178.4  375.12  5183.8  375.12
  5184.3  375.92  5243.0  376.66  5263.6  377.59  5315.3  377.76  5372.3  379.64
  5427.0  379.76  5473.0  380.88  5583.6  380.26  5686.8  381.22  5764.9  380.86
#Mann=7,-1,0
  4205.0     0.1       0  4241.6    0.05       0  5070.4    0.07       0
  5171.0    0.12       0  5177.9    0.03       0  5184.3    0.12       0
  5372.3    0.05       0
Bank Sta=5177.9,5184.3
Exp/Cntr=0.3,0.1

Type RM Length L Ch R = 1,4551,509,509,509
BEGIN DESCRIPTION:
UNT 048 in RCW 7.0
END DESCRIPTION:
XS GIS Cut Line= 3
      2043974.99     13443225.00      2043362.60     13443051.79
      2042793.62     13442859.53
#Sta/Elev= 30
  4238.1  408.98  4260.3  408.06  4294.2  405.46  4328.2  400.52  4333.4  400.34
  4373.2  395.43  4386.2  394.32  4401.3  392.48  4406.5  392.58  4474.4  384.15
  4487.5  383.11  4581.0  380.19  4612.2  378.41  4674.6  377.34  4705.7  375.06
  4732.9  376.10  4738.1  375.36  4811.2  375.39  4840.0  376.23  4935.3  375.52
  5006.1  373.33  5006.7  372.53  5012.9  372.53  5013.4  373.33  5051.4  375.05
  5153.0  377.32  5182.6  377.79  5256.1  378.42  5319.0  380.09  5475.1  380.61
#Mann=6,-1,0
  4238.1     0.1       0  4386.2    0.05       0  5006.1    0.03       0
  5013.4    0.05       0  5153.0    0.12       0  5182.6    0.05       0
Bank Sta=5006.1,5013.4
Exp/Cntr=0.3,0.1

Type RM Length L Ch R = 1,4042,433,433,433
BEGIN DESCRIPTION:
UNT 048 in RCW 6.0
END DESCRIPTION:
XS GIS Cut Line= 3
      2044175.07     13442929.39      2043625.00     13442775.00
      2042892.05     13442689.91
#Sta/Elev= 30
  4439.1  399.96  4491.1  396.11  4522.3  395.59  4553.4  393.67  4582.1  393.44
  4587.3  392.99  4621.4  392.27  4667.7  390.06  4747.6  386.95  4802.2  383.94
  4823.5  381.70  4920.0  376.51  4948.1  374.67  4968.9  372.72  4984.5  370.61
  4985.0  369.81  4991.3  369.81  4991.9  370.61  5012.9  370.95  5049.7  374.40
  5060.8  374.24  5138.4  375.37  5181.6  375.48  5211.8  376.20  5262.1  376.15
  5315.7  378.12  5463.4  379.04  5544.0  379.11  5660.3  380.64  5748.3  380.65
#Mann=4,-1,0
  4439.1     0.1       0  4747.6    0.05       0  4984.5    0.03       0
  4991.9    0.05       0
Bank Sta=4984.5,4991.9
Exp/Cntr=0.3,0.1

Type RM Length L Ch R = 1,3609,239,239,239
BEGIN DESCRIPTION:
UNT 048 in RCW 5.0
END DESCRIPTION:
XS GIS Cut Line= 3
      2044041.85     13442317.42      2043575.00     13442375.00
      2042943.74     13442523.59
#Sta/Elev= 30
  4519.3  384.15  4535.8  384.01  4540.8  383.42  4703.1  378.55  4794.0  376.42
  4828.5  375.65  4878.9  373.72  4909.1  372.02  4929.2  371.57  4939.3  370.95
  4946.6  369.79  4951.6  370.08  4959.5  368.94  4983.4  367.45  4984.0  366.65
  4990.4  366.65  4990.9  367.45  5013.4  367.73  5029.5  368.58  5050.7  370.93
  5055.8  371.09  5061.6  372.61  5082.1  373.77  5195.2  376.05  5277.9  377.03
  5410.9  377.42  5503.4  378.55  5532.1  378.32  5554.7  379.15  5638.2  379.69
#Mann=5,-1,0
  4519.3    0.05       0  4794.0     0.1       0  4983.4    0.07       0
  4990.9     0.1       0  5029.5    0.05       0
Bank Sta=4983.4,4990.9
Exp/Cntr=0.3,0.1

Type RM Length L Ch R = 1,3370,140,140,140
BEGIN DESCRIPTION:
Mapping XS 2cbf9249
END DESCRIPTION:
XS GIS Cut Line= 3
      2043963.71     13442167.68      2043403.84     13442141.64
      2042880.81     13442282.70
#Sta/Elev= 30
  4539.7  382.64  4638.5  379.84  4688.6  377.78  4800.8  374.94  4878.8  373.67
  4928.8  372.29  4958.9  372.01  4978.9  372.38  5029.6  371.76  5059.0  370.93
  5069.0  369.89  5075.2  368.46  5075.8  367.66  5082.2  367.66  5082.8  368.46
  5100.2  368.97  5109.3  370.28  5213.6  374.29  5243.2  373.82  5288.2  374.97
  5357.7  374.98  5378.6  375.59  5397.6  375.09  5437.6  375.06  5442.7  375.50
  5502.9  376.25  5534.0  377.49  5557.3  376.92  5592.0  377.57  5641.9  377.63
#Mann=5,-1,0
  4539.7    0.05       0  4800.8     0.1       0  5029.6    0.05       0
  5075.2    0.07       0  5082.8    0.05       0
Bank Sta=5075.2,5082.8
Exp/Cntr=0.3,0.1

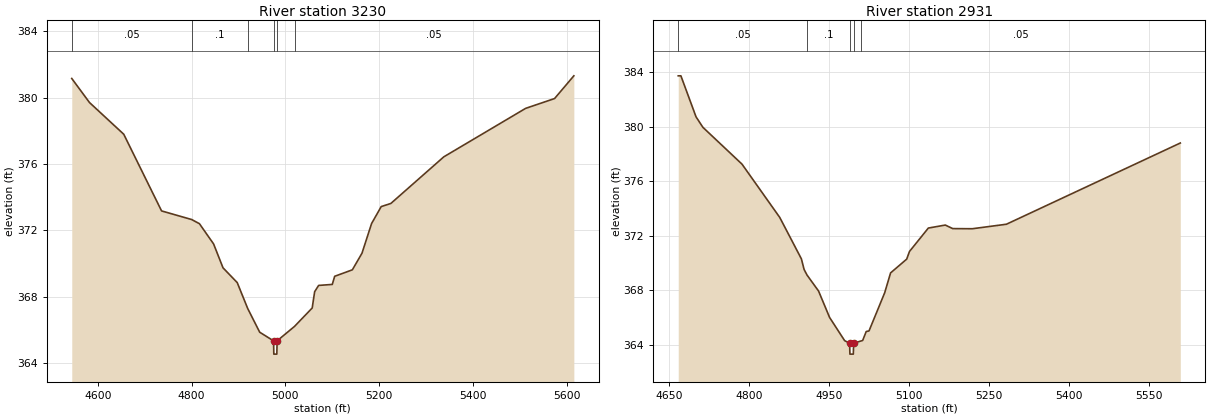
Type RM Length L Ch R = 1,3230,299,299,299
BEGIN DESCRIPTION:
UNT 048 in RCW 4.0
END DESCRIPTION:
XS GIS Cut Line= 3
      2043924.96     13442074.99      2043525.00     13442025.00
      2042874.96     13441874.99
#Sta/Elev= 30
  4544.7  381.15  4582.5  379.70  4655.5  377.79  4736.1  373.17  4800.3  372.65
  4816.8  372.40  4847.0  371.18  4867.1  369.74  4897.4  368.85  4919.7  367.29
  4945.3  365.86  4974.8  365.34  4975.4  364.54  4981.8  364.54  4982.4  365.34
  5019.5  366.21  5057.2  367.32  5062.4  368.30  5070.9  368.68  5100.0  368.74
  5105.1  369.23  5142.8  369.62  5163.3  370.62  5183.8  372.41  5204.3  373.43
  5224.9  373.62  5337.8  376.43  5512.2  379.35  5573.8  379.94  5614.9  381.31
#Mann=6,-1,0
  4544.7    0.05       0  4800.3     0.1       0  4919.7    0.07       0
  4974.8    0.07       0  4982.4    0.07       0  5019.5    0.05       0
Bank Sta=4974.8,4982.4
Exp/Cntr=0.3,0.1

Type RM Length L Ch R = 1,2931,0,0,0
BEGIN DESCRIPTION:
Mapping XS be120049
END DESCRIPTION:
XS GIS Cut Line= 3
      2043989.77     13441879.05      2043488.47     13441748.84
      2043066.49     13441709.89
#Sta/Elev= 30
  4667.5  383.73  4672.5  383.73  4700.9  380.72  4713.8  379.95  4787.1  377.25
  4857.9  373.34  4898.5  370.30  4903.6  369.52  4909.1  369.11  4930.7  367.94
  4951.4  366.00  4979.6  364.30  4988.9  364.11  4989.5  363.31  4995.9  363.31
  4996.5  364.11  5009.9  364.27  5013.4  364.31  5020.1  364.97  5025.3  365.01
  5054.7  367.81  5065.8  369.27  5096.0  370.28  5101.2  370.84  5136.6  372.56
  5168.4  372.78  5182.3  372.52  5219.0  372.51  5283.0  372.84  5609.2  378.80
#Mann=5,-1,0
  4667.5    0.05       0  4909.1     0.1       0  4988.9    0.07       0
  4996.5     0.1       0  5009.9    0.05       0
Bank Sta=4988.9,4996.5
Exp/Cntr=0.3,0.1

Chan Stop Cuts=-1