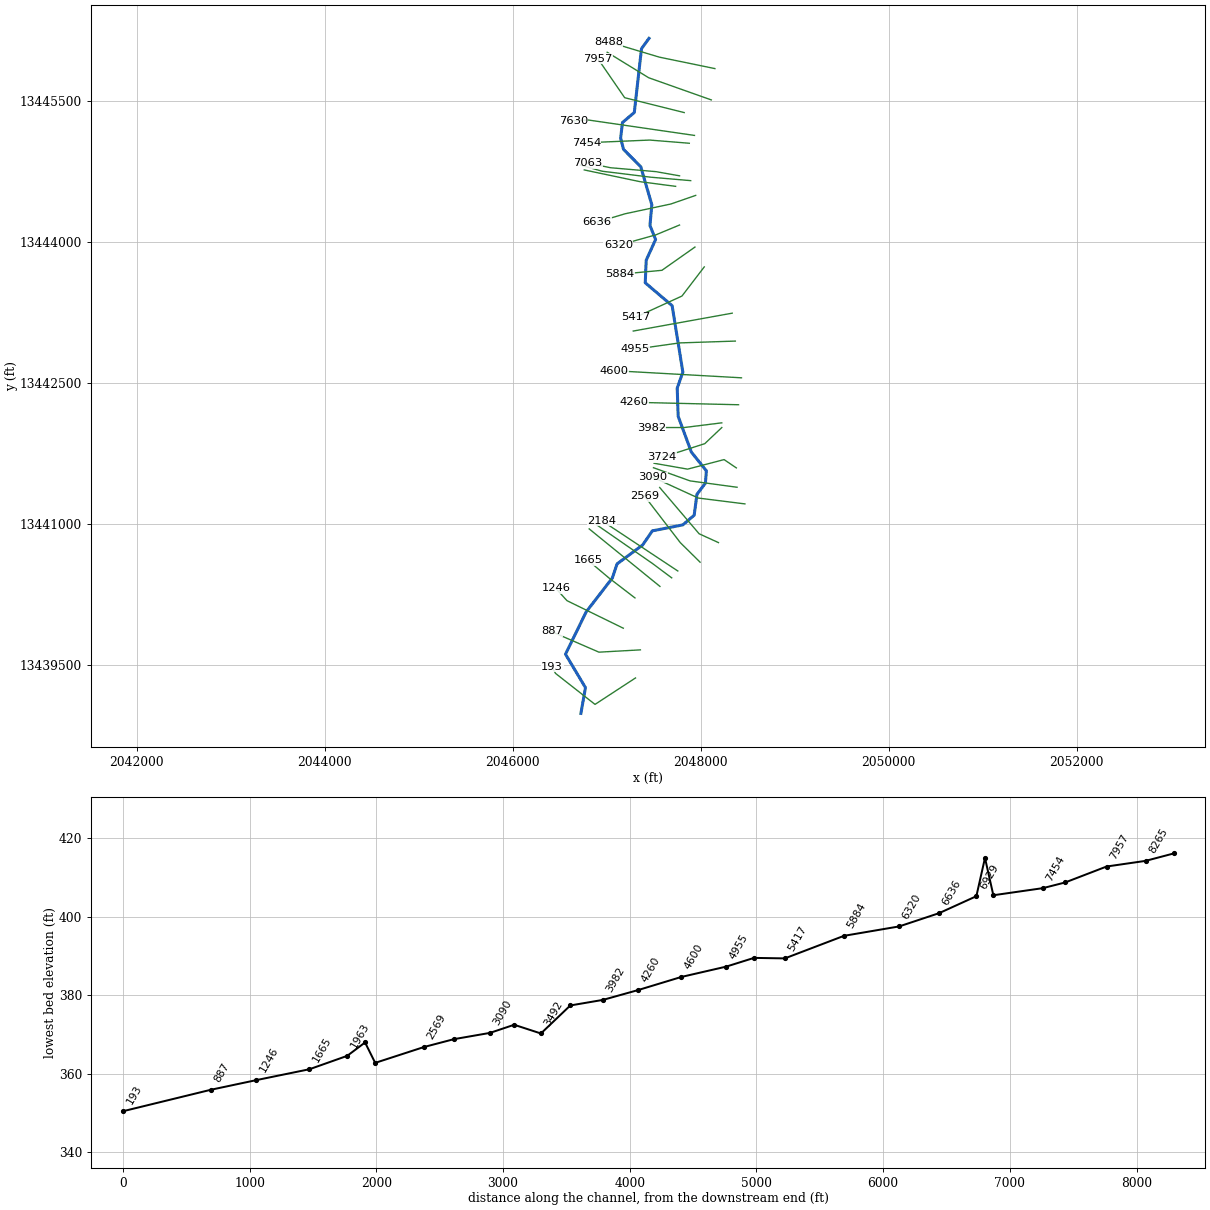
--- UNT 049 in RCW.prj (project) ---

Proj Title=UNT 049 in RCW Base Level Engineering
Current Plan=p01
Default Exp/Contr=0.3,0.1
English Units
Geom File=g01
Flow File=f01
Plan File=p01
BEGIN DESCRIPTION:
UNT 049 in RCW
END DESCRIPTION:

--- UNT 049 in RCW.p01 (plan) ---

Plan Title=Multiple Run
Short Identifier=Multiple
Geom File=g01
Flow File=f01
Subcritical Flow
K Sum by GR= 0
Std Step Tol= 0.01
Critical Tol= 0.01
Num of Std Step Trials= 20
Max Error Tol= 0.3
Flow Tol Ratio= 0.001
Split Flow NTrial= 30
Split Flow Tol= 0.02
Split Flow Ratio= 0.02
Log Output Level= 0
Friction Slope Method= 1
Unsteady Friction Slope Method= 2
Unsteady Bridges Friction Slope Method= 1
Parabolic Critical Depth
Global Vel Dist=  1 , 1 , 1
Global Log Level= 0
CheckData=True
Encroach Param= -1, 0, 0, 0
BEGIN DESCRIPTION:
Multiple Run
END DESCRIPTION:

--- UNT 049 in RCW.f01 (steady flow) ---

Flow Title=Multiple
Number of Profiles=7
Profile Names=10-year,25-year,50-year,1pct_min,100-year,1pct_plu,500-year
River Rch & RM= UNT 049 in RCW,Reach-1,8488
     174     237     289     176     351     700     524
River Rch & RM= UNT 049 in RCW,Reach-1,5417
     249     347     429     265     528    1053     812
Boundary for River Rch & Prof#=UNT 049 in RCW,Reach-1,1
Up Type=0
Dn Type=3
Dn Slope=0.005
Boundary for River Rch & Prof#=UNT 049 in RCW,Reach-1,2
Up Type=0
Dn Type=3
Dn Slope=0.005
Boundary for River Rch & Prof#=UNT 049 in RCW,Reach-1,3
Up Type=0
Dn Type=3
Dn Slope=0.005
Boundary for River Rch & Prof#=UNT 049 in RCW,Reach-1,4
Up Type=0
Dn Type=3
Dn Slope=0.005
Boundary for River Rch & Prof#=UNT 049 in RCW,Reach-1,5
Up Type=0
Dn Type=3
Dn Slope=0.005
Boundary for River Rch & Prof#=UNT 049 in RCW,Reach-1,6
Up Type=0
Dn Type=3
Dn Slope=0.005
Boundary for River Rch & Prof#=UNT 049 in RCW,Reach-1,7
Up Type=0
Dn Type=3
Dn Slope=0.005

--- UNT 049 in RCW.g01 (geometry) ---

Geom Title=Existing Conditions

River Reach=UNT 049 in RCW,Reach-1
Reach XY= 30
      2047450.80     13446164.54      2047370.80     13446054.54
      2047294.24     13445375.59      2047168.50     13445269.28
      2047148.97     13445103.26      2047179.76     13444983.50
      2047362.73     13444799.44      2047480.80     13444394.54
      2047460.80     13444174.54      2047520.80     13444024.54
      2047420.80     13443804.54      2047410.80     13443564.54
      2047696.54     13443321.14      2047810.80     13442614.54
      2047750.80     13442444.54      2047760.80     13442144.54
      2047900.80     13441764.54      2048060.80     13441564.54
      2048050.80     13441434.54      2047960.80     13441314.54
      2047930.92     13441091.98      2047810.26     13440989.55
      2047486.47     13440926.18      2047382.31     13440775.14
      2047110.80     13440574.54      2047060.80     13440424.54
      2046782.70     13440064.63      2046562.43     13439614.33
      2046775.10     13439258.43      2046726.30     13438984.86

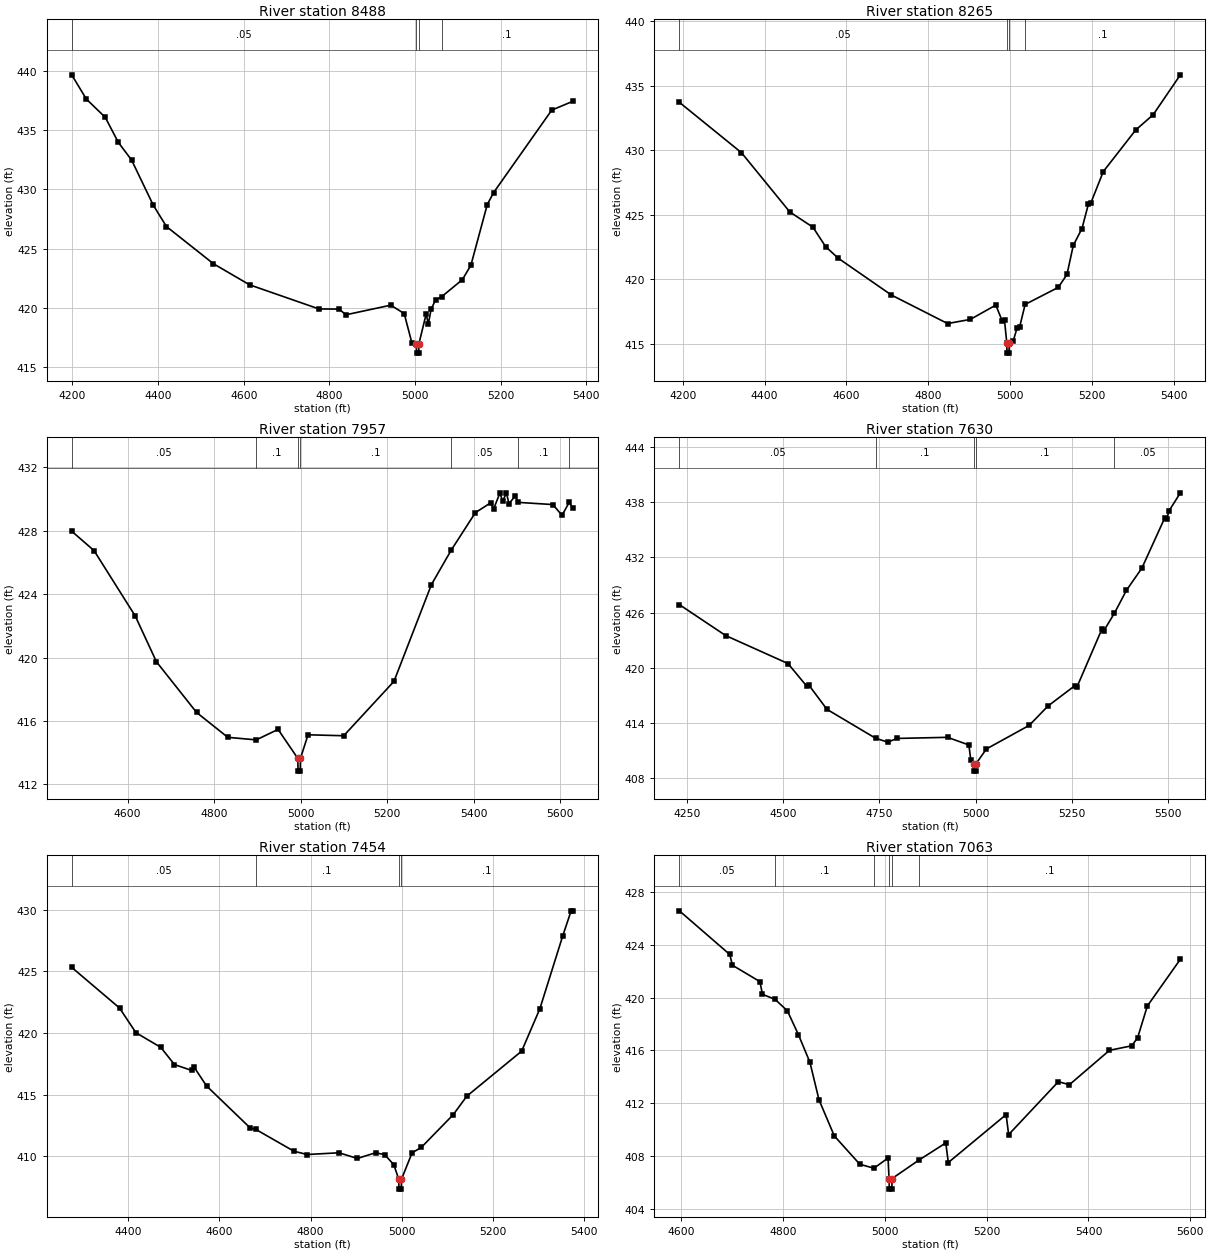
Type RM Length L Ch R = 1,8488,223,223,223
BEGIN DESCRIPTION:
UNT 049 in RCW 18.0
END DESCRIPTION:
XS GIS Cut Line= 3
      2048151.66     13445842.81      2047561.43     13445964.33
      2047018.16     13446126.96
#Sta/Elev= 30
  4198.4  439.68  4232.4  437.64  4276.7  436.09  4307.3  433.97  4338.1  432.49
  4389.0  428.66  4419.6  426.87  4529.2  423.73  4613.6  421.95  4775.7  419.91
  4822.1  419.90  4839.0  419.42  4943.4  420.23  4974.7  419.52  4992.8  417.02
  5003.1  416.98  5003.6  416.18  5008.6  416.18  5009.1  416.98  5025.9  419.47
  5031.1  418.65  5037.4  419.87  5047.8  420.67  5062.3  420.95  5110.4  422.38
  5130.4  423.60  5168.7  428.73  5183.5  429.74  5319.2  436.70  5368.1  437.44
#Mann=4,-1,0
  4198.4    0.05       0  5003.1    0.03       0  5009.1    0.05       0
  5062.3     0.1       0
Bank Sta=5003.1,5009.1
Exp/Cntr=0.3,0.1

Type RM Length L Ch R = 1,8265,308,308,308
BEGIN DESCRIPTION:
Mapping XS 28df773b
END DESCRIPTION:
XS GIS Cut Line= 3
      2048113.49     13445509.47      2047446.85     13445745.58
      2047005.89     13446016.40
#Sta/Elev= 30
  4191.8  433.70  4343.6  429.80  4461.8  425.21  4518.3  424.03  4549.2  422.53
  4580.1  421.63  4710.0  418.78  4847.5  416.57  4903.0  416.89  4965.3  418.00
  4980.7  416.80  4986.6  416.83  4992.1  415.08  4992.6  414.28  4997.6  414.28
  4998.1  415.08  5007.8  415.21  5017.4  416.24  5023.3  416.27  5037.0  418.05
  5118.0  419.37  5139.3  420.37  5154.7  422.62  5176.0  423.93  5191.4  425.79
  5197.3  425.88  5228.1  428.34  5307.4  431.56  5350.0  432.74  5416.5  435.83
#Mann=4,-1,0
  4191.8    0.05       0  4992.1    0.03       0  4998.1    0.05       0
  5037.0     0.1       0
Bank Sta=4992.1,4998.1
Exp/Cntr=0.3,0.1

Type RM Length L Ch R = 1,7957,327,327,327
BEGIN DESCRIPTION:
UNT 049 in RCW 17.0
END DESCRIPTION:
XS GIS Cut Line= 3
      2047825.03     13445374.99      2047192.03     13445533.06
      2046905.56     13445949.74
#Sta/Elev= 30
  4470.8  427.96  4522.4  426.74  4617.8  422.61  4666.7  419.73  4759.4  416.54
  4831.6  414.97  4897.4  414.81  4947.8  415.47  4993.5  413.64  4994.0  412.84
  4999.0  412.84  4999.5  413.64  5017.1  415.13  5099.6  415.07  5215.8  418.50
  5302.4  424.60  5348.1  426.77  5403.9  429.13  5439.8  429.76  5445.9  429.35
  5460.8  430.38  5466.8  429.85  5475.7  430.37  5481.7  429.69  5496.6  430.21
  5501.8  429.78  5583.2  429.64  5604.2  428.96  5621.3  429.80  5628.9  429.40
#Mann=7,-1,0
  4470.8    0.05       0  4897.4     0.1       0  4993.5    0.07       0
  4999.5     0.1       0  5348.1    0.05       0  5501.8     0.1       0
  5621.3    0.05       0
Bank Sta=4993.5,4999.5
Exp/Cntr=0.3,0.1

Type RM Length L Ch R = 1,7630,176,176,176
BEGIN DESCRIPTION:
Mapping XS 8d083235
END DESCRIPTION:
XS GIS Cut Line= 3
      2047934.20     13445132.02      2046804.01     13445296.08
      2046645.13     13445288.27
#Sta/Elev= 30
  4230.5  426.86  4350.8  423.50  4512.6  420.46  4561.3  418.00  4566.3  418.15
  4613.7  415.49  4740.5  412.34  4771.8  411.93  4795.6  412.33  4926.9  412.45
  4982.3  411.62  4987.5  409.94  4994.7  409.58  4995.2  408.78  5000.2  408.78
  5000.7  409.58  5028.0  411.19  5139.1  413.75  5187.8  415.85  5258.0  418.07
  5263.0  417.91  5328.1  424.23  5333.2  424.05  5360.1  425.91  5391.6  428.42
  5431.6  430.82  5491.5  436.32  5496.5  436.15  5501.7  437.01  5531.6  439.00
#Mann=5,-1,0
  4230.5    0.05       0  4740.5     0.1       0  4994.7    0.07       0
  5000.7     0.1       0  5360.1    0.05       0
Bank Sta=4994.7,5000.7
Exp/Cntr=0.3,0.1

Type RM Length L Ch R = 1,7454,391,391,391
BEGIN DESCRIPTION:
UNT 049 in RCW 16.0
END DESCRIPTION:
XS GIS Cut Line= 3
      2047879.55     13445048.68      2047457.66     13445082.54
      2046783.21     13445053.89
#Sta/Elev= 30
  4276.4  425.33  4381.3  422.03  4417.1  420.03  4471.6  418.84  4501.7  417.44
  4539.8  416.96  4544.9  417.22  4571.9  415.71  4667.6  412.30  4679.9  412.18
  4763.4  410.41  4792.4  410.14  4862.5  410.28  4902.5  409.82  4942.5  410.28
  4962.5  410.13  4982.6  409.31  4993.3  408.13  4993.8  407.33  4998.8  407.33
  4999.3  408.13  5022.6  410.28  5042.6  410.71  5112.7  413.37  5142.7  414.88
  5262.8  418.53  5302.8  421.98  5352.9  427.89  5371.3  429.92  5374.7  429.92
#Mann=4,-1,0
  4276.4    0.05       0  4679.9     0.1       0  4993.3    0.07       0
  4999.3     0.1       0
Bank Sta=4993.3,4999.3
Exp/Cntr=0.3,0.1

Type RM Length L Ch R = 1,7063,66,66,66
BEGIN DESCRIPTION:
UNT 049 in RCW 15.0
END DESCRIPTION:
XS GIS Cut Line= 4
      2047775.39     13444702.32      2047525.36     13444746.60
      2047040.99     13444788.27      2046801.42     13444837.74
#Sta/Elev= 30
  4595.9  426.55  4695.0  423.25  4700.1  422.44  4754.2  421.20  4759.2  420.24
  4784.0  419.86  4808.2  418.99  4829.9  417.19  4852.5  415.10  4870.3  412.27
  4900.4  409.54  4950.5  407.40  4978.3  407.10  5006.0  407.87  5008.0  406.32
  5008.5  405.52  5013.5  405.52  5014.0  406.32  5066.2  407.70  5119.5  409.01
  5124.5  407.53  5238.1  411.15  5243.1  409.64  5340.8  413.64  5362.5  413.41
  5441.3  416.01  5485.0  416.35  5496.6  416.96  5515.7  419.36  5580.6  422.89
#Mann=6,-1,0
  4595.9    0.05       0  4784.0     0.1       0  4978.3    0.05       0
  5008.0   0.033       0  5014.0    0.05       0  5066.2     0.1       0
Bank Sta=5008,5014
Exp/Cntr=0.3,0.1

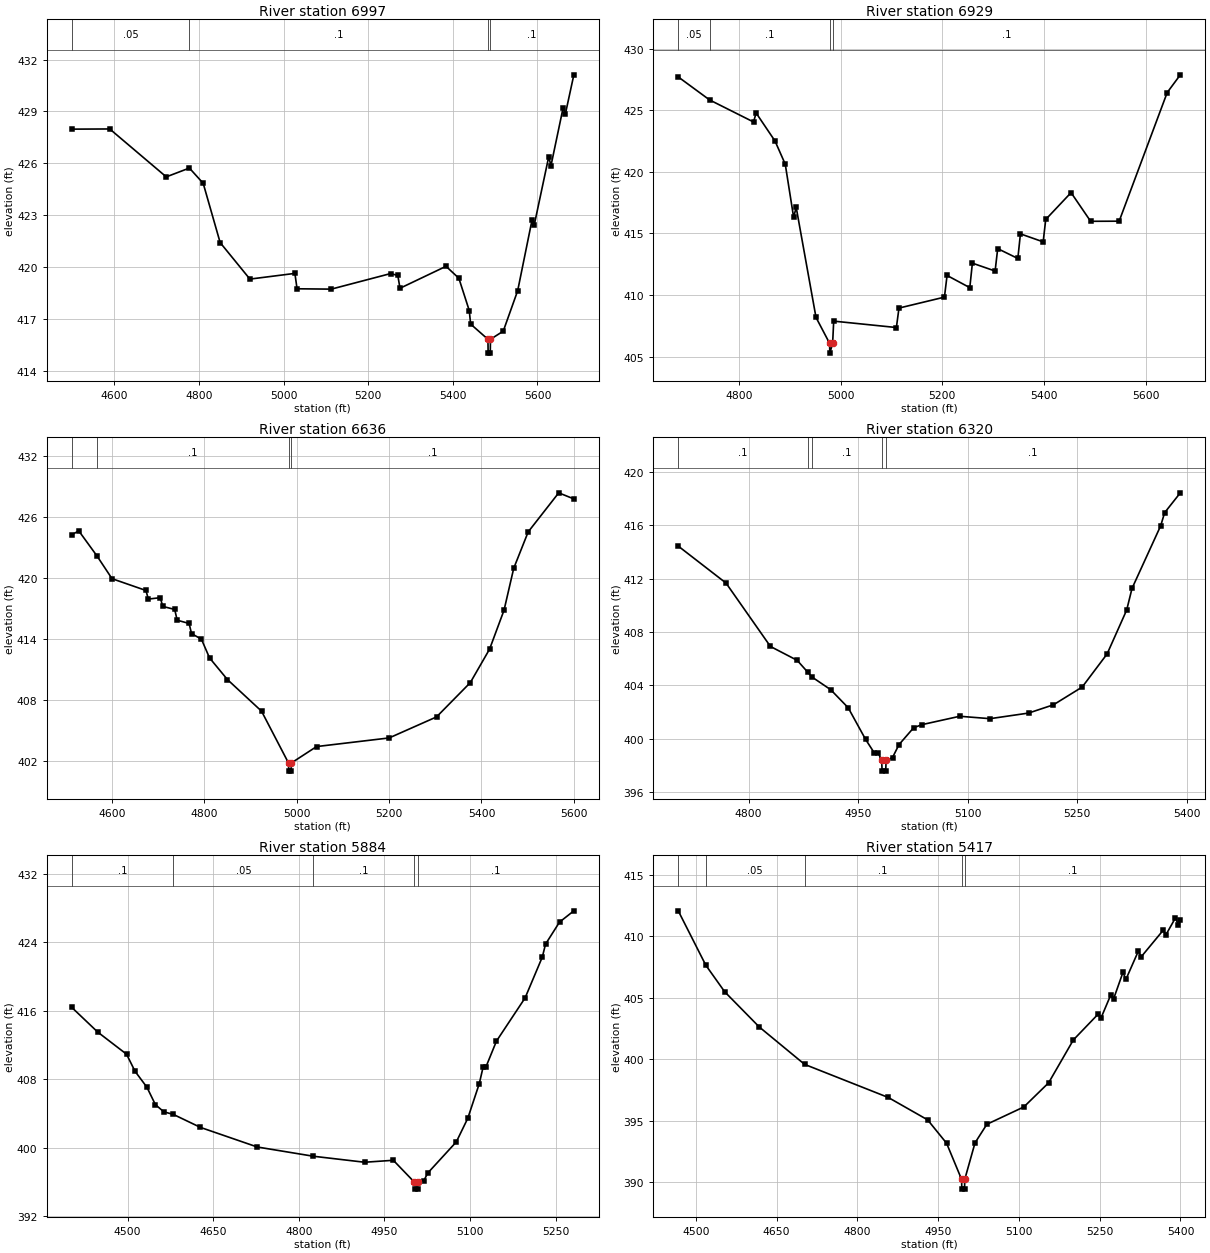
Type RM Length L Ch R = 1,6997,68,68,68
BEGIN DESCRIPTION:
Mapping XS 3e581968
END DESCRIPTION:
XS GIS Cut Line= 5
      2047894.34     13444650.96      2047466.81     13444687.85
      2047169.50     13444724.75      2046954.66     13444750.79
      2046722.44     13444815.89
#Sta/Elev= 30
  4499.7  427.98  4589.4  427.99  4723.0  425.22  4777.6  425.73  4810.2  424.85
  4850.3  421.42  4920.6  419.31  5026.9  419.64  5032.0  418.75  5112.9  418.73
  5253.1  419.63  5270.1  419.52  5275.2  418.78  5384.0  420.05  5414.3  419.36
  5438.9  417.49  5442.1  416.71  5483.0  415.83  5483.5  415.03  5488.5  415.03
  5489.0  415.83  5519.2  416.30  5553.3  418.64  5587.4  422.75  5592.6  422.46
  5626.7  426.39  5631.9  425.86  5660.8  429.23  5666.0  428.86  5686.0  431.12
#Mann=4,-1,0
  4499.7    0.05       0  4777.6     0.1       0  5483.0    0.07       0
  5489.0     0.1       0
Bank Sta=5483,5489
Exp/Cntr=0.3,0.1

Type RM Length L Ch R = 1,6929,293,293,293
BEGIN DESCRIPTION:
UNT 049 in RCW 14.0
END DESCRIPTION:
XS GIS Cut Line= 3
      2047733.75     13444590.34      2047356.09     13444639.83
      2046762.39     13444764.82
#Sta/Elev= 30
  4680.8  427.72  4742.5  425.85  4828.9  424.06  4834.0  424.79  4871.2  422.51
  4891.3  420.63  4907.8  416.31  4912.8  417.13  4951.8  408.18  4978.5  406.08
  4979.0  405.28  4984.5  406.08  4986.6  407.88  5109.9  407.36  5115.0  408.94
  5204.4  409.83  5209.6  411.59  5254.3  410.60  5259.4  412.59  5304.1  411.95
  5309.2  413.77  5348.8  412.97  5353.9  414.97  5398.6  414.32  5403.7  416.14
  5453.5  418.32  5492.0  415.99  5548.1  416.00  5642.6  426.45  5668.4  427.89
#Mann=4,-1,0
  4680.8    0.05       0  4742.5     0.1       0  4978.5    0.07       0
  4984.5     0.1       0
Bank Sta=4978.5,4984.5
Exp/Cntr=0.3,0.1

Type RM Length L Ch R = 1,6636,316,316,316
BEGIN DESCRIPTION:
Mapping XS 270ae363
END DESCRIPTION:
XS GIS Cut Line= 4
      2047947.25     13444494.00      2047684.22     13444402.85
      2047197.24     13444298.68      2046900.34     13444210.13
#Sta/Elev= 30
  4513.6  424.26  4528.8  424.64  4568.0  422.18  4600.7  419.93  4674.0  418.77
  4679.3  417.92  4705.1  418.06  4710.4  417.20  4736.3  416.90  4741.6  415.84
  4767.4  415.52  4772.7  414.52  4794.1  413.97  4811.6  412.13  4850.4  409.99
  4924.1  406.88  4982.5  401.77  4983.0  400.97  4988.0  400.97  4988.5  401.77
  5043.2  403.39  5200.2  404.24  5302.7  406.31  5375.8  409.69  5417.5  412.99
  5448.8  416.83  5469.7  420.95  5501.0  424.54  5567.1  428.39  5599.8  427.79
#Mann=4,-1,0
  4513.6    0.05       0  4568.0     0.1       0  4982.5    0.07       0
  4988.5     0.1       0
Bank Sta=4982.5,4988.5
Exp/Cntr=0.3,0.1

Type RM Length L Ch R = 1,6320,436,436,436
BEGIN DESCRIPTION:
UNT 049 in RCW 13.0
END DESCRIPTION:
XS GIS Cut Line= 3
      2047775.37     13444178.89      2047525.00     13444075.00
      2047124.30     13443962.74
#Sta/Elev= 30
  4703.8  414.44  4769.2  411.67  4830.0  406.92  4866.6  405.88  4881.1  404.99
  4886.6  404.64  4912.5  403.68  4936.4  402.33  4960.2  399.96  4972.2  398.94
  4977.5  398.94  4982.3  398.38  4982.8  397.58  4987.8  397.58  4988.3  398.38
  4997.1  398.60  5006.0  399.57  5026.0  400.83  5037.2  401.06  5089.1  401.69
  5130.6  401.51  5183.3  401.93  5217.4  402.55  5256.7  403.88  5290.8  406.36
  5317.6  409.65  5324.9  411.27  5364.2  415.97  5369.5  416.94  5391.0  418.43
#Mann=5,-1,0
  4703.8     0.1       0  4881.1    0.05       0  4886.6     0.1       0
  4982.3    0.07       0  4988.3     0.1       0
Bank Sta=4982.3,4988.3
Exp/Cntr=0.3,0.1

Type RM Length L Ch R = 1,5884,467,467,467
BEGIN DESCRIPTION:
UNT 049 in RCW 12.0
END DESCRIPTION:
XS GIS Cut Line= 3
      2047939.45     13443944.53      2047587.86     13443697.12
      2047140.01     13443655.46
#Sta/Elev= 30
  4402.3  416.41  4447.7  413.53  4498.3  410.94  4513.1  408.95  4534.0  407.08
  4548.8  405.05  4563.6  404.21  4580.2  403.91  4627.8  402.39  4727.4  400.10
  4825.8  399.02  4915.4  398.32  4965.7  398.55  5002.8  395.98  5003.3  395.18
  5008.3  395.18  5008.8  395.98  5019.0  396.14  5025.9  397.05  5076.1  400.70
  5096.2  403.46  5116.3  407.50  5123.2  409.49  5128.2  409.49  5146.4  412.47
  5196.6  417.52  5226.8  422.30  5232.4  423.80  5256.9  426.37  5282.0  427.69
#Mann=5,-1,0
  4402.3     0.1       0  4580.2    0.05       0  4825.8     0.1       0
  5002.8    0.07       0  5008.8     0.1       0
Bank Sta=5002.8,5008.8
Exp/Cntr=0.3,0.1

Type RM Length L Ch R = 1,5417,243,243,243
BEGIN DESCRIPTION:
UNT 049 in RCW 11.0
END DESCRIPTION:
XS GIS Cut Line= 3
      2048038.39     13443733.59      2047801.41     13443423.68
      2047308.27     13443197.88
#Sta/Elev= 30
  4467.2  412.05  4518.4  407.63  4553.5  405.47  4617.7  402.61  4701.9  399.57
  4857.3  396.88  4930.4  395.06  4965.6  393.16  4993.4  390.23  4993.9  389.43
  4998.9  389.43  4999.4  390.23  5018.4  393.19  5040.4  394.70  5109.1  396.11
  5155.1  398.07  5201.1  401.56  5247.2  403.66  5252.7  403.37  5270.2  405.18
  5275.7  404.88  5293.2  407.05  5298.7  406.48  5321.7  408.77  5327.2  408.32
  5367.7  410.46  5373.2  410.12  5390.7  411.48  5396.2  410.88  5399.7  411.29
#Mann=5,-1,0
  4467.2     0.1       0  4518.4    0.05       0  4701.9     0.1       0
  4993.4    0.07       0  4999.4     0.1       0
Bank Sta=4993.4,4999.4
Exp/Cntr=0.3,0.1

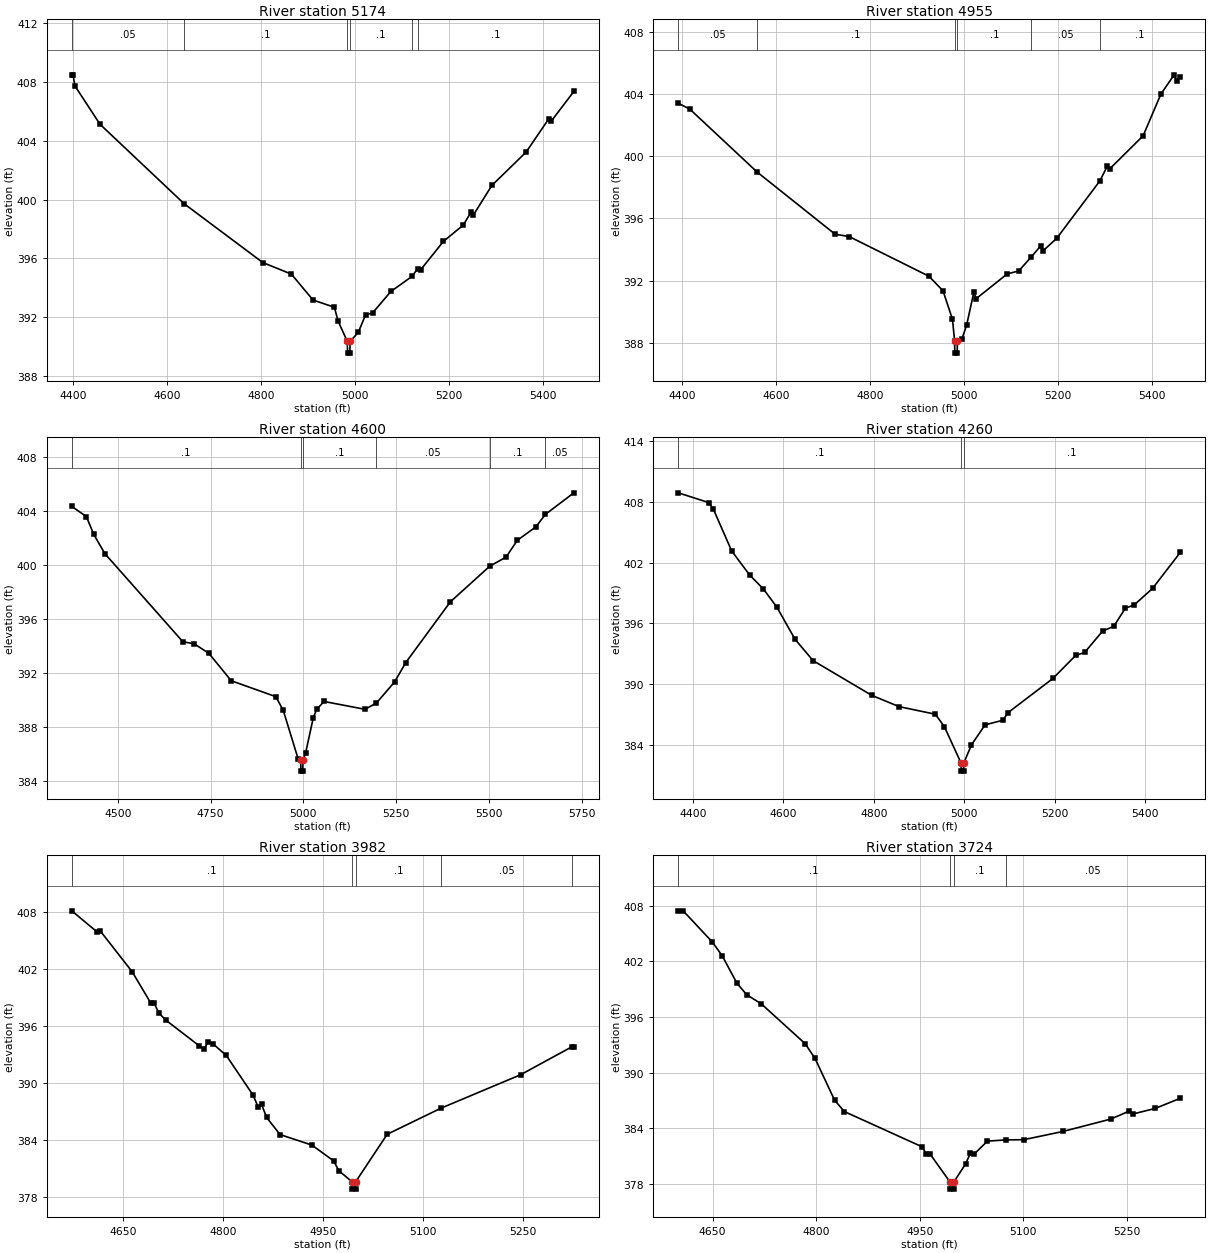
Type RM Length L Ch R = 1,5174,219,219,219
BEGIN DESCRIPTION:
Mapping XS 70d7a460
END DESCRIPTION:
XS GIS Cut Line= 2
      2048335.26     13443241.39      2047283.19     13443051.29
#Sta/Elev= 30
  4396.4  408.48  4399.1  408.48  4403.0  407.73  4456.5  405.12  4635.9  399.71
  4803.1  395.72  4864.1  394.93  4910.1  393.17  4955.6  392.68  4963.6  391.73
  4983.1  390.36  4983.6  389.56  4988.6  389.56  4989.1  390.36  5006.4  390.97
  5022.2  392.17  5036.9  392.29  5075.8  393.75  5121.5  394.79  5132.9  395.31
  5139.4  395.23  5187.9  397.16  5229.9  398.26  5246.5  399.14  5251.6  398.95
  5290.9  400.96  5363.7  403.22  5412.1  405.49  5417.2  405.32  5465.5  407.35
#Mann=6,-1,0
  4396.4    0.05       0  4635.9     0.1       0  4983.1    0.07       0
  4989.1     0.1       0  5121.5    0.05       0  5132.9     0.1       0
Bank Sta=4983.1,4989.1
Exp/Cntr=0.3,0.1

Type RM Length L Ch R = 1,4955,355,355,355
BEGIN DESCRIPTION:
UNT 049 in RCW 10.0
END DESCRIPTION:
XS GIS Cut Line= 3
      2048369.14     13442944.52      2047775.00     13442925.00
      2047304.02     13442858.58
#Sta/Elev= 30
  4391.2  403.39  4415.4  403.03  4559.5  398.97  4725.5  394.98  4755.5  394.83
  4925.6  392.28  4955.6  391.34  4975.7  389.51  4980.2  388.14  4980.7  387.34
  4985.7  387.34  4986.2  388.14  4995.8  388.25  5005.9  389.14  5021.2  391.25
  5026.3  390.84  5092.4  392.43  5116.9  392.62  5143.6  393.52  5163.5  394.22
  5168.6  393.91  5197.7  394.71  5290.0  398.41  5305.8  399.36  5310.9  399.18
  5382.0  401.30  5419.9  403.98  5448.1  405.22  5453.2  404.83  5461.3  405.10
#Mann=6,-1,0
  4391.2    0.05       0  4559.5     0.1       0  4980.2    0.07       0
  4986.2     0.1       0  5143.6    0.05       0  5290.0     0.1       0
Bank Sta=4980.2,4986.2
Exp/Cntr=0.3,0.1

Type RM Length L Ch R = 1,4600,340,340,340
BEGIN DESCRIPTION:
Mapping XS 2dafc266
END DESCRIPTION:
XS GIS Cut Line= 2
      2048434.23     13442553.89      2047082.63     13442629.41
#Sta/Elev= 30
  4375.6  404.35  4414.9  403.60  4434.9  402.27  4465.0  400.84  4675.3  394.30
  4705.3  394.16  4745.4  393.44  4805.5  391.41  4925.7  390.23  4945.7  389.22
  4985.8  385.62  4992.8  385.50  4993.3  384.70  4998.3  384.70  4998.8  385.50
  5005.8  386.01  5026.8  388.67  5035.9  389.28  5055.9  389.87  5166.1  389.29
  5196.9  389.75  5246.2  391.33  5276.2  392.76  5396.4  397.27  5502.9  399.92
  5546.6  400.59  5576.7  401.83  5626.8  402.83  5652.6  403.76  5729.3  405.36
#Mann=6,-1,0
  4375.6     0.1       0  4992.8    0.07       0  4998.8     0.1       0
  5196.9    0.05       0  5502.9     0.1       0  5652.6    0.05       0
Bank Sta=4992.8,4998.8
Exp/Cntr=0.3,0.1

Type RM Length L Ch R = 1,4260,278,278,278
BEGIN DESCRIPTION:
Mapping XS c01167a9
END DESCRIPTION:
XS GIS Cut Line= 2
      2048402.92     13442267.43      2047293.63     13442293.47
#Sta/Elev= 30
  4367.7  408.90  4435.6  407.93  4445.6  407.26  4485.7  403.16  4525.7  400.76
  4555.7  399.40  4585.7  397.59  4625.7  394.42  4665.7  392.30  4795.7  388.86
  4855.8  387.75  4935.8  387.00  4955.8  385.78  4992.7  382.17  4993.2  381.37
  4998.3  381.37  4998.8  382.17  5015.8  383.97  5045.8  385.95  5085.8  386.41
  5095.8  387.13  5195.9  390.54  5245.9  392.81  5265.9  393.11  5305.9  395.24
  5330.1  395.69  5355.9  397.48  5375.9  397.83  5415.9  399.44  5477.3  403.01
#Mann=3,-1,0
  4367.7     0.1       0  4992.7    0.07       0  4998.8     0.1       0
Bank Sta=4992.7,4998.8
Exp/Cntr=0.3,0.1

Type RM Length L Ch R = 1,3982,258,258,258
BEGIN DESCRIPTION:
UNT 049 in RCW 8.0
END DESCRIPTION:
XS GIS Cut Line= 3
      2048224.99     13442075.00      2047825.00     13442025.00
      2047475.00     13442025.00
#Sta/Elev= 30
  4572.7  408.14  4610.5  405.93  4615.5  406.02  4663.4  401.72  4691.1  398.45
  4696.1  398.43  4703.7  397.36  4713.8  396.64  4764.2  393.92  4771.7  393.64
  4776.8  394.31  4784.3  394.16  4804.5  392.92  4844.8  388.73  4852.3  387.49
  4857.4  387.77  4864.9  386.41  4885.1  384.60  4933.0  383.49  4965.7  381.82
  4973.3  380.79  4992.7  379.66  4993.2  378.86  4998.3  378.86  4998.8  379.66
  5045.8  384.63  5126.3  387.37  5245.8  390.89  5323.3  393.85  5325.8  393.85
#Mann=5,-1,0
  4572.7     0.1       0  4992.7    0.07       0  4998.8     0.1       0
  5126.3    0.05       0  5323.3     0.1       0
Bank Sta=4992.7,4998.8
Exp/Cntr=0.3,0.1

Type RM Length L Ch R = 1,3724,232,232,232
BEGIN DESCRIPTION:
UNT 049 in RCW 7.0
END DESCRIPTION:
XS GIS Cut Line= 3
      2048225.03     13442025.03      2048043.59     13441853.37
      2047588.97     13441707.89
#Sta/Elev= 30
  4600.3  407.46  4607.4  407.46  4649.9  404.08  4664.1  402.59  4685.1  399.68
  4699.3  398.42  4720.7  397.42  4784.2  393.12  4798.4  391.54  4826.7  387.04
  4840.8  385.81  4953.6  382.00  4959.2  381.26  4964.5  381.28  4993.6  378.24
  4994.1  377.44  4999.2  377.44  4999.7  378.24  5016.6  380.18  5023.5  381.35
  5028.8  381.22  5048.1  382.62  5075.2  382.75  5100.6  382.77  5157.4  383.66
  5226.9  385.00  5253.8  385.87  5259.1  385.55  5291.2  386.15  5327.4  387.24
#Mann=4,-1,0
  4600.3     0.1       0  4993.6    0.07       0  4999.7     0.1       0
  5075.2    0.05       0
Bank Sta=4993.6,4999.7
Exp/Cntr=0.3,0.1

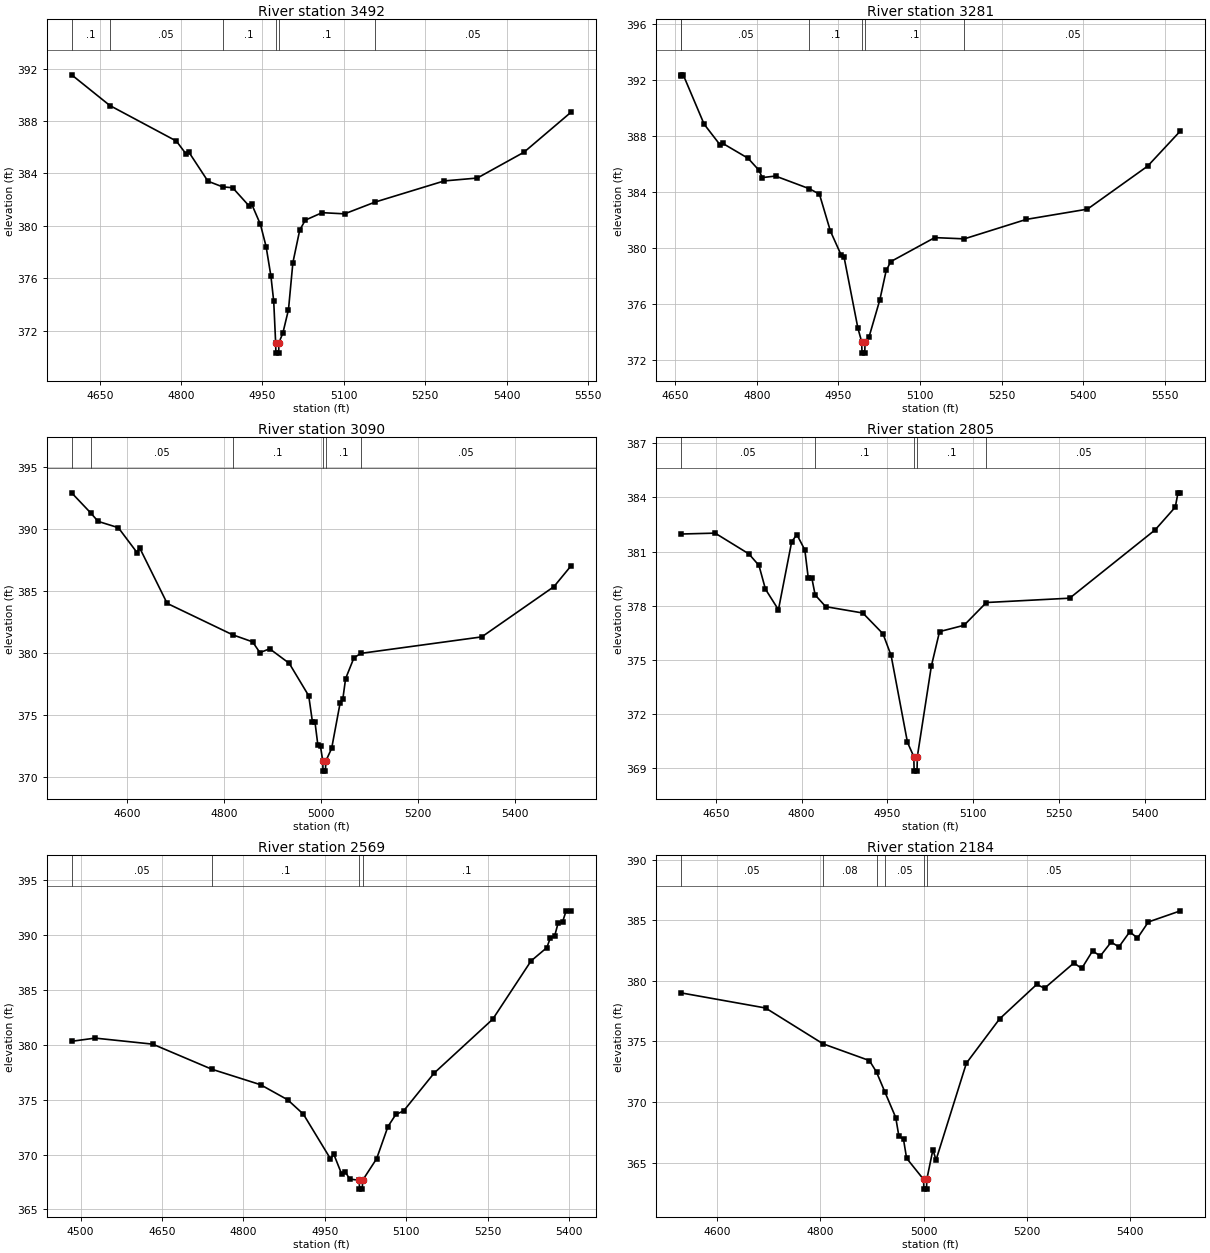
Type RM Length L Ch R = 1,3492,211,211,211
BEGIN DESCRIPTION:
Mapping XS 2b535d10
END DESCRIPTION:
XS GIS Cut Line= 4
      2048379.56     13441595.54      2048249.32     13441684.10
      2047861.30     13441582.54      2047504.52     13441645.04
#Sta/Elev= 30
  4598.3  391.52  4668.7  389.18  4791.3  386.47  4809.1  385.49  4814.3  385.63
  4849.5  383.41  4876.4  382.98  4895.1  382.91  4925.2  381.53  4930.4  381.64
  4946.3  380.11  4956.7  378.43  4965.6  376.18  4970.8  374.24  4974.3  371.10
  4974.8  370.30  4979.9  370.30  4980.4  371.10  4987.7  371.84  4998.0  373.62
  5006.1  377.20  5018.7  379.68  5029.0  380.44  5060.0  381.01  5101.4  380.92
  5157.8  381.82  5285.1  383.43  5346.0  383.65  5432.1  385.62  5519.1  388.68
#Mann=6,-1,0
  4598.3     0.1       0  4668.7    0.05       0  4876.4     0.1       0
  4974.3    0.07       0  4980.4     0.1       0  5157.8    0.05       0
Bank Sta=4974.3,4980.4
Exp/Cntr=0.3,0.1

Type RM Length L Ch R = 1,3281,191,191,191
BEGIN DESCRIPTION:
Mapping XS 0b7d6102
END DESCRIPTION:
XS GIS Cut Line= 3
      2048387.33     13441389.83      2047887.34     13441457.54
      2047498.33     13441597.58
#Sta/Elev= 30
  4660.4  392.32  4661.5  392.33  4664.7  392.37  4703.1  388.85  4732.3  387.38
  4737.3  387.48  4783.8  386.42  4804.0  385.56  4809.9  385.04  4834.3  385.15
  4896.2  384.25  4915.0  383.86  4935.2  381.22  4955.0  379.51  4960.1  379.40
  4985.7  374.30  4992.7  373.32  4993.2  372.52  4998.3  372.52  4998.8  373.32
  5005.9  373.64  5026.0  376.32  5037.7  378.42  5046.2  379.05  5126.9  380.76
  5181.2  380.67  5295.3  382.06  5407.5  382.79  5518.2  385.86  5578.4  388.37
#Mann=6,-1,0
  4660.4     0.1       0  4661.5    0.05       0  4896.2     0.1       0
  4992.7    0.07       0  4998.8     0.1       0  5181.2    0.05       0
Bank Sta=4992.7,4998.8
Exp/Cntr=0.3,0.1

Type RM Length L Ch R = 1,3090,285,285,285
BEGIN DESCRIPTION:
UNT 049 in RCW 6.0
END DESCRIPTION:
XS GIS Cut Line= 3
      2048470.68     13441212.74      2047975.00     13441275.00
      2047491.54     13441496.59
#Sta/Elev= 30
  4484.8  392.88  4523.9  391.27  4539.4  390.58  4581.2  390.07  4619.9  388.06
  4624.9  388.47  4682.0  383.97  4817.1  381.44  4858.4  380.87  4873.5  380.00
  4893.7  380.31  4934.0  379.14  4974.3  376.52  4981.9  374.43  4987.1  374.43
  4993.1  372.57  4998.6  372.45  5003.3  371.25  5003.8  370.45  5008.9  370.45
  5009.4  371.25  5021.6  372.28  5039.1  375.94  5044.6  376.23  5050.4  377.90
  5067.6  379.58  5081.8  379.94  5331.6  381.27  5480.6  385.32  5516.2  387.01
#Mann=6,-1,0
  4484.8     0.1       0  4523.9    0.05       0  4817.1     0.1       0
  5003.3    0.07       0  5009.4     0.1       0  5081.8    0.05       0
Bank Sta=5003.3,5009.4
Exp/Cntr=0.3,0.1

Type RM Length L Ch R = 1,2805,236,236,236
BEGIN DESCRIPTION:
Mapping XS 6c68d767
END DESCRIPTION:
XS GIS Cut Line= 3
      2048189.40     13440801.30      2047983.70     13440895.04
      2047564.43     13441387.22
#Sta/Elev= 30
  4589.1  381.97  4648.9  382.02  4707.9  380.87  4725.5  380.23  4736.8  378.92
  4759.5  377.78  4782.6  381.54  4791.7  381.94  4805.6  381.09  4811.7  379.51
  4818.0  379.51  4823.6  378.60  4842.1  377.95  4906.9  377.60  4942.1  376.45
  4956.3  375.25  4984.9  370.44  4996.0  369.65  4996.5  368.85  5001.6  368.85
  5002.1  369.65  5026.6  374.66  5040.9  376.57  5083.7  376.92  5122.7  378.18
  5268.2  378.42  5417.5  382.20  5452.7  383.46  5457.4  384.25  5461.7  384.25
#Mann=5,-1,0
  4589.1    0.05       0  4823.6     0.1       0  4996.0    0.07       0
  5002.1     0.1       0  5122.7    0.05       0
Bank Sta=4996,5002.1
Exp/Cntr=0.3,0.1

Type RM Length L Ch R = 1,2569,385,385,385
BEGIN DESCRIPTION:
UNT 049 in RCW 5.0
END DESCRIPTION:
XS GIS Cut Line= 3
      2047994.13     13440592.94      2047783.18     13440801.29
      2047402.97     13441296.08
#Sta/Elev= 30
  4483.6  380.30  4526.8  380.59  4633.0  380.04  4741.8  377.76  4831.7  376.35
  4881.6  374.98  4910.6  373.67  4960.4  369.62  4966.7  370.02  4981.3  368.20
  4987.6  368.45  4995.8  367.77  5013.5  367.65  5014.0  366.85  5019.2  366.85
  5019.7  367.65  5045.6  369.62  5066.4  372.54  5080.9  373.64  5095.4  373.97
  5151.6  377.41  5259.5  382.31  5330.1  387.61  5359.2  388.82  5365.5  389.69
  5373.7  389.90  5380.0  391.06  5388.2  391.16  5394.5  392.13  5404.1  392.17
#Mann=4,-1,0
  4483.6    0.05       0  4741.8     0.1       0  5013.5    0.07       0
  5019.7     0.1       0
Bank Sta=5013.5,5019.7
Exp/Cntr=0.3,0.1

Type RM Length L Ch R = 1,2184,80,80,80
BEGIN DESCRIPTION:
Mapping XS d498f4f4
END DESCRIPTION:
XS GIS Cut Line= 2
      2047757.10     13440499.23      2046948.58     13441034.77
#Sta/Elev= 30
  4529.0  379.01  4693.4  377.76  4805.1  374.80  4895.0  373.42  4908.8  372.47
  4925.4  370.79  4946.1  368.72  4952.1  367.21  4961.2  366.91  4967.2  365.36
  5000.2  363.61  5000.7  362.81  5005.9  362.81  5006.4  363.61  5018.3  366.07
  5024.3  365.21  5083.3  373.21  5147.7  376.86  5219.9  379.71  5234.9  379.39
  5292.1  381.48  5307.1  381.02  5328.2  382.47  5343.2  382.05  5364.3  383.20
  5379.3  382.80  5400.4  384.05  5415.4  383.53  5436.5  384.86  5498.8  385.78
#Mann=6,-1,0
  4529.0    0.05       0  4805.1    0.08       0  4908.8     0.1       0
  4925.4    0.05       0  5000.2    0.04       0  5006.4    0.05       0
Bank Sta=5000.2,5006.4
Exp/Cntr=0.3,0.1

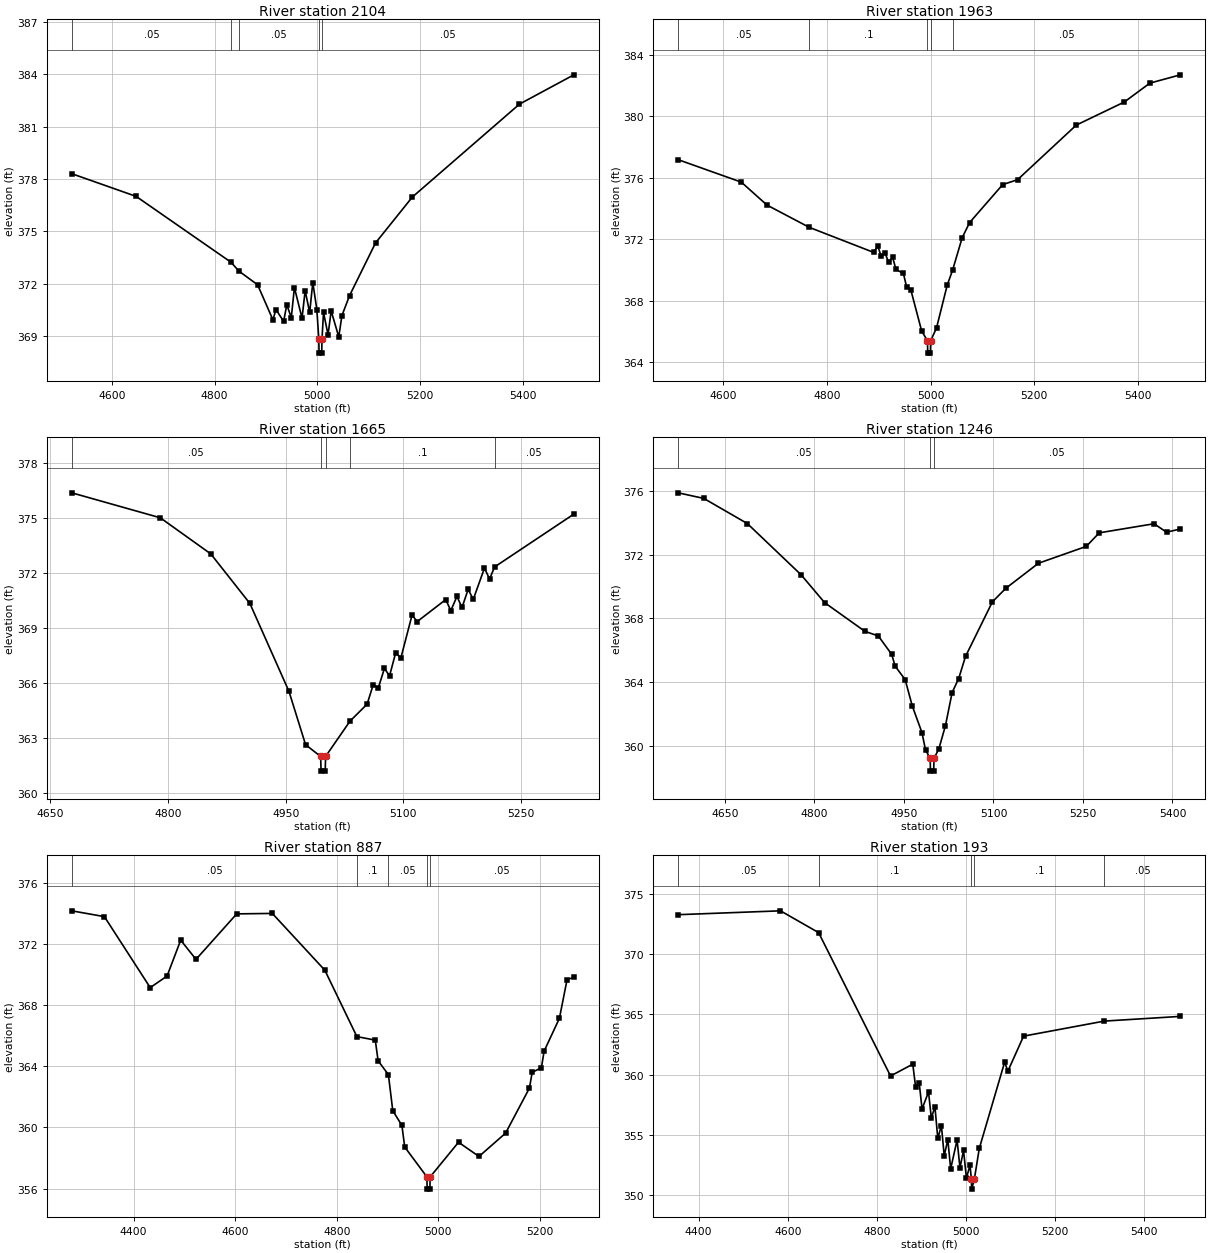
Type RM Length L Ch R = 1,2104,141,141,141
BEGIN DESCRIPTION:
Mapping XS a91bcb7d
END DESCRIPTION:
XS GIS Cut Line= 3
      2047692.06     13440426.26      2047486.30     13440579.93
      2046893.54     13440990.71
#Sta/Elev= 30
  4521.7  378.30  4647.0  377.00  4832.0  373.22  4847.4  372.71  4883.7  371.93
  4913.5  369.92  4919.5  370.51  4934.4  369.83  4940.5  370.78  4949.3  370.05
  4955.4  371.77  4970.2  370.01  4976.3  371.59  4985.1  370.34  4991.2  372.06
  4999.1  370.51  5002.9  368.81  5003.4  368.01  5008.6  368.01  5009.1  368.81
  5012.1  370.34  5020.9  369.06  5027.0  370.43  5041.8  368.94  5047.9  370.16
  5062.8  371.31  5113.4  374.33  5185.1  376.96  5393.8  382.29  5499.7  383.97
#Mann=5,-1,0
  4521.7    0.05       0  4832.0    0.08       0  4847.4    0.05       0
  5002.9    0.04       0  5009.1    0.05       0
Bank Sta=5002.9,5009.1
Exp/Cntr=0.3,0.1

Type RM Length L Ch R = 1,1963,298,298,298
BEGIN DESCRIPTION:
Mapping XS 7a8b089a
END DESCRIPTION:
XS GIS Cut Line= 2
      2047567.05     13440335.13      2046814.46     13440947.10
#Sta/Elev= 30
  4512.6  377.18  4634.5  375.72  4684.0  374.23  4765.8  372.78  4890.2  371.15
  4898.1  371.57  4904.5  370.91  4912.5  371.08  4918.9  370.52  4926.8  370.83
  4933.3  370.04  4947.6  369.78  4954.1  368.87  4962.0  368.71  4982.8  366.05
  4994.1  365.40  4994.6  364.60  4999.8  364.60  5000.3  365.40  5011.6  366.24
  5032.4  369.04  5042.6  369.99  5061.1  372.10  5075.5  373.09  5139.4  375.56
  5168.2  375.88  5281.6  379.43  5374.3  380.93  5423.8  382.16  5482.6  382.70
#Mann=5,-1,0
  4512.6    0.05       0  4765.8     0.1       0  4994.1    0.07       0
  5000.3     0.1       0  5042.6    0.05       0
Bank Sta=4994.1,5000.3
Exp/Cntr=0.3,0.1

Type RM Length L Ch R = 1,1665,419,419,419
BEGIN DESCRIPTION:
UNT 049 in RCW 4.0
END DESCRIPTION:
XS GIS Cut Line= 3
      2047301.37     13440212.77      2047025.00     13440425.00
      2046801.95     13440612.57
#Sta/Elev= 30
  4677.4  376.36  4790.2  375.00  4854.6  373.03  4904.4  370.33  4954.2  365.54
  4975.4  362.63  4994.6  361.99  4995.1  361.19  5000.4  361.19  5000.9  361.99
  5032.1  363.92  5053.8  364.84  5061.6  365.90  5068.1  365.73  5075.9  366.79
  5082.4  366.38  5090.2  367.64  5096.8  367.35  5111.1  369.70  5117.6  369.34
  5154.0  370.54  5160.5  369.94  5168.3  370.71  5174.8  370.11  5182.6  371.10
  5189.1  370.55  5203.4  372.26  5209.9  371.66  5216.3  372.32  5317.3  375.20
#Mann=5,-1,0
  4677.4    0.05       0  4994.6    0.03       0  5000.9    0.05       0
  5032.1     0.1       0  5216.3    0.05       0
Bank Sta=4994.6,5000.9
Exp/Cntr=0.3,0.1

Type RM Length L Ch R = 1,1246,359,359,359
BEGIN DESCRIPTION:
UNT 049 in RCW 3.0
END DESCRIPTION:
XS GIS Cut Line= 3
      2047177.31     13439890.68      2046578.32     13440183.67
      2046460.82     13440313.07
#Sta/Elev= 30
  4571.6  375.88  4614.4  375.53  4687.5  373.95  4777.5  370.74  4817.0  368.99
  4884.5  367.19  4907.0  366.90  4929.5  365.74  4935.1  365.01  4952.0  364.16
  4963.8  362.52  4980.1  360.84  4986.1  359.75  4993.9  359.22  4994.4  358.42
  4999.8  358.42  5000.3  359.22  5008.3  359.80  5019.5  361.27  5030.7  363.35
  5041.7  364.23  5053.2  365.62  5098.2  369.04  5120.7  369.89  5175.3  371.46
  5255.6  372.52  5277.3  373.37  5369.2  373.94  5390.1  373.41  5413.2  373.61
#Mann=3,-1,0
  4571.6    0.05       0  4993.9    0.03       0  5000.3    0.05       0
Bank Sta=4993.9,5000.3
Exp/Cntr=0.3,0.1

Type RM Length L Ch R = 1,887,694,694,694
BEGIN DESCRIPTION:
UNT 049 in RCW 2.0
END DESCRIPTION:
XS GIS Cut Line= 4
      2047359.12     13439660.23      2046918.16     13439635.92
      2046445.94     13439840.78      2046418.22     13439856.42
#Sta/Elev= 30
  4278.5  374.19  4342.7  373.81  4432.9  369.16  4466.1  369.92  4492.9  372.27
  4523.0  371.01  4603.1  373.99  4673.2  374.02  4776.6  370.30  4839.7  365.95
  4875.9  365.72  4881.4  364.37  4901.7  363.46  4910.3  361.10  4928.3  360.13
  4933.8  358.72  4977.5  356.76  4978.0  355.96  4983.4  355.96  4983.9  356.76
  5039.7  359.03  5080.0  358.10  5132.4  359.63  5179.3  362.58  5184.7  363.61
  5202.8  363.91  5208.2  365.00  5238.3  367.15  5253.4  369.69  5266.7  369.83
#Mann=5,-1,0
  4278.5    0.05       0  4839.7     0.1       0  4901.7    0.05       0
  4977.5    0.03       0  4983.9    0.05       0
Bank Sta=4977.5,4983.9
Exp/Cntr=0.3,0.1

Type RM Length L Ch R = 1,193,0,0,0
BEGIN DESCRIPTION:
UNT 049 in RCW 1.0
END DESCRIPTION:
XS GIS Cut Line= 4
      2047307.05     13439361.62      2046876.49     13439080.37
      2046456.35     13439410.23      2046419.56     13439478.96
#Sta/Elev= 30
  4354.3  373.29  4583.7  373.61  4669.2  371.80  4830.6  359.89  4880.5  360.87
  4886.9  358.96  4895.0  359.29  4901.3  357.15  4915.8  358.56  4922.1  356.40
  4930.2  357.33  4936.6  354.71  4944.7  355.77  4951.0  353.26  4959.1  354.60
  4965.5  352.18  4979.9  354.57  4986.3  352.27  4994.4  353.70  5000.8  351.41
  5008.9  352.48  5012.0  351.29  5012.5  350.49  5018.5  351.29  5029.7  353.87
  5086.6  361.04  5093.8  360.29  5129.1  363.20  5310.3  364.45  5480.7  364.84
#Mann=5,-1,0
  4354.3    0.05       0  4669.2     0.1       0  5012.0    0.07       0
  5018.5     0.1       0  5310.3    0.05       0
Bank Sta=5012,5018.5
Exp/Cntr=0.3,0.1

Chan Stop Cuts=-1