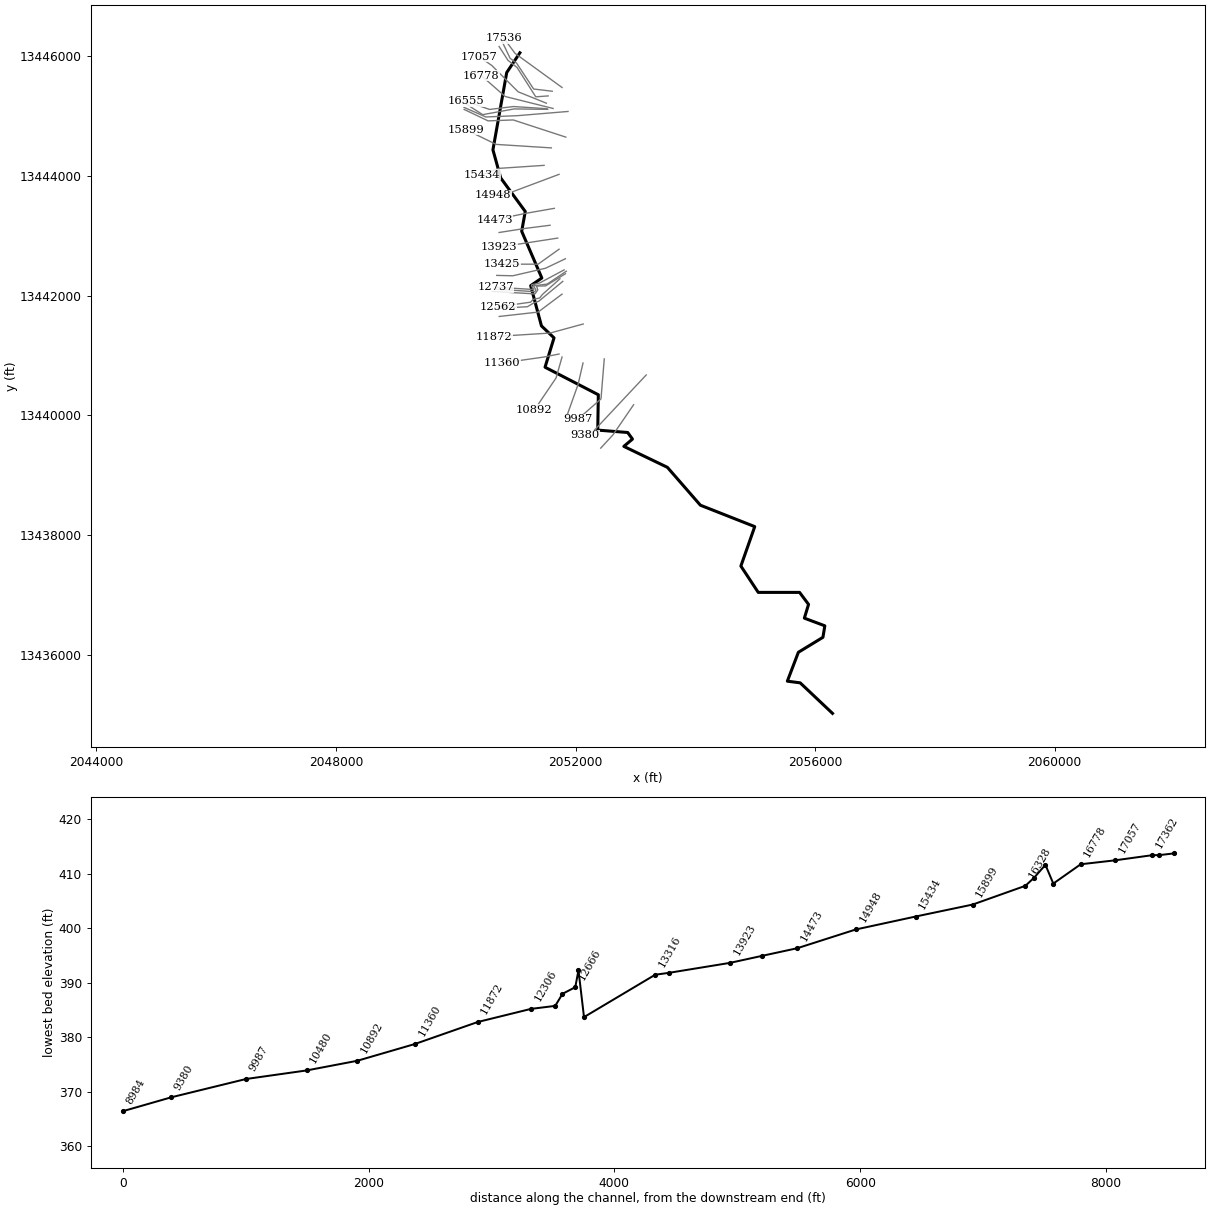
--- UNT 050 in RCW.prj (project) ---

Proj Title=UNT 050 in RCW Base Level Engineering
Current Plan=p01
Default Exp/Contr=0.3,0.1
English Units
Geom File=g01
Flow File=f01
Plan File=p01
Y Axis Title=Elevation
X Axis Title(PF)=Main Channel Distance
X Axis Title(XS)=Station
BEGIN DESCRIPTION:
UNT 050 in RCW
END DESCRIPTION:
DSS Export Rating Curves= 0
DSS Export Rating Curve Sorted= 0
DSS Export Volume Flow Curves= 0
DXF OffsetX= 0
DXF OffsetY= 0
DXF ScaleX= 1
DXF ScaleY= 10

--- UNT 050 in RCW.p01 (plan) ---

Plan Title=Multiple Run
Short Identifier=Multiple
Geom File=g01
Flow File=f01
Subcritical Flow
K Sum by GR= 0
Std Step Tol= 0.01
Critical Tol= 0.01
Num of Std Step Trials= 20
Max Error Tol= 0.3
Flow Tol Ratio= 0.001
Split Flow NTrial= 30
Split Flow Tol= 0.02
Split Flow Ratio= 0.02
Log Output Level= 0
Friction Slope Method= 1
Unsteady Friction Slope Method= 2
Unsteady Bridges Friction Slope Method= 1
Parabolic Critical Depth
Global Vel Dist=  1 , 1 , 1
Global Log Level= 0
CheckData=True
Encroach Param= -1, 0, 0, 0
BEGIN DESCRIPTION:
Multiple Run
END DESCRIPTION:

--- UNT 050 in RCW.f01 (steady flow) ---

Flow Title=Multiple
Number of Profiles=7
Profile Names=10-year,25-year,50-year,1pct_min,100-year,1pct_plu,500-year
River Rch & RM= UNT 050 in RCW,Reach-1,17536
     188     258     314     192     382     763     574
River Rch & RM= UNT 050 in RCW,Reach-1,16778
     270     377     465     286     571    1139     874
River Rch & RM= UNT 050 in RCW,Reach-1,6693
     411     585     732     457     911    1818    1433
River Rch & RM= UNT 050 in RCW,Reach-1,4598
     467     668     840     525    1048    2091    1659
River Rch & RM= UNT 050 in RCW,Reach-1,2816
     542     780     984     618    1232    2459    1964
Boundary for River Rch & Prof#=UNT 050 in RCW,Reach-1,1
Up Type=0
Dn Type=3
Dn Slope=0.005
Boundary for River Rch & Prof#=UNT 050 in RCW,Reach-1,2
Up Type=0
Dn Type=3
Dn Slope=0.005
Boundary for River Rch & Prof#=UNT 050 in RCW,Reach-1,3
Up Type=0
Dn Type=3
Dn Slope=0.005
Boundary for River Rch & Prof#=UNT 050 in RCW,Reach-1,4
Up Type=0
Dn Type=3
Dn Slope=0.005
Boundary for River Rch & Prof#=UNT 050 in RCW,Reach-1,5
Up Type=0
Dn Type=3
Dn Slope=0.005
Boundary for River Rch & Prof#=UNT 050 in RCW,Reach-1,6
Up Type=0
Dn Type=3
Dn Slope=0.005
Boundary for River Rch & Prof#=UNT 050 in RCW,Reach-1,7
Up Type=0
Dn Type=3
Dn Slope=0.005

--- UNT 050 in RCW.g01 (geometry) ---

Geom Title=Existing Conditions
Program Version=5.05

River Reach=UNT 050 in RCW  ,Reach-1
Reach XY= 30
       2051070.8     13446054.54       2050850.8     13445724.54
       2050620.8     13444434.54       2050750.8     13443964.54
       2051160.8     13443404.54       2051100.8     13443074.54
      2051437.36     13442293.99      2051251.25     13442166.21
       2051430.8     13441494.54       2051640.8     13441294.54
       2051490.8     13440804.54       2052380.8     13440344.54
       2052370.8     13439754.54       2052870.8     13439714.54
       2052950.8     13439604.54      2052806.54     13439482.58
      2053533.97     13439132.75      2054084.74     13438500.57
      2054992.38     13438142.94       2054760.8     13437484.54
       2055050.8     13437044.54       2055740.8     13437044.54
       2055890.8     13436844.54       2055820.8     13436614.54
      2056162.63     13436486.57       2056130.8     13436294.54
       2055720.8     13436044.54      2055536.77     13435562.09
       2055750.8     13435534.54       2056290.8     13435024.54

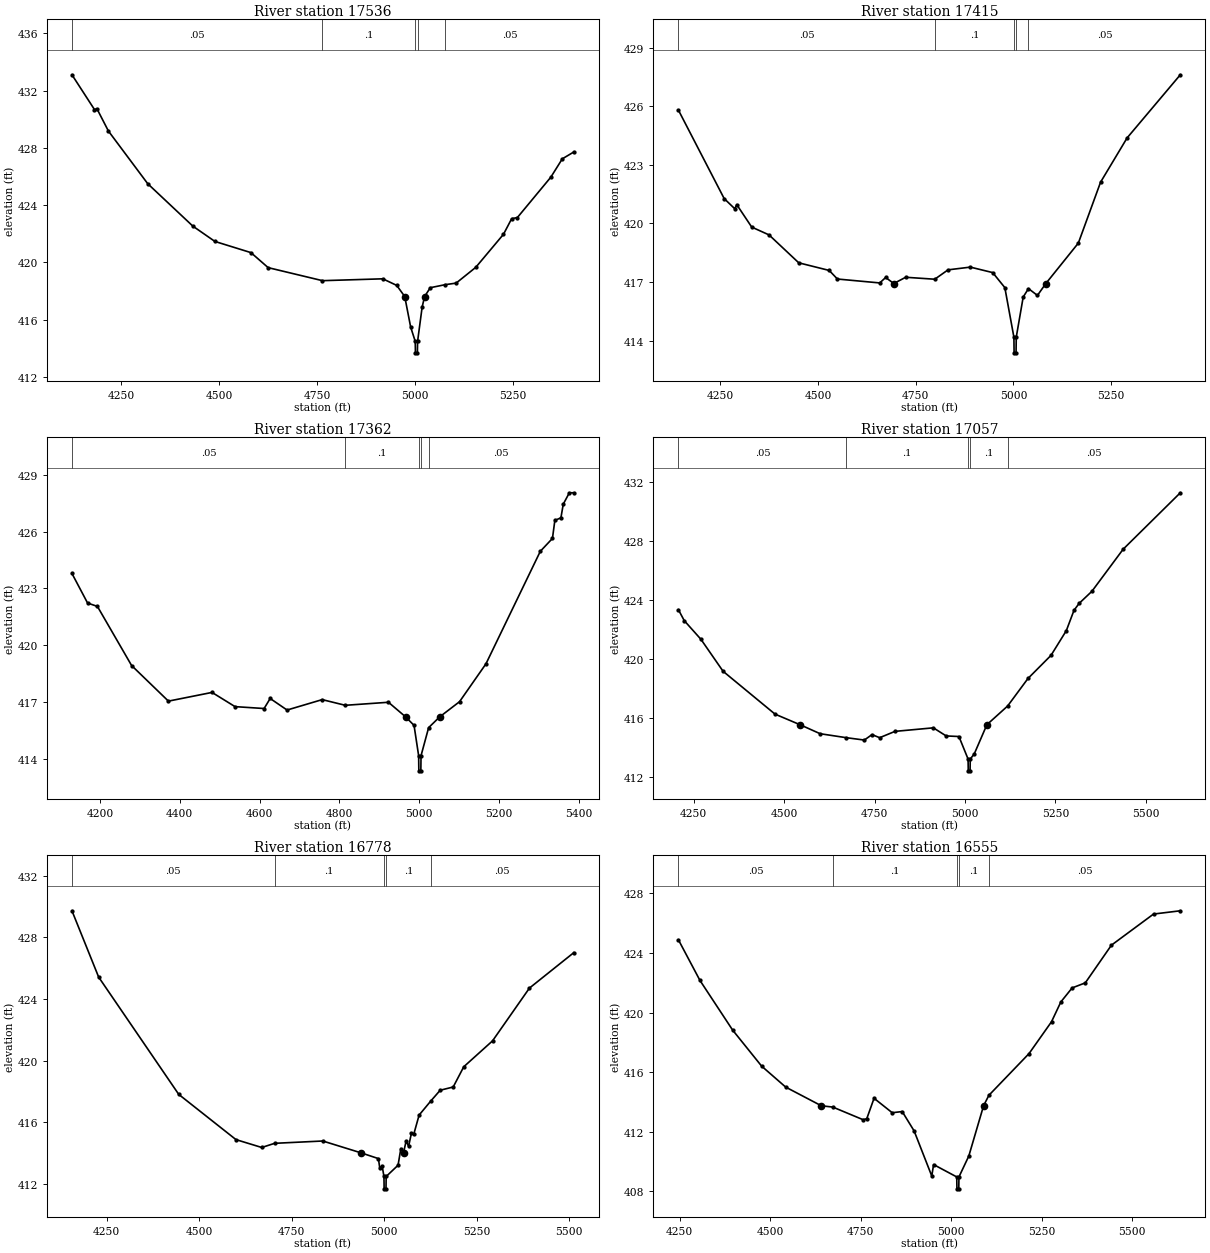
Type RM Length L Ch R = 1 ,17536   ,121,121,121
BEGIN DESCRIPTION:
UNT 050 in RCW 34.0
END DESCRIPTION:
XS GIS Cut Line= 3
      2051775.03     13445474.98      2050990.68     13446044.25
      2050804.07     13446295.96
#Sta/Elev= 30
  4123.8  433.11  4181.4  430.68  4187.6  430.74    4217  429.18  4317.5   425.5
  4432.7  422.54  4489.1  421.47  4581.1  420.69  4625.2  419.64    4764  418.73
  4918.1  418.86  4953.7   418.4 4974.15417.6237  4989.3  415.49    5001  414.49
  5001.5  413.69  5006.5  413.69    5007  414.49  5018.6  416.88  5024.9417.6238
  5039.5  418.24  5077.5  418.45  5105.5  418.56  5155.6  419.66  5226.5  421.97
  5247.4  423.06    5262  423.14  5347.5  425.96  5376.8  427.24  5406.3  427.72
#Mann= 5 ,-1 , 0
  4123.8     .05       0    4764      .1       0    5001     .07       0
    5007      .1       0  5077.5     .05       0
Bank Sta=4974.15,5024.9
XS Rating Curve= 0 ,0
Exp/Cntr=0.3,0.1

Type RM Length L Ch R = 1 ,17415   ,53,53,53
BEGIN DESCRIPTION:
Mapping XS 9cd8a9bd
END DESCRIPTION:
XS GIS Cut Line= 5
      2051611.32     13445412.74      2051301.01     13445449.63
      2051014.55     13445883.66      2050908.21     13445961.79
      2050770.29     13446250.56
#Sta/Elev= 30
  4142.7   425.8  4259.8  421.27  4286.9  420.75    4292  420.96  4330.3  419.81
  4374.6  419.41  4450.7  417.98  4528.6  417.59  4549.6  417.15    4658  416.95
  4673.1  417.23 4693.84416.9197  4724.3  417.24  4798.8  417.14  4832.7  417.62
  4889.8  417.76    4947  417.48  4978.1  416.71  5001.3  414.17  5001.8  413.37
  5006.8  413.37  5007.3  414.17  5025.1  416.23  5038.6  416.66  5061.5  416.31
 5083.05416.9199  5166.2  418.99  5223.1  422.11  5291.1  424.38  5427.2  427.61
#Mann= 5 ,-1 , 0
  4142.7     .05       0  4798.8      .1       0  5001.3     .07       0
  5007.3      .1       0  5038.6     .05       0
Bank Sta=4693.84,5083.05
XS Rating Curve= 0 ,0
Exp/Cntr=0.3,0.1

Type RM Length L Ch R = 1 ,17362   ,305,305,305
BEGIN DESCRIPTION:
Mapping XS 2cb11d40
END DESCRIPTION:
XS GIS Cut Line= 5
      2051544.03     13445334.61      2051335.73     13445319.43
      2051023.23     13445809.88      2050871.32     13445929.24
      2050723.75     13446159.28
#Sta/Elev= 30
  4130.2  423.79  4169.3  422.23    4194  422.05  4279.6  418.93  4371.8  417.05
    4481  417.51  4538.6  416.76  4611.4  416.66  4626.6  417.19  4668.9  416.58
  4756.9  417.13  4814.7  416.83  4922.8  416.99 4965.92416.2169  4986.9  415.77
  4998.4  414.17  4998.9  413.37  5003.9  413.37  5004.4  414.17  5023.4  415.65
 5051.01416.2168  5100.8  417.02    5167  419.02  5303.1  424.96  5333.5  425.64
  5339.5  426.59  5354.7  426.73  5360.6  427.45  5375.8  428.05  5387.1  428.05
#Mann= 5 ,-1 , 0
  4130.2     .05       0  4814.7      .1       0  4998.4     .07       0
  5004.4      .1       0  5023.4     .05       0
Bank Sta=4965.92,5051.01
XS Rating Curve= 0 ,0
Exp/Cntr=0.3,0.1

Type RM Length L Ch R = 1 ,17057   ,279,279,279
BEGIN DESCRIPTION:
Mapping XS 1528beb8
END DESCRIPTION:
XS GIS Cut Line= 4
      2051512.81     13445213.09      2051041.46     13445403.19
      2050601.36      13445843.3      2050390.12     13445990.13
#Sta/Elev= 30
  4207.5  423.36  4223.6  422.62  4269.8  421.35    4331  419.18  4474.7  416.27
 4543.75415.5524  4599.5  414.94    4672  414.67  4721.6  414.51  4742.8  414.88
    4764  414.67  4806.4   415.1  4912.5  415.34  4947.9  414.79  4983.2  414.75
  5008.5  413.22    5009  412.42    5014  412.42  5014.5  413.22  5025.6  413.57
 5060.48415.5522  5117.8  416.82  5174.1  418.69  5237.8  420.26  5280.2  421.94
  5301.4  423.32  5315.6  423.79  5350.9  424.61  5437.4  427.47  5595.4   431.3
#Mann= 5 ,-1 , 0
  4207.5     .05       0    4672      .1       0  5008.5     .07       0
  5014.5      .1       0  5117.8     .05       0
Bank Sta=4543.75,5060.48
XS Rating Curve= 0 ,0
Exp/Cntr=0.3,0.1

Type RM Length L Ch R = 1 ,16778   ,223,223,223
BEGIN DESCRIPTION:
UNT 050 in RCW 33.0
END DESCRIPTION:
XS GIS Cut Line= 3
      2051625.01       13445125.        2050825.       13445325.
      2050425.03     13445674.98
#Sta/Elev= 30
  4156.5  429.72  4228.7  425.42  4445.1  417.82  4599.7  414.89  4669.3  414.38
  4704.2  414.65  4834.2   414.8 4938.28414.0273  4984.5  413.66  4988.2  413.05
  4994.9  413.15  4999.5   412.5    5000   411.7    5005   411.7  5005.5   412.5
  5037.6  413.23  5045.2  414.31 5052.32414.0268  5059.4   414.8  5066.1  414.46
  5073.7   415.3  5080.3  415.26  5094.5  416.48    5126  417.39  5151.5  418.09
  5186.6   418.3  5215.1  419.61  5292.9  421.29  5392.6  424.71  5512.6  427.01
#Mann= 5 ,-1 , 0
  4156.5     .05       0  4704.2      .1       0  4999.5     .07       0
  5005.5      .1       0    5126     .05       0
Bank Sta=4938.28,5052.32
XS Rating Curve= 0 ,0
Exp/Cntr=0.3,0.1

Type RM Length L Ch R = 1 ,16555   ,64,64,64
BEGIN DESCRIPTION:
Mapping XS 193d2f3b
END DESCRIPTION:
XS GIS Cut Line= 4
      2051524.44     13445120.67       2050963.7     13445157.12
       2050564.4     13445108.51      2050165.13     13445247.39
#Sta/Elev= 30
  4246.2  424.88  4305.8  422.15    4396  418.82  4476.1   416.4  4542.7  414.99
  4641.1413.7378  4672.8  413.65  4756.7   412.8  4766.7  412.87  4786.8  414.24
    4837  413.27  4864.6  413.35  4897.5  412.05  4946.3  409.02  4951.3  409.79
  5015.3  408.96  5015.8  408.16  5020.9  408.16  5021.4  408.96  5048.6  410.36
 5089.43413.7378  5104.1  414.44    5215  417.24  5277.2  419.38    5303  420.71
  5334.1  421.65  5370.5  421.99  5442.7  424.52  5559.1  426.61  5633.1  426.83
#Mann= 5 ,-1 , 0
  4246.2     .05       0  4672.8      .1       0  5015.3     .07       0
  5021.4      .1       0  5104.1     .05       0
Bank Sta=4641.1,5089.43
XS Rating Curve= 0 ,0
Exp/Cntr=0.3,0.1

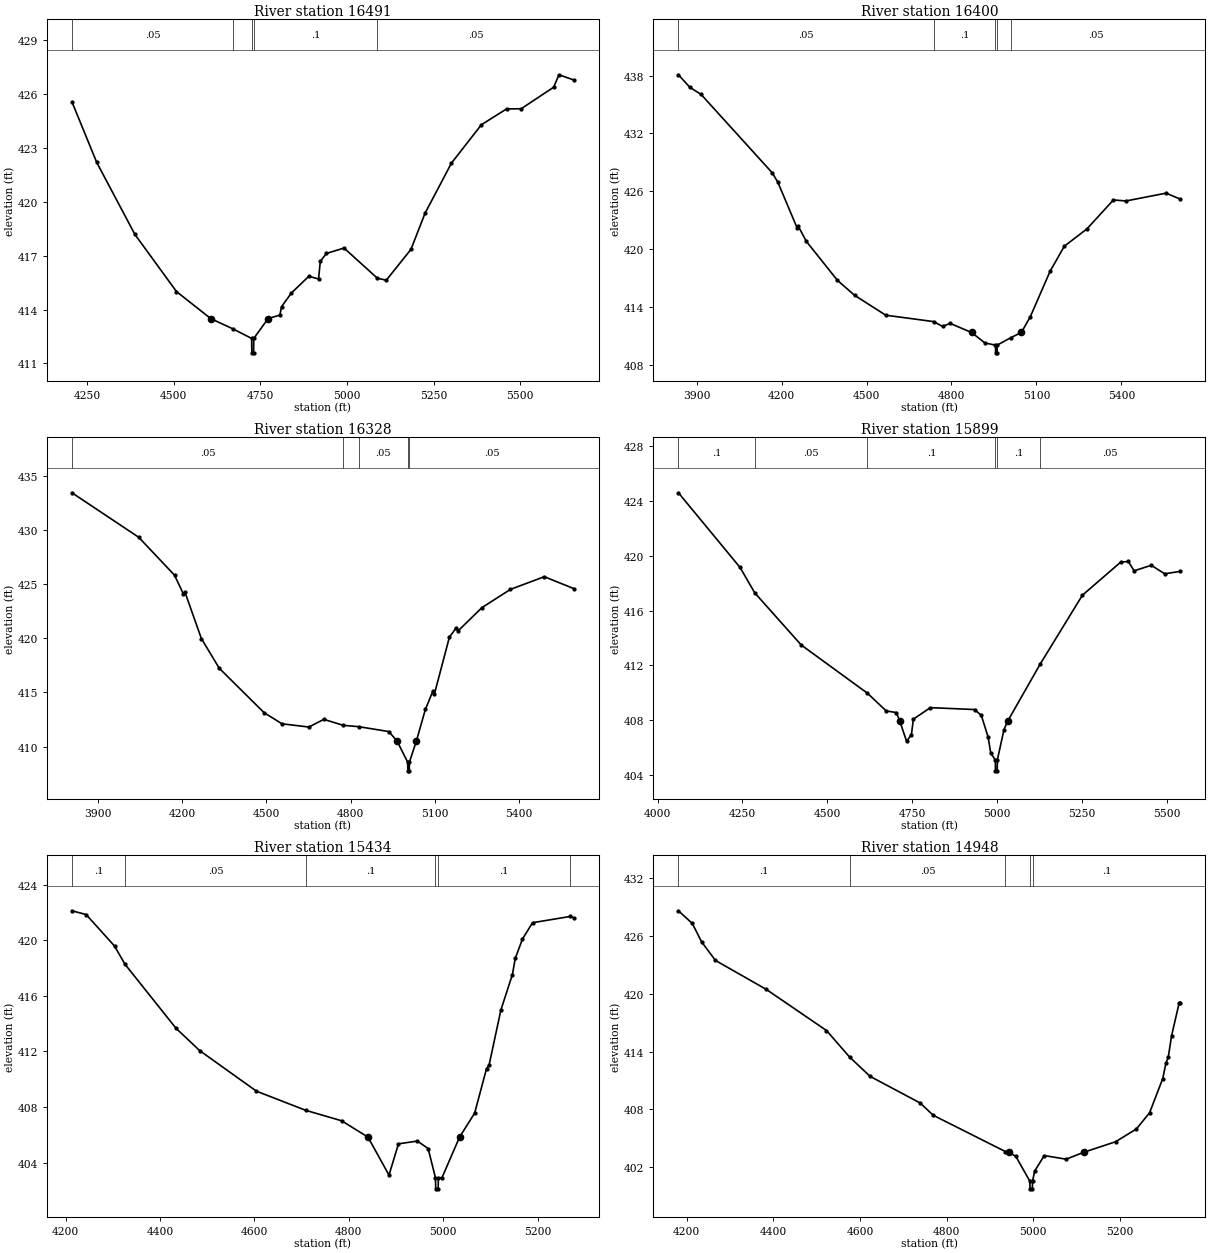
Type RM Length L Ch R = 1 ,16491   ,91,91,91
BEGIN DESCRIPTION:
Mapping XS d3f772af
END DESCRIPTION:
XS GIS Cut Line= 4
      2051536.58     13445110.25      2050974.12     13445117.19
      2050449.81     13445021.71      2050152.96     13445212.66
#Sta/Elev= 30
  4206.4  425.55    4278  422.18    4388  418.18    4508     415    4607 413.494
  4671.4  412.92    4725  412.39  4725.5  411.59  4730.6  411.59  4731.1  412.39
 4772.39 413.494  4806.3  413.69  4811.4  414.16  4839.2  414.91    4890  415.85
    4918   415.7  4923.1  416.68  4940.8  417.12  4991.6  417.42  5087.8  415.74
  5113.6  415.63  5184.8  417.35  5225.4  419.36  5301.7  422.15    5388  424.28
  5460.6  425.16  5502.9  425.17  5596.6  426.37  5611.8  427.06  5654.8  426.77
#Mann= 5 ,-1 , 0
  4206.4     .05       0  4671.4      .1       0    4725     .07       0
  4731.1      .1       0  5087.8     .05       0
Bank Sta=4607,4772.39
XS Rating Curve= 0 ,0
Exp/Cntr=0.3,0.1

Type RM Length L Ch R = 1 ,16400   ,72,72,72
BEGIN DESCRIPTION:
UNT 050 in RCW 32.0
END DESCRIPTION:
XS GIS Cut Line= 4
      2051874.96       13445075.      2051031.91     13445004.76
       2050502.4     13444983.05      2050138.92     13445143.16
#Sta/Elev= 30
  3835.3  438.08  3875.4  436.79  3915.5  436.04  4166.4  427.93  4186.5  426.95
  4254.2  422.24  4259.3  422.36  4286.8  420.83  4397.2  416.77  4457.4  415.23
  4567.8  413.16  4736.5   412.5  4768.3     412  4795.3  412.31 4870.79411.3702
  4918.4  410.28  4955.4  410.06  4955.9  409.26    4961  409.26  4961.5  410.06
  5010.1  410.84 5046.96411.3701  5078.5  413.01  5148.6  417.73  5198.6  420.31
  5278.7  422.11  5372.1  425.11    5416     425  5558.1  425.81  5608.4  425.19
#Mann= 5 ,-1 , 0
  3835.3     .05       0  4736.5      .1       0  4955.4     .07       0
  4961.5      .1       0  5010.1     .05       0
Bank Sta=4870.79,5046.96
XS Rating Curve= 0 ,0
Exp/Cntr=0.3,0.1

Type RM Length L Ch R = 1 ,16328   ,429,429,429
BEGIN DESCRIPTION:
Mapping XS 209a5750
END DESCRIPTION:
XS GIS Cut Line= 4
      2051837.01     13444646.69       2050960.3     13444933.14
      2050539.29     13444917.95      2050140.01     13445108.91
#Sta/Elev= 30
    3808  433.46  4045.4  429.35    4173  425.84  4204.8   424.1  4210.1  424.28
  4268.6  419.98  4332.4  417.23  4491.7  413.13  4555.5   412.1  4651.1   411.8
  4704.3  412.51  4773.2  411.96  4829.7  411.83  4935.8  411.38 4965.35410.4911
  5002.8  408.55  5003.3  407.75  5008.4  407.75  5008.9  408.55  5033.6 410.491
  5065.8  413.43  5092.8  415.14  5097.8  414.84  5151.3  420.11  5176.3  420.99
  5181.8  420.68    5267  422.84  5368.7  424.53  5488.9   425.7  5594.2   424.6
#Mann= 5 ,-1 , 0
    3808     .05       0  4773.2      .1       0  4829.7     .05       0
  5002.8     .03       0  5008.9     .05       0
Bank Sta=4965.35,5033.6
XS Rating Curve= 0 ,0
Exp/Cntr=0.3,0.1

Type RM Length L Ch R = 1 ,15899   ,465,465,465
BEGIN DESCRIPTION:
UNT 050 in RCW 31.0
END DESCRIPTION:
XS GIS Cut Line= 3
      2051596.16     13444466.56        2050675.       13444525.
      2050174.69     13444768.22
#Sta/Elev= 30
  4061.2  424.59  4242.7  419.15  4286.2  417.29  4423.1  413.49  4618.4  409.97
  4673.6  408.68  4703.6  408.56 4713.99407.9191  4733.7  406.46    4748  406.96
  4753.7  408.08  4803.8  408.92  4934.1  408.78  4954.1  408.35  4974.2  406.75
  4981.7  405.61  4995.2  405.11  4995.7  404.31  5000.8  404.31  5001.3  405.11
  5020.8  407.32 5031.31407.9189  5127.1  412.08  5251.9  417.12  5364.7  419.53
  5387.3  419.58  5404.3   418.9  5454.9   419.3  5494.5  418.68  5540.5  418.86
#Mann= 6 ,-1 , 0
  4061.2      .1       0  4286.2     .05       0  4618.4      .1       0
  4995.2     .07       0  5001.3      .1       0  5127.1     .05       0
Bank Sta=4713.99,5031.31
XS Rating Curve= 0 ,0
Exp/Cntr=0.3,0.1

Type RM Length L Ch R = 1 ,15434   ,486,486,486
BEGIN DESCRIPTION:
UNT 050 in RCW 30.0
END DESCRIPTION:
XS GIS Cut Line= 3
      2051474.95       13444175.        2050725.       13444125.
      2050432.93     13444017.33
#Sta/Elev= 30
  4213.6  422.13  4243.6  421.86  4303.8  419.59  4325.9  418.28    4434  413.67
  4484.2  412.06  4604.4  409.14  4708.9  407.76  4784.8  407.01 4840.48405.8354
    4885   403.1  4905.1  405.35  4945.2  405.55  4967.9  405.01  4983.4  402.91
  4983.9  402.11  4989.1  402.11  4989.6  402.91  4997.2  402.91 5034.46405.8354
  5066.4  407.56  5091.6  410.77  5096.9  411.01    5122  414.99  5146.4  417.54
  5152.4   418.7  5167.7   420.1    5189  421.27  5268.5  421.72  5276.5  421.63
#Mann= 6 ,-1 , 0
  4213.6      .1       0  4325.9     .05       0  4708.9      .1       0
  4983.4     .07       0  4989.6      .1       0  5268.5     .05       0
Bank Sta=4840.48,5034.46
XS Rating Curve= 0 ,0
Exp/Cntr=0.3,0.1

Type RM Length L Ch R = 1 ,14948   ,475,475,475
BEGIN DESCRIPTION:
UNT 050 in RCW 29.0
END DESCRIPTION:
XS GIS Cut Line= 3
      2051725.01       13444025.        2050925.       13443725.
      2050624.95     13443674.99
#Sta/Elev= 30
  4180.8  428.63  4212.9  427.31  4234.2  425.41  4266.3  423.47  4383.7  420.46
  4522.6  416.19  4575.8  413.44  4623.1  411.43  4738.8  408.66  4769.1  407.38
  4935.8  403.61 4943.54403.5497  4959.6  403.12    4992  400.54  4992.5  399.74
  4997.8  399.74  4998.3  400.54  5003.2  401.59  5025.4   403.2  5075.8  402.82
 5117.11403.5498  5189.8  404.63    5238  405.96  5268.4  407.64  5298.8  411.19
  5306.4  412.84  5311.5   413.4  5319.1  415.61  5336.8  419.08  5339.4  419.08
#Mann= 5 ,-1 , 0
  4180.8      .1       0  4575.8     .05       0  4935.8      .1       0
    4992     .07       0  4998.3      .1       0
Bank Sta=4943.54,5117.11
XS Rating Curve= 0 ,0
Exp/Cntr=0.3,0.1

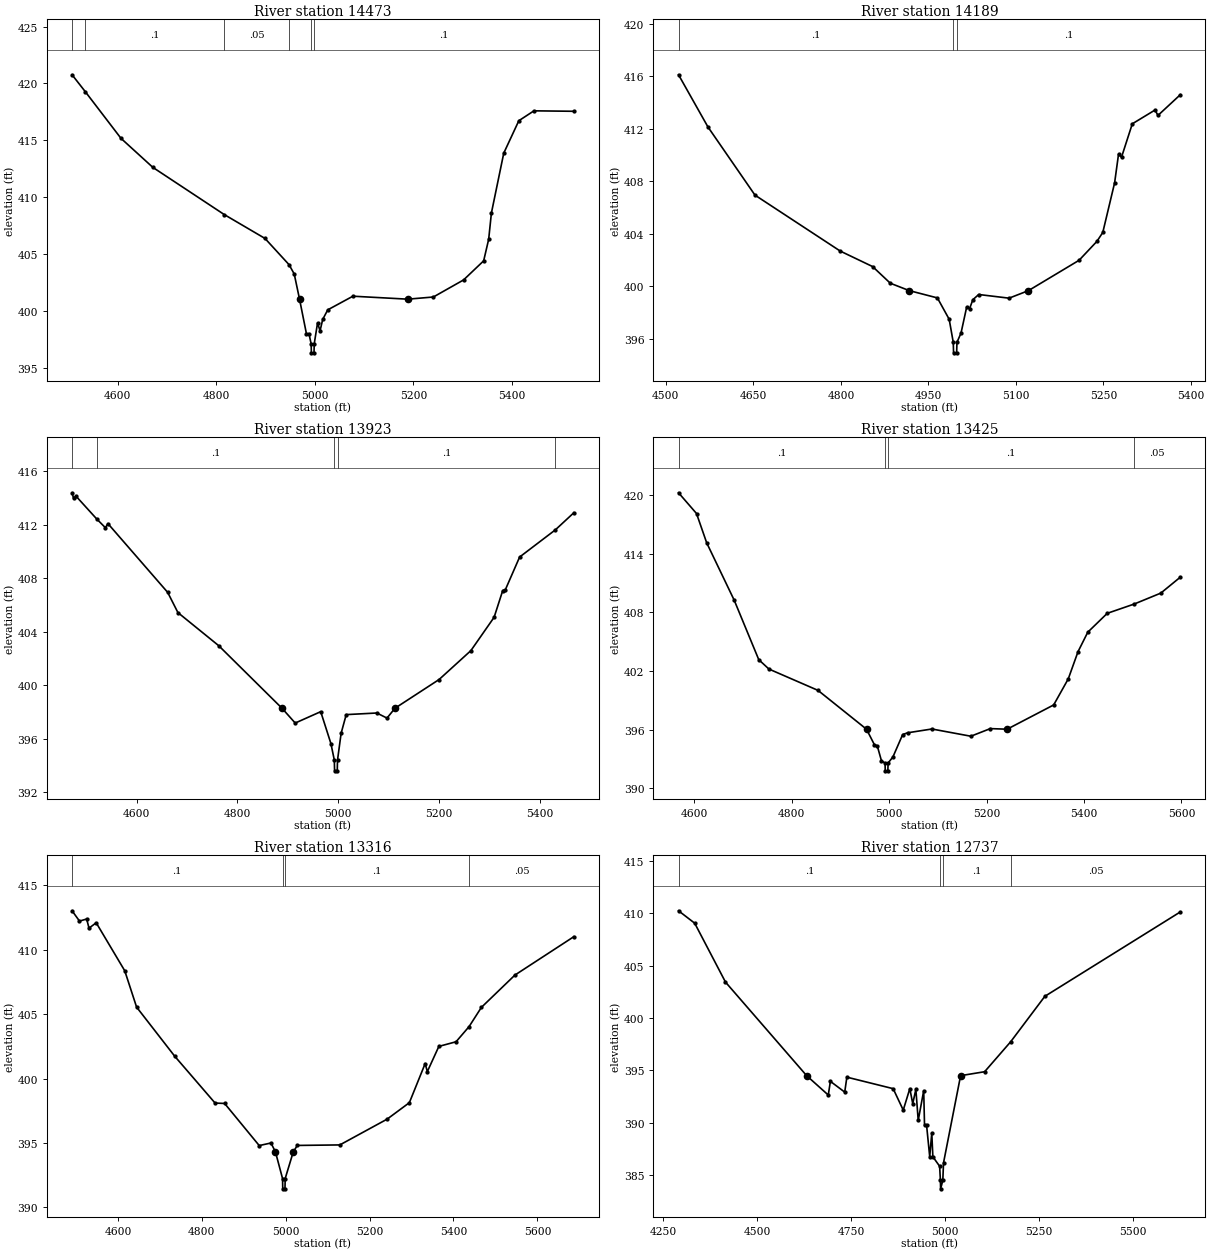
Type RM Length L Ch R = 1 ,14473   ,284,284,284
BEGIN DESCRIPTION:
UNT 050 in RCW 28.0
END DESCRIPTION:
XS GIS Cut Line= 3
      2051646.04     13443457.44        2051175.       13443375.
      2050645.61     13443266.47
#Sta/Elev= 30
  4507.3  420.76  4534.4  419.26  4606.6  415.17  4671.2  412.62  4816.2  408.47
  4898.9  406.37  4947.8  404.06  4958.3  403.24 4969.04401.0291    4983     398
  4988.1     398  4992.6  397.11  4993.1  396.31  4998.4  396.31  4998.9  397.11
  5005.6  398.94  5010.7  398.25  5016.1  399.25  5026.3  400.09  5077.4  401.29
 5188.82401.0288  5240.7  401.22    5302  402.72  5342.8   404.4    5353   406.3
  5358.5   408.6  5383.6  413.87  5414.2  416.72  5444.9  417.59  5525.9  417.55
#Mann= 6 ,-1 , 0
  4507.3     .05       0  4534.4      .1       0  4816.2     .05       0
  4947.8      .1       0  4992.6     .07       0  4998.9      .1       0
Bank Sta=4969.04,5188.82
XS Rating Curve= 0 ,0
Exp/Cntr=0.3,0.1

Type RM Length L Ch R = 1 ,14189   ,266,266,266
BEGIN DESCRIPTION:
UNT 050 in RCW 27.0
END DESCRIPTION:
XS GIS Cut Line= 3
      2051574.96     13443174.99      2051151.27     13443121.08
      2050723.74      13443053.8
#Sta/Elev= 30
  4521.8  416.13  4572.2  412.15  4652.8  406.95    4799  402.68  4854.4   401.5
  4884.7  400.23 4917.19399.6658  4965.4  399.11  4985.6  397.48  4992.6  395.72
  4993.1  394.92  4998.4  394.92  4998.9  395.72  5005.9  396.43  5015.5   398.4
  5020.6  398.29  5026.1  398.97  5036.2  399.37  5088.2  399.09 5121.45399.6657
  5208.2  401.98  5238.7  403.42  5248.8   404.1  5269.1  407.89  5275.8  410.07
  5280.9  409.84  5299.4  412.39  5338.3  413.44  5343.4  413.03  5381.7  414.61
#Mann= 3 ,-1 , 0
  4521.8      .1       0  4992.6     .07       0  4998.9      .1       0
Bank Sta=4917.19,5121.45
XS Rating Curve= 0 ,0
Exp/Cntr=0.3,0.1

Type RM Length L Ch R = 1 ,13923   ,498,498,498
BEGIN DESCRIPTION:
Mapping XS 5971a0aa
END DESCRIPTION:
XS GIS Cut Line= 2
      2051702.53     13442960.49      2050718.66     13442808.79
#Sta/Elev= 30
  4472.1  414.38    4475  413.97  4480.1  414.12  4520.6  412.44  4538.2  411.77
  4543.2  412.08  4661.8  406.94  4682.1  405.43    4763  402.96 4888.62398.2841
  4914.8  397.18  4965.4  398.03  4985.6  395.65  4992.4  394.41  4992.9  393.61
  4998.2  393.61  4998.7  394.41  5005.9  396.42    5016  397.81  5076.7  397.93
  5096.9  397.55 5112.66398.2842  5200.2  400.43  5263.3  402.59  5309.4  405.08
  5326.5  407.08  5331.6  407.13    5360  409.58  5430.9  411.61  5467.6  412.89
#Mann= 5 ,-1 , 0
  4472.1     .05       0  4520.6      .1       0  4992.4     .07       0
  4998.7      .1       0  5430.9     .05       0
Bank Sta=4888.62,5112.66
XS Rating Curve= 0 ,0
Exp/Cntr=0.3,0.1

Type RM Length L Ch R = 1 ,13425   ,109,109,109
BEGIN DESCRIPTION:
UNT 050 in RCW 26.0
END DESCRIPTION:
XS GIS Cut Line= 3
      2051725.01     13442775.01        2051375.       13442525.
      2050775.03       13442525.
#Sta/Elev= 30
  4567.5  420.22  4604.4   418.1  4625.3   415.1  4681.8  409.23  4732.2  403.15
  4753.1  402.19  4853.8  400.01 4953.38396.0377  4969.4  394.47  4975.5  394.33
  4984.1   392.8  4991.4  392.58  4991.9  391.78  4997.2  391.78  4997.7  392.58
  5007.6   393.2  5027.6  395.49  5037.6  395.67  5087.6  396.06  5167.6  395.32
  5207.6   396.1 5242.04396.0376  5337.6  398.52  5367.6  401.19  5387.6  403.97
  5407.6  405.96  5447.6  407.89  5502.9  408.84  5557.6  409.96  5597.6  411.59
#Mann= 4 ,-1 , 0
  4567.5      .1       0  4991.4     .07       0  4997.7      .1       0
  5502.9     .05       0
Bank Sta=4953.38,5242.04
XS Rating Curve= 0 ,0
Exp/Cntr=0.3,0.1

Type RM Length L Ch R = 1 ,13316   ,579,579,579
BEGIN DESCRIPTION:
Mapping XS 8a33dd45
END DESCRIPTION:
XS GIS Cut Line= 4
      2051830.54     13442615.44      2051498.49     13442457.01
      2050951.62     13442331.14      2050684.68     13442337.66
#Sta/Elev= 30
  4490.8  413.03  4508.5  412.23  4525.6  412.39  4531.2  411.68  4548.3   412.1
  4616.4  408.37  4644.6  405.55  4735.4  401.74  4831.7   398.1  4854.4  398.07
  4936.9   394.8  4964.9     395  4975.6394.3094  4992.5  392.24    4993  391.44
  4998.3  391.44  4998.8  392.24 5018.06394.3099  5027.7  394.81  5129.1  394.85
  5241.7  396.85  5294.8  398.13  5332.5  401.17  5337.6  400.54  5365.1   402.5
  5406.1  402.86  5437.2  404.04  5466.5  405.53  5546.5  408.04  5686.9  411.02
#Mann= 4 ,-1 , 0
  4490.8      .1       0  4992.5     .07       0  4998.8      .1       0
  5437.2     .05       0
Bank Sta=4975.6,5018.06
XS Rating Curve= 0 ,0
Exp/Cntr=0.3,0.1

Type RM Length L Ch R = 1 ,12737   ,45,45,45
BEGIN DESCRIPTION:
Mapping XS 3290ebf4
END DESCRIPTION:
XS GIS Cut Line= 6
      2051809.22     13442429.71       2051401.2     13442210.94
      2051267.52     13442181.43      2051265.79     13442160.59
      2051303.98     13442101.57      2050665.08      13442141.5
#Sta/Elev= 30
  4290.1  410.26  4333.2  409.07  4415.2  403.44 4631.36394.4928    4689  392.64
  4694.6  393.95  4732.8  392.92  4738.5  394.35  4861.8  393.25  4888.7   391.2
  4906.2  393.25    4914  391.82  4922.3  393.18  4928.6  390.21  4943.2  393.06
  4945.4  389.74  4950.9  389.74  4959.2  386.75  4964.7     389  4967.6  386.74
  4985.6  385.83  4987.7  384.47  4988.2  383.67  4994.1  384.47    4996  386.16
 5041.48394.4929  5105.5  394.87    5175  397.74  5265.9  402.08  5626.8  410.15
#Mann= 4 ,-1 , 0
  4290.1      .1       0  4987.7     .07       0  4994.1      .1       0
    5175     .05       0
Bank Sta=4631.36,5041.48
XS Rating Curve= 0 ,0
Exp/Cntr=0.3,0.1

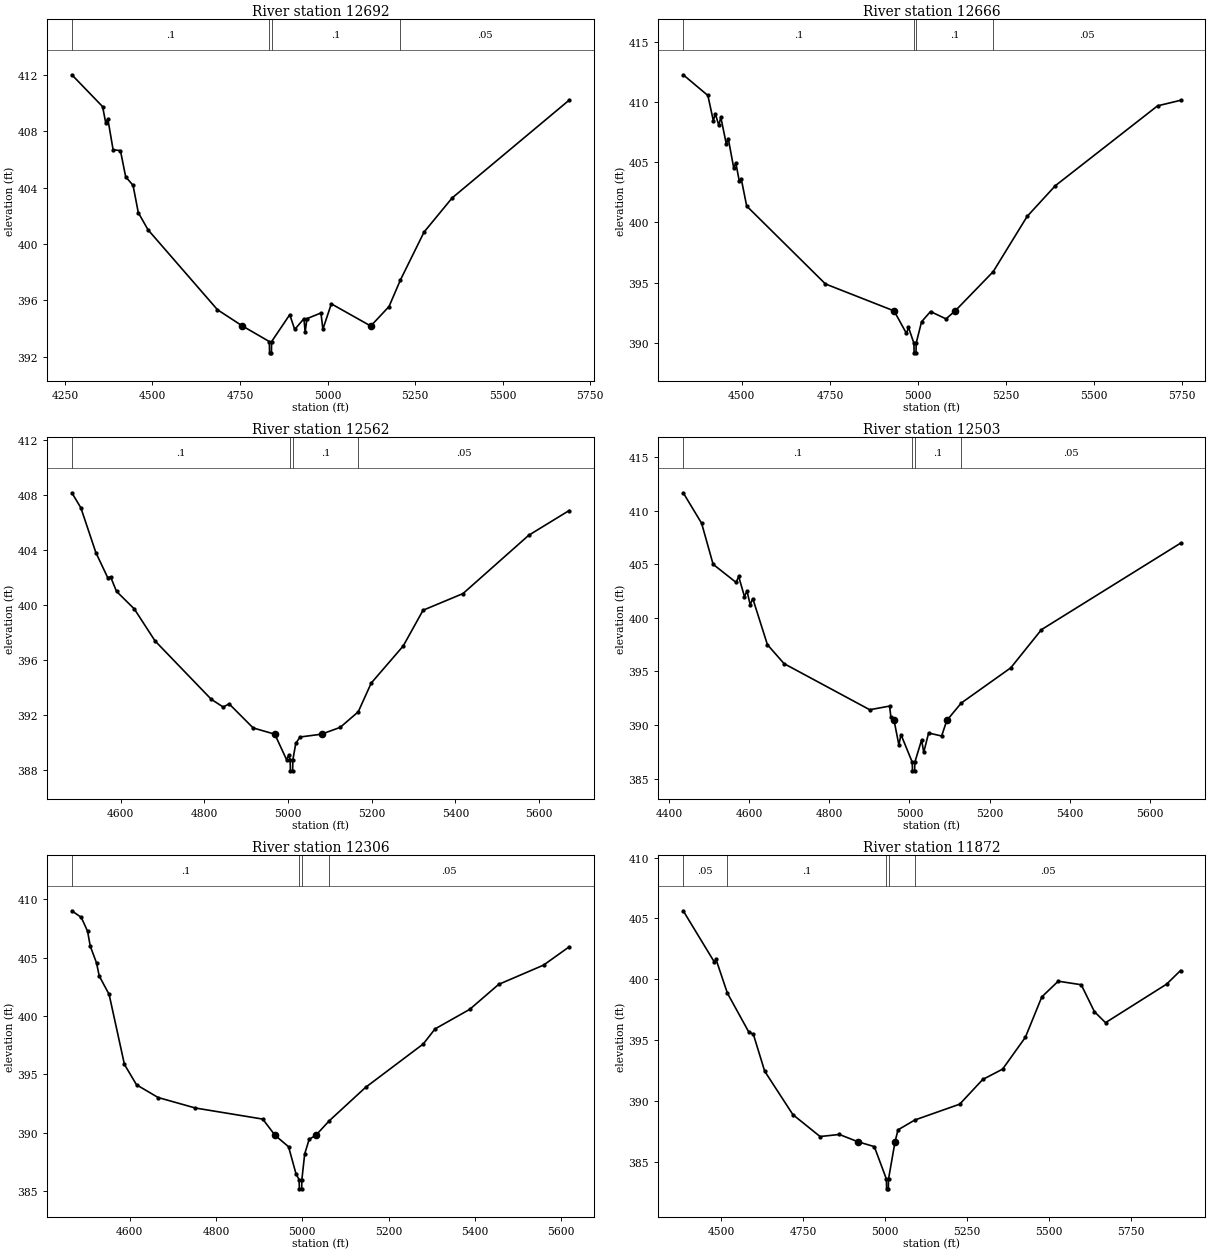
Type RM Length L Ch R = 1 ,12692   ,26,26,26
BEGIN DESCRIPTION:
Mapping XS 7183c964
END DESCRIPTION:
XS GIS Cut Line= 6
      2051845.63     13442407.11      2051527.94     13442193.58
       2051295.3     13442162.33       2051338.7     13442098.09
      2051321.34     13442065.11      2050640.81     13442110.25
#Sta/Elev= 30
  4269.7  412.02  4357.5  409.76  4366.5   408.6  4372.5  408.89  4387.5   406.7
  4408.5  406.63  4423.5  404.77  4444.5  404.17  4459.5  402.23  4487.3  401.01
  4685.7  395.33 4757.06394.1751  4833.9  393.07  4834.4  392.27  4839.8  392.27
  4840.3  393.07  4892.1  394.98  4906.3  393.93  4932.7   394.7  4936.1  393.74
  4941.3   394.7  4981.2   395.1  4986.8  393.95  5010.9  395.75 5123.52 394.175
  5175.7  395.56  5208.3  397.45  5275.8  400.85  5355.9  403.27  5690.3  410.22
#Mann= 4 ,-1 , 0
  4269.7      .1       0  4833.9     .07       0  4840.3      .1       0
  5208.3     .05       0
Bank Sta=4757.06,5123.52
XS Rating Curve= 0 ,0
Exp/Cntr=0.3,0.1

Type RM Length L Ch R = 1 ,12666   ,104,104,104
BEGIN DESCRIPTION:
Mapping XS 491dbd10
END DESCRIPTION:
XS GIS Cut Line= 6
      2051831.72     13442365.43      2051500.16     13442162.33
      2051349.12     13442158.86      2051369.95     13442096.36
      2051323.08     13442028.65      2050609.76     13442070.31
#Sta/Elev= 30
  4333.4  412.25  4403.5  410.53  4418.9  408.44  4424.8  409.01  4434.4  408.05
  4440.2  408.72  4455.7  406.52  4461.5  406.93    4477   404.5  4482.8  404.94
  4492.4  403.46  4498.3   403.6  4513.7  401.35  4737.4  394.88 4932.37392.6415
  4967.5  390.77  4973.3  391.27  4988.7  389.96  4989.2  389.16  4994.6  389.16
  4995.1  389.96  5010.4  391.74  5035.8  392.59  5079.8  391.98 5105.82392.6416
  5213.8   395.9  5310.3  400.49  5390.4  403.04  5680.7  409.67    5746  410.13
#Mann= 4 ,-1 , 0
  4333.4      .1       0  4988.7     .07       0  4995.1      .1       0
  5213.8     .05       0
Bank Sta=4932.37,5105.82
XS Rating Curve= 0 ,0
Exp/Cntr=0.3,0.1

Type RM Length L Ch R = 1 ,12562   ,59,59,59
BEGIN DESCRIPTION:
UNT 050 in RCW 25.0
END DESCRIPTION:
XS GIS Cut Line= 6
      2051739.41     13442281.26      2051446.41     13442018.64
      2051400.83     13441960.05      2051291.24     13441937.03
       2051251.1     13441890.61      2050709.24     13441814.75
#Sta/Elev= 30
  4483.7  408.16  4505.2  407.07  4541.1  403.81  4569.5  401.98  4576.2  402.05
  4590.4  400.99    4633  399.71  4682.4  397.39  4816.9  393.14  4845.3  392.58
  4859.5  392.81  4916.8  391.06 4968.54390.6057  4996.7  388.75  5001.8  389.08
  5005.3  388.74  5005.8  387.94  5011.2  387.94  5011.7  388.74  5018.7  389.94
  5028.9   390.4 5080.16390.6058  5124.8   391.1  5167.9  392.23  5198.9  394.32
  5275.4  397.02  5322.8  399.62  5418.2  400.83  5575.2  405.07  5671.9  406.87
#Mann= 4 ,-1 , 0
  4483.7      .1       0  5005.3     .07       0  5011.7      .1       0
  5167.9     .05       0
Bank Sta=4968.54,5080.16
XS Rating Curve= 0 ,0
Exp/Cntr=0.3,0.1

Type RM Length L Ch R = 1 ,12503   ,197,197,197
BEGIN DESCRIPTION:
Mapping XS 9724b7af
END DESCRIPTION:
XS GIS Cut Line= 5
      2051787.13     13442237.83      2051385.64      13441905.8
      2051298.84     13441875.42      2051196.84     13441814.65
      2050688.41     13441786.53
#Sta/Elev= 30
  4435.6  411.67  4481.5  408.83  4510.2     405  4567.5  403.31    4574  403.86
  4588.4  401.99  4594.8   402.5  4602.7  401.23  4609.2   401.8  4645.7   397.5
  4687.3  395.73    4901  391.43  4950.5  391.77  4953.8  390.74 4961.69390.4328
  4973.7  388.15    4979  389.11  5007.1  386.53  5007.6  385.73    5013  385.73
  5013.5  386.53  5030.4  388.61  5035.7  387.46  5047.9  389.26  5080.4  388.98
 5093.32390.4326  5129.5  392.06  5252.9  395.34  5329.4   398.9  5676.5  406.97
#Mann= 4 ,-1 , 0
  4435.6      .1       0  5007.1     .07       0  5013.5      .1       0
  5129.5     .05       0
Bank Sta=4961.69,5093.32
XS Rating Curve= 0 ,0
Exp/Cntr=0.3,0.1

Type RM Length L Ch R = 1 ,12306   ,434,434,434
BEGIN DESCRIPTION:
UNT 050 in RCW 24.0
END DESCRIPTION:
XS GIS Cut Line= 3
      2051774.99     13442024.99        2051375.       13441725.
      2050725.89     13441651.89
#Sta/Elev= 30
  4465.6  409.02  4487.5  408.45    4502  407.27  4508.3  405.99  4522.9  404.54
  4529.1  403.43    4552  401.85  4587.5  395.85  4615.6   394.1  4665.6  393.01
    4752  392.11  4908.3  391.16 4936.65389.7745  4968.1  388.79  4985.7  386.42
  4992.6  385.98  4993.1  385.18  4998.5  385.18    4999  385.98  5005.5  388.17
  5015.9  389.43 5031.54389.7747  5062.3  391.01  5146.7  393.88  5280.4   397.6
  5307.7  398.89  5388.2  400.57  5455.3  402.71  5559.3  404.36  5618.8  405.93
#Mann= 4 ,-1 , 0
  4465.6      .1       0  4992.6     .07       0    4999      .1       0
  5062.3     .05       0
Bank Sta=4936.65,5031.54
XS Rating Curve= 0 ,0
Exp/Cntr=0.3,0.1

Type RM Length L Ch R = 1 ,11872   ,512,512,512
BEGIN DESCRIPTION:
UNT 050 in RCW 23.0
END DESCRIPTION:
XS GIS Cut Line= 3
      2052127.85     13441526.03        2051575.       13441375.
      2050632.58     13441315.52
#Sta/Elev= 30
  4384.8  405.63  4479.7  401.42  4484.9  401.64  4519.6  398.86  4584.7  395.67
  4598.8  395.48  4633.4  392.44  4719.5  388.87  4802.4  387.07  4861.2  387.24
 4917.42386.6461  4967.9  386.24  5004.8  383.57  5005.3  382.77  5010.7  382.77
  5011.2  383.57 5031.15386.6469  5040.2  387.62  5091.5  388.43  5228.4  389.73
  5298.6  391.76  5359.2  392.61  5428.8  395.23  5478.9  398.55    5529  399.84
  5599.2  399.55  5639.3  397.34  5673.3  396.43  5859.7   399.6  5902.2  400.72
#Mann= 5 ,-1 , 0
  4384.8     .05       0  4519.6      .1       0  5004.8     .07       0
  5011.2      .1       0  5091.5     .05       0
Bank Sta=4917.42,5031.15
XS Rating Curve= 0 ,0
Exp/Cntr=0.3,0.1

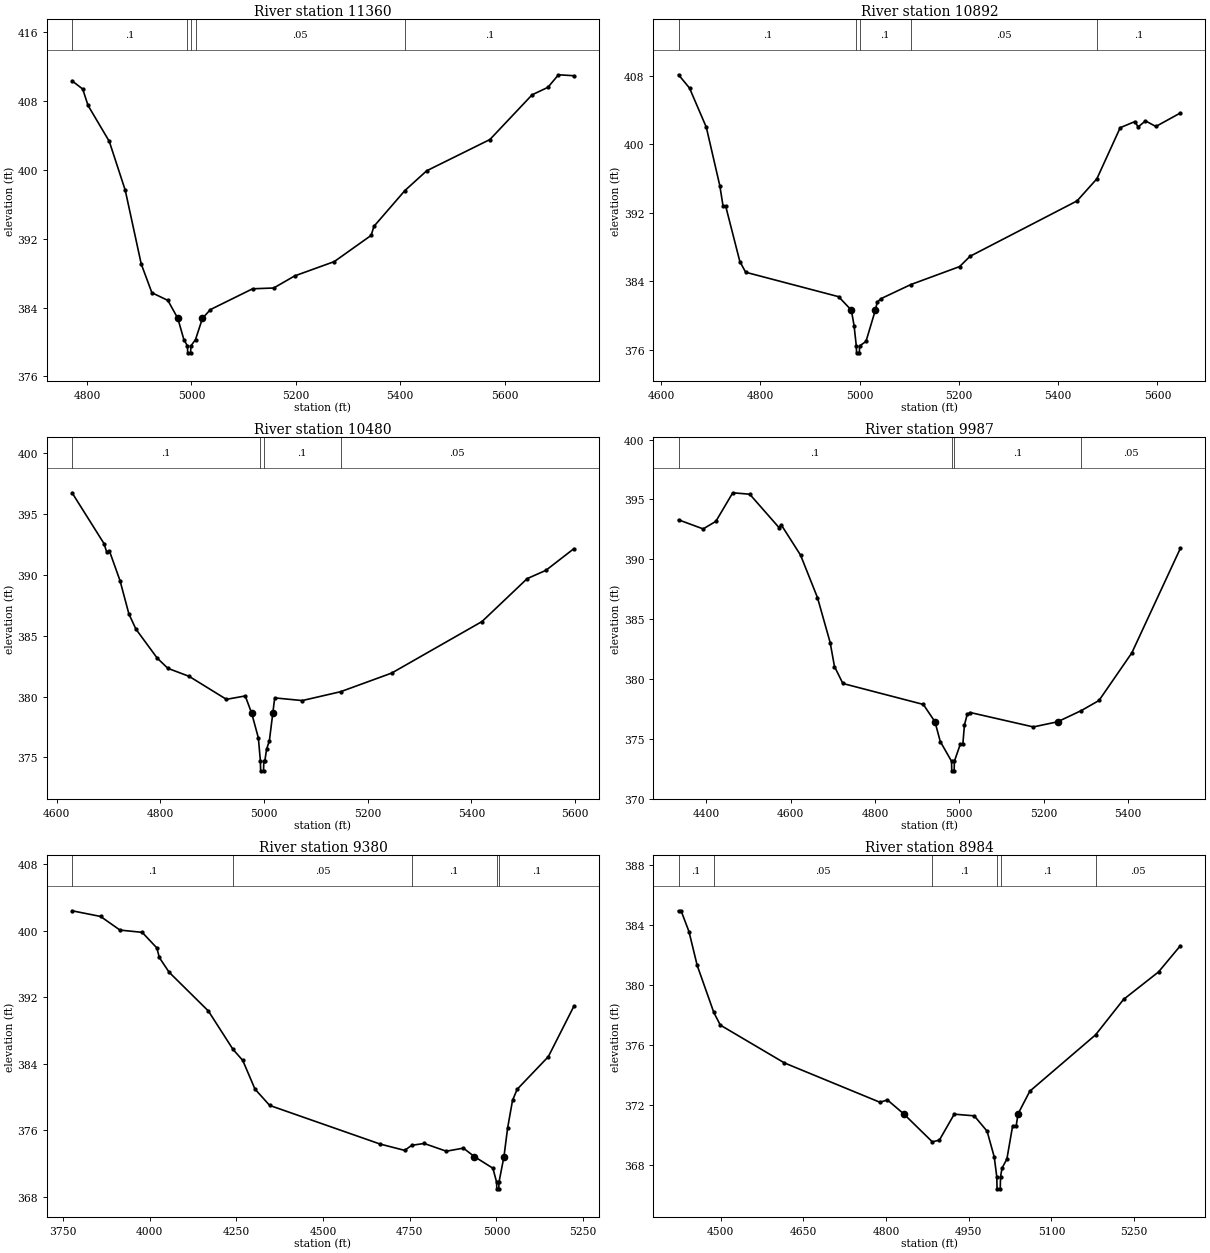
Type RM Length L Ch R = 1 ,11360   ,468,468,468
BEGIN DESCRIPTION:
UNT 050 in RCW 22.0
END DESCRIPTION:
XS GIS Cut Line= 3
      2051724.96     13441024.99        2051475.       13440975.
      2050775.83     13440874.98
#Sta/Elev= 30
  4771.4  410.36  4791.8  409.41    4802   407.5  4842.7  403.32  4873.3  397.63
  4903.9  389.06  4924.3  385.72  4954.9  384.83 4973.94382.7413  4985.5  380.28
  4992.4  379.53  4992.9  378.73  4998.5  378.73    4999  379.53  5007.9  380.28
 5021.13382.7415  5036.4  383.76  5117.2  386.18  5157.6  386.27  5197.9  387.68
  5273.6  389.34  5344.3  392.39  5349.6  393.44  5408.9   397.6  5450.6   399.9
  5571.8  403.54  5652.6  408.74  5682.9  409.61  5703.1  411.07  5732.6  410.96
#Mann= 5 ,-1 , 0
  4771.4      .1       0  4992.4     .07       0    4999      .1       0
  5007.9     .05       0  5408.9      .1       0
Bank Sta=4973.94,5021.13
XS Rating Curve= 0 ,0
Exp/Cntr=0.3,0.1

Type RM Length L Ch R = 1 ,10892   ,412,412,412
BEGIN DESCRIPTION:
UNT 050 in RCW 21.0
END DESCRIPTION:
XS GIS Cut Line= 3
      2051775.01     13440975.03        2051675.       13440625.
      2051312.05     13440089.68
#Sta/Elev= 30
  4635.4  408.09  4657.5  406.54  4691.3  401.98  4718.6  395.14  4725.1  392.77
  4730.3  392.79  4758.9  386.31  4770.6  385.06  4957.8  382.21 4983.53380.6394
    4989  378.83  4993.5  376.46    4994  375.66  4999.6  375.66  5000.1  376.46
    5013  376.99 5031.86380.6395  5035.7  381.57  5042.9  381.97  5103.2  383.62
  5201.6  385.72  5222.6  386.92  5438.2  393.38  5478.1  395.96  5525.1  401.92
    5555  402.64    5561     402    5576  402.71  5596.9  402.06  5646.2  403.63
#Mann= 5 ,-1 , 0
  4635.4      .1       0  4993.5     .07       0  5000.1      .1       0
  5103.2     .05       0  5478.1      .1       0
Bank Sta=4983.53,5031.86
XS Rating Curve= 0 ,0
Exp/Cntr=0.3,0.1

Type RM Length L Ch R = 1 ,10480   ,493,493,493
BEGIN DESCRIPTION:
UNT 050 in RCW 20.0
END DESCRIPTION:
XS GIS Cut Line= 3
      2052125.01     13440875.05      2052042.33     13440516.04
      2051840.94     13439951.81
#Sta/Elev= 30
    4630  396.76  4691.6  392.58  4696.8  391.88  4701.9  391.99  4722.4  389.54
  4739.6  386.79  4753.2  385.54  4794.2  383.16  4814.8  382.32  4855.8  381.66
  4927.6  379.77  4963.9  380.05 4976.29378.6291  4989.2   376.6  4993.1  374.69
  4993.6  373.89  4999.2  373.89  4999.7  374.69  5001.6  374.69  5005.1  375.68
  5010.4  376.36 5017.02378.6288  5020.7  379.89  5073.8  379.67  5147.9   380.4
  5246.2  381.93  5420.4  386.17  5507.5   389.7  5543.6  390.38  5597.5  392.16
#Mann= 4 ,-1 , 0
    4630      .1       0  4993.1     .07       0  4999.7      .1       0
  5147.9     .05       0
Bank Sta=4976.29,5017.02
XS Rating Curve= 0 ,0
Exp/Cntr=0.3,0.1

Type RM Length L Ch R = 1 ,9987    ,607,607,607
BEGIN DESCRIPTION:
UNT 050 in RCW 19.0
END DESCRIPTION:
XS GIS Cut Line= 3
      2052479.83      13440943.1        2052425.       13440275.
      2052035.36     13439932.69
#Sta/Elev= 30
  4334.6   393.3  4392.9  392.54    4423  393.17  4463.1  395.56  4503.3  395.44
  4572.7  392.65  4577.8  392.89  4623.7  390.35  4663.8   386.8  4693.9  383.04
  4704.1  381.04    4724  379.62  4914.6  377.87 4942.21376.4213  4954.8  374.77
  4981.5  373.12    4982  372.32  4987.7  372.32  4988.2  373.12  5002.4  374.56
  5008.3  374.56  5012.1  376.16  5018.7  377.05  5026.3  377.19  5175.3  375.99
 5232.81376.4203  5289.2  377.36  5330.9   378.2  5408.7  382.18  5523.6  390.91
#Mann= 4 ,-1 , 0
  4334.6      .1       0  4981.5     .07       0  4988.2      .1       0
  5289.2     .05       0
Bank Sta=4942.21,5232.81
XS Rating Curve= 0 ,0
Exp/Cntr=0.3,0.1

Type RM Length L Ch R = 1 ,9380    ,396,396,396
BEGIN DESCRIPTION:
UNT 050 in RCW 18.0
END DESCRIPTION:
XS GIS Cut Line= 3
      2053180.38     13440675.36      2052301.01     13439738.26
      2052155.14     13439667.07
#Sta/Elev= 30
  3775.8  402.37  3857.9  401.69  3914.1  400.05    3978  399.78  4020.5   397.9
  4027.4  396.76  4055.7  394.99    4169  390.33  4239.9  385.73  4268.2  384.39
  4303.4  380.95  4345.8  378.99  4664.3  374.35  4735.1  373.59  4755.7   374.2
  4791.3  374.42  4855.3  373.49  4904.6  373.86 4936.12372.8439  4989.6  371.45
  5000.4  369.77  5000.9  368.97  5006.7  368.97  5007.2  369.77 5021.62372.8449
  5032.1  376.27  5046.3   379.6  5059.7  380.93  5149.6  384.85  5223.2   390.9
#Mann= 5 ,-1 , 0
  3775.8      .1       0  4239.9     .05       0  4755.7      .1       0
  5000.4     .07       0  5007.2      .1       0
Bank Sta=4936.12,5021.62
XS Rating Curve= 0 ,0
Exp/Cntr=0.3,0.1

Type RM Length L Ch R = 1 ,8984    ,346,346,346
BEGIN DESCRIPTION:
UNT 050 in RCW 17.0
END DESCRIPTION:
XS GIS Cut Line= 3
      2052969.42     13440177.51        2052625.       13439675.
      2052420.83     13439453.57
#Sta/Elev= 30
  4423.4  384.92    4428  384.92  4442.3  383.54  4457.2  381.29  4487.4  378.15
  4499.2  377.31  4615.6  374.79    4789  372.17  4802.3  372.33 4831.91371.4019
  4883.8  369.54  4896.6  369.65  4923.6  371.38  4959.9  371.27  4983.2  370.25
  4996.2  368.53  5000.8  367.21  5001.3  366.41  5007.1  366.41  5007.6  367.21
  5010.3  367.79  5019.1  368.39  5029.6  370.61    5036  370.61 5039.41371.4026
  5060.7  372.91    5180  376.66  5230.8  379.02  5294.3  380.85  5333.8  382.59
#Mann= 6 ,-1 , 0
  4423.4      .1       0  4487.4     .05       0  4883.8      .1       0
  5000.8     .07       0  5007.6      .1       0    5180     .05       0
Bank Sta=4831.91,5039.41
XS Rating Curve= 0 ,0
Exp/Cntr=0.3,0.1