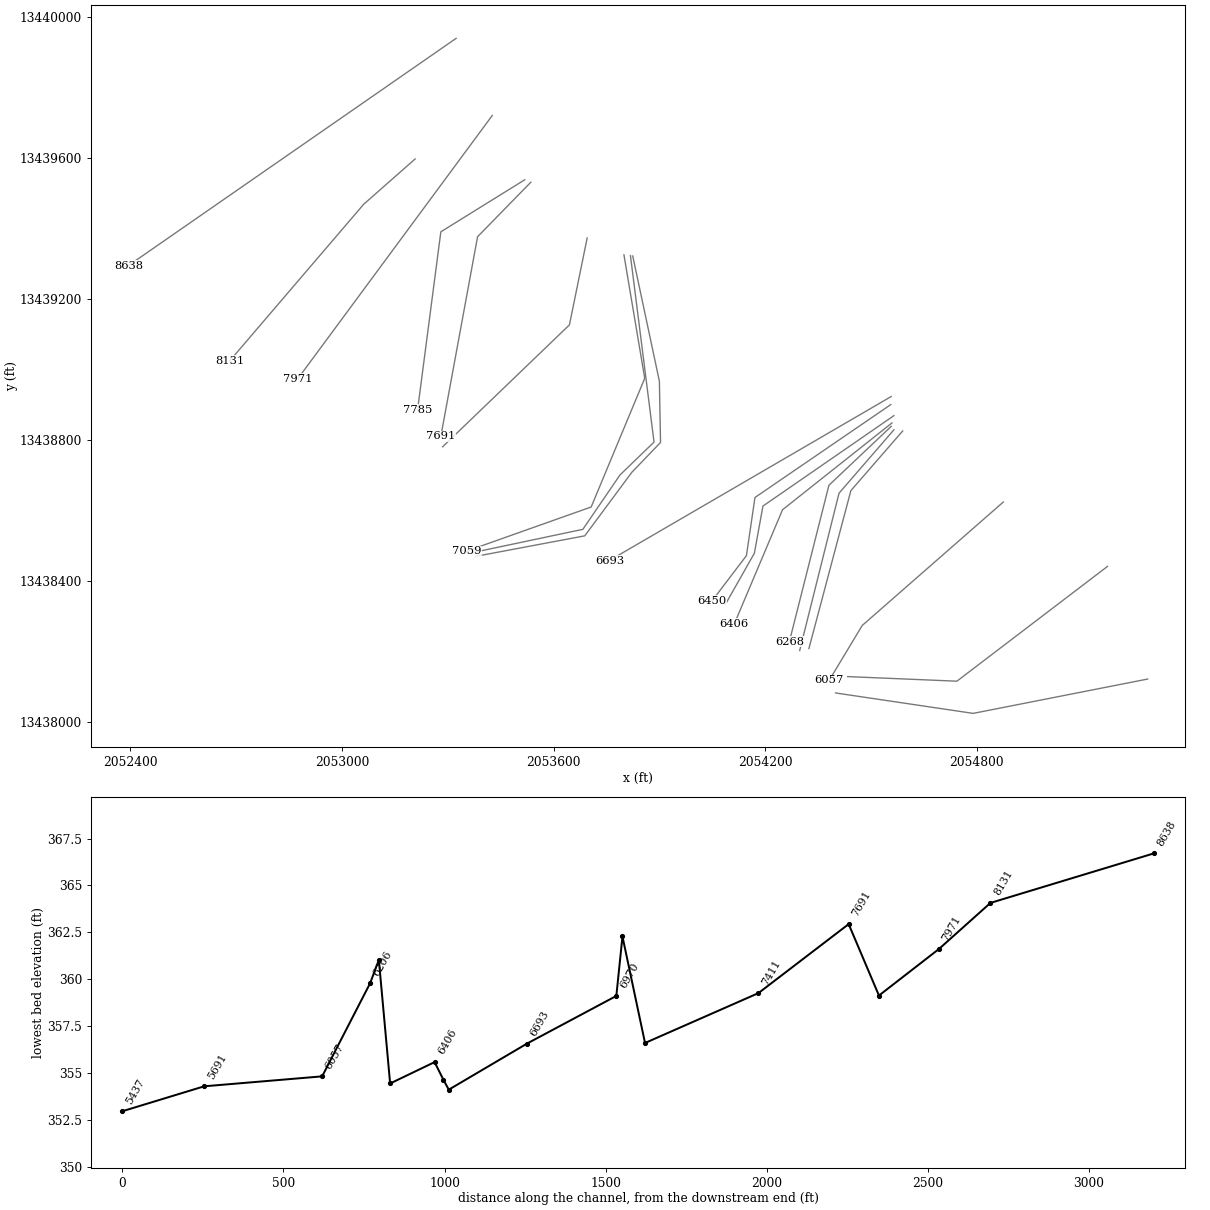
HEC-RAS study UNT 050 in RCW.prj: UNT 050 in RCW Base Level Engineering

--- UNT 050 in RCW.g01 (geometry) --- (continued)

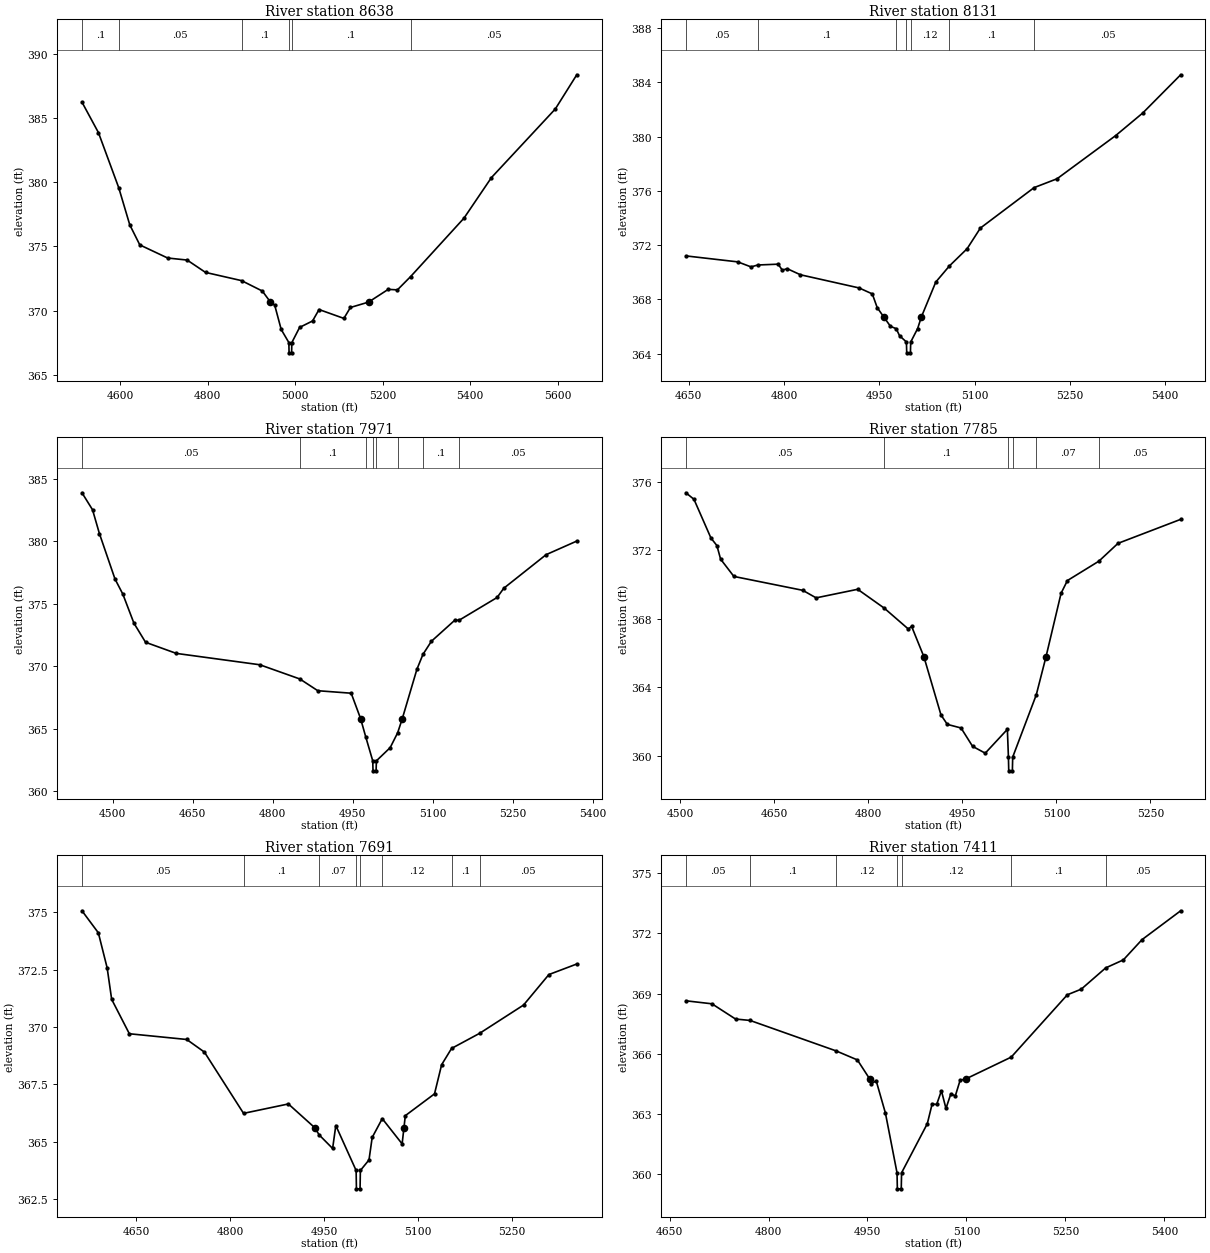
Type RM Length L Ch R = 1 ,8638    ,507,507,507
BEGIN DESCRIPTION:
Mapping XS b4ff8352
END DESCRIPTION:
XS GIS Cut Line= 2
      2053323.55     13439939.63      2052394.73     13439295.53
#Sta/Elev= 30
  4512.9  386.22  4550.5  383.85  4596.9  379.56  4622.1  376.67    4645  375.11
  4708.6  374.09  4753.2  373.93  4795.1  372.97  4877.4  372.33  4924.9  371.52
  4943.5370.6577  4953.1  370.43    4968  368.53  4985.5  367.51    4986  366.71
  4991.8  366.71  4992.3  367.51  5010.1  368.69  5039.6  369.19  5054.5  370.08
  5111.2  369.39  5126.1  370.24 5167.54 370.658  5212.5  371.65  5233.5  371.61
  5263.8  372.65  5385.5  377.19  5448.3  380.35  5594.2  385.69  5643.2  388.35
#Mann= 6 ,-1 , 0
  4512.9      .1       0  4596.9     .05       0  4877.4      .1       0
  4985.5     .07       0  4992.3      .1       0  5263.8     .05       0
Bank Sta=4943.5,5167.54
XS Rating Curve= 0 ,0
Exp/Cntr=0.3,0.1

Type RM Length L Ch R = 1 ,8131    ,160,160,160
BEGIN DESCRIPTION:
UNT 050 in RCW 16.0
END DESCRIPTION:
XS GIS Cut Line= 3
      2053207.23     13439597.61      2053061.43     13439469.17
      2052681.21     13439024.71
#Sta/Elev= 30
  4645.3  371.21    4727  370.77  4747.9   370.4  4758.6  370.54  4790.6   370.6
  4797.2  370.16  4804.8  370.27  4825.7  369.82  4918.1  368.85  4938.9  368.41
  4946.6   367.4 4957.29366.6901  4967.5  366.02  4976.5  365.85  4981.8  365.33
  4992.6  364.87  4993.1  364.07  4998.9  364.07  4999.4  364.87  5010.3  365.86
 5015.95366.6904  5038.8  369.28  5060.3  370.47  5088.2  371.74  5109.1  373.26
  5193.7  376.24  5229.8  376.89  5322.1  380.07  5364.9  381.74  5424.5  384.55
#Mann= 7 ,-1 , 0
  4645.3     .05       0  4758.6      .1       0  4976.5     .12       0
  4992.6     .07       0  4999.4     .12       0  5060.3      .1       0
  5193.7     .05       0
Bank Sta=4957.29,5015.95
XS Rating Curve= 0 ,0
Exp/Cntr=0.3,0.1

Type RM Length L Ch R = 1 ,7971    ,186,186,186
BEGIN DESCRIPTION:
UNT 050 in RCW 15.0
END DESCRIPTION:
XS GIS Cut Line= 3
      2053426.01     13439720.91       2053170.8     13439375.42
      2052874.97     13438974.96
#Sta/Elev= 30
  4442.3  383.89  4462.1  382.53    4475  380.62  4504.2  376.98  4518.9  375.77
  4539.7  373.44  4561.5  371.91  4619.1  371.02  4775.6  370.11  4850.7  368.97
  4884.3  368.03  4946.9  367.83 4964.47365.8031  4974.3  364.31  4987.3  362.41
  4987.8  361.61  4993.6  361.61  4994.1  362.41    5020  363.47    5034  364.66
 5042.77365.8028  5070.1  369.75  5081.4  370.94  5097.2  371.99  5141.1  373.68
  5149.3  373.68  5220.4   375.5  5232.9  376.24  5312.2  378.93  5369.7  380.02
#Mann= 8 ,-1 , 0
  4442.3     .05       0  4850.7      .1       0  4974.3     .07       0
  4987.3     .07       0  4994.1     .07       0    5034     .12       0
  5081.4      .1       0  5149.3     .05       0
Bank Sta=4964.47,5042.77
XS Rating Curve= 0 ,0
Exp/Cntr=0.3,0.1

Type RM Length L Ch R = 1 ,7785    ,94,94,94
BEGIN DESCRIPTION:
Mapping XS 137d51bd
END DESCRIPTION:
XS GIS Cut Line= 3
      2053518.03     13439538.61      2053280.18     13439391.04
       2053214.2     13438885.84
#Sta/Elev= 30
  4508.9  375.35  4521.8  374.97  4548.9  372.71  4558.4  372.27  4564.3  371.48
  4585.5  370.47  4695.4  369.66  4716.7  369.22    4783  369.72  4825.4  368.62
  4863.9   367.4    4869  367.56 4888.59365.7909  4915.9  362.39    4926  361.84
  4947.9  361.63  4966.3  360.56  4986.5  360.16  5021.8  361.55  5023.5  359.93
    5024  359.13  5029.8  359.13  5030.3  359.93  5067.9  363.56 5083.49 365.791
  5107.5  369.49  5117.6  370.23  5167.8  371.36  5198.3   372.4  5298.3   373.8
#Mann= 6 ,-1 , 0
  4508.9     .05       0  4825.4      .1       0  5023.5     .07       0
  5030.3      .1       0  5067.9     .07       0  5167.8     .05       0
Bank Sta=4888.59,5083.49
XS Rating Curve= 0 ,0
Exp/Cntr=0.3,0.1

Type RM Length L Ch R = 1 ,7691    ,280,280,280
BEGIN DESCRIPTION:
Mapping XS ff975f41
END DESCRIPTION:
XS GIS Cut Line= 3
      2053535.41      13439531.7      2053384.34     13439377.15
      2053280.17     13438811.18
#Sta/Elev= 30
  4562.8  375.06    4589   374.1  4603.1  372.57  4610.3   371.2  4638.6   369.7
  4730.4  369.45  4758.7   368.9  4821.3  366.23    4893  366.64 4935.35365.6015
  4942.3  365.29  4963.8   364.7  4968.9   365.7  5001.4  363.74  5001.9  362.94
  5007.7  362.94  5008.2  363.74    5022   364.2  5027.1  365.18  5043.2     366
    5075   364.9 5077.91365.6018  5080.1  366.13  5126.8  367.08  5138.2  368.35
  5154.1  369.06  5199.1  369.72  5269.2  370.95  5309.8  372.28  5354.4  372.74
#Mann= 8 ,-1 , 0
  4562.8     .05       0  4821.3      .1       0  4942.3     .07       0
  5001.4     .07       0  5008.2     .07       0  5043.2     .12       0
  5154.1      .1       0  5199.1     .05       0
Bank Sta=4935.35,5077.91
XS Rating Curve= 0 ,0
Exp/Cntr=0.3,0.1

Type RM Length L Ch R = 1 ,7411    ,352,352,352
BEGIN DESCRIPTION:
UNT 050 in RCW 14.0
END DESCRIPTION:
XS GIS Cut Line= 3
       2053695.1     13439373.65      2053644.76     13439127.15
      2053285.38     13438781.66
#Sta/Elev= 30
  4674.7  368.64  4714.2  368.49    4750  367.73    4772  367.66  4902.5  366.14
  4934.7  365.69 4953.11364.7551  4955.8  364.49  4963.1  364.66  4977.2  363.04
  4994.8  360.06  4995.3  359.26  5001.2  359.26  5001.7  360.06  5040.7  362.51
    5048  363.49  5054.9  363.47  5062.1  364.15    5069  363.27  5076.3  363.99
  5083.2   363.9  5090.4  364.67 5099.84364.7548  5167.9  365.83    5253  368.94
  5274.1  369.22  5311.1  370.28  5337.9  370.68  5366.2  371.69  5424.8  373.13
#Mann= 7 ,-1 , 0
  4674.7     .05       0    4772      .1       0  4902.5     .12       0
  4994.8     .07       0  5001.7     .12       0  5167.9      .1       0
  5311.1     .05       0
Bank Sta=4953.11,5099.84
XS Rating Curve= 0 ,0
Exp/Cntr=0.3,0.1

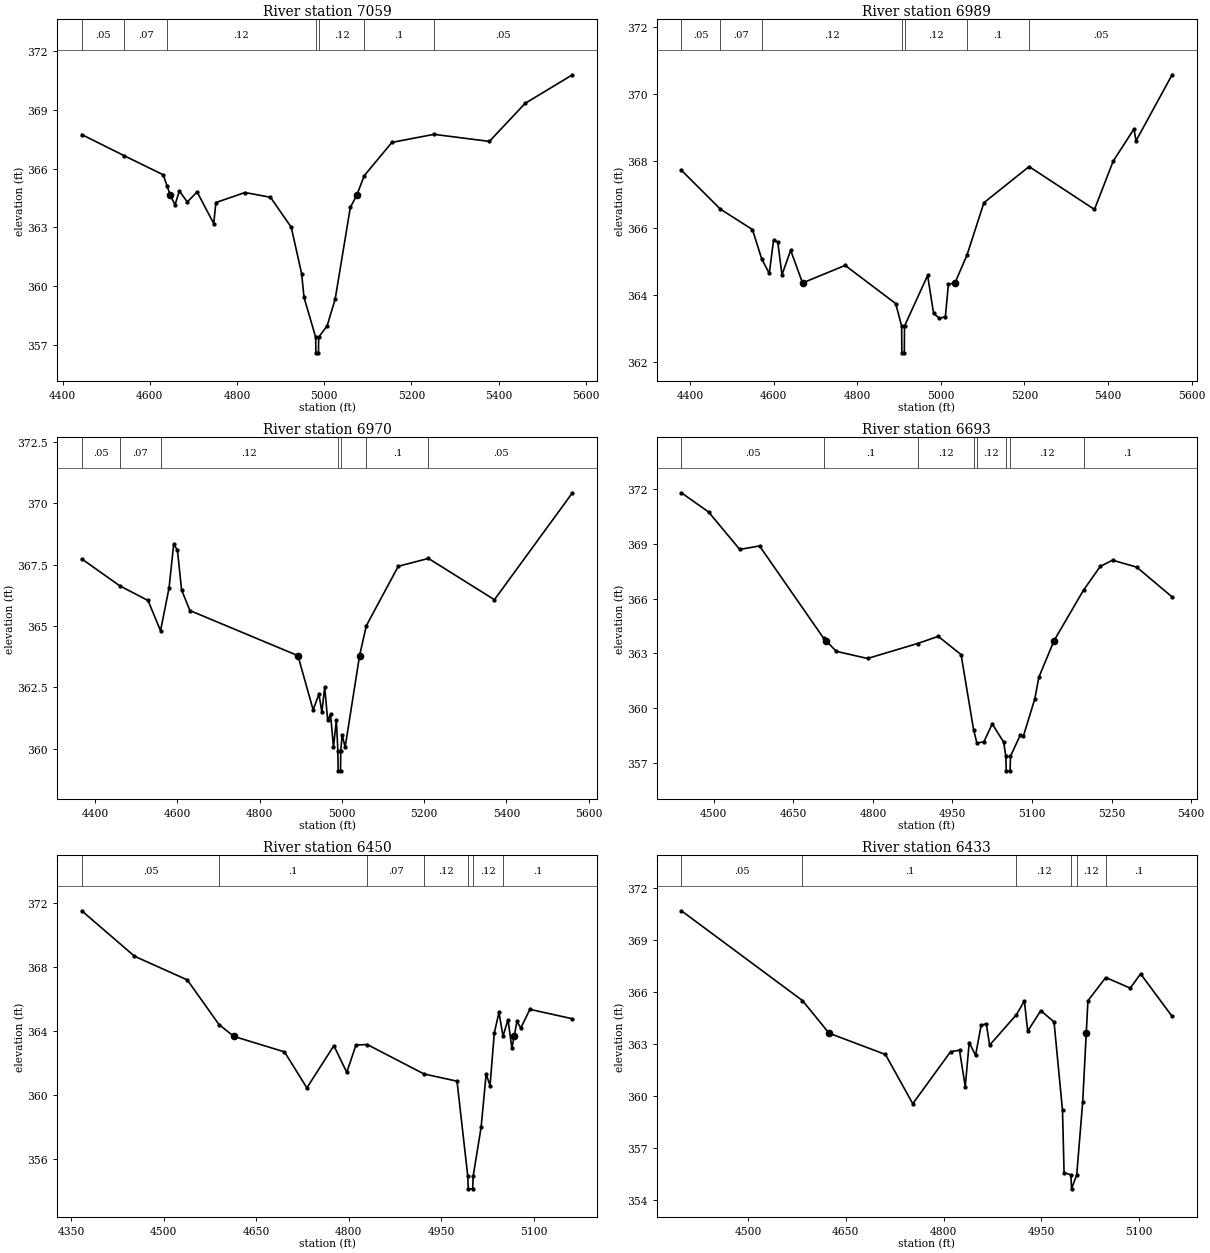
Type RM Length L Ch R = 1 ,7059    ,70,70,70
BEGIN DESCRIPTION:
UNT 050 in RCW 13.0
END DESCRIPTION:
XS GIS Cut Line= 4
      2053799.31      13439325.8      2053858.25     13438975.65
      2053706.46     13438610.88      2053352.71     13438485.44
#Sta/Elev= 30
  4443.9  367.74  4540.3  366.67  4630.5  365.69  4639.8   365.1 4646.82364.6533
  4657.7  364.15  4667.8  364.86    4686   364.3  4708.4  364.81  4746.6   363.2
  4751.6  364.27  4818.2  364.78  4876.7  364.54  4924.4  363.01  4948.2  360.64
  4953.7  359.43  4980.4   357.4  4980.9   356.6  4986.8   356.6  4987.3   357.4
  5006.8  357.98  5025.2  359.35  5059.9  364.02 5074.83364.6532  5091.8  365.64
  5155.3  367.34  5251.9  367.75  5378.8  367.39  5460.8  369.33  5569.4  370.79
#Mann= 7 ,-1 , 0
  4443.9     .05       0  4540.3     .07       0  4639.8     .12       0
  4980.4     .07       0  4987.3     .12       0  5091.8      .1       0
  5251.9     .05       0
Bank Sta=4646.82,5074.83
XS Rating Curve= 0 ,0
Exp/Cntr=0.3,0.1

Type RM Length L Ch R = 1 ,6989    ,19,19,19
BEGIN DESCRIPTION:
Mapping XS 695d6a2c
END DESCRIPTION:
XS GIS Cut Line= 5
      2053817.75     13439323.66      2053884.63      13438794.9
      2053788.06     13438701.59      2053682.81     13438547.51
      2053369.56     13438481.39
#Sta/Elev= 30
  4379.2  367.73  4472.4  366.57  4549.2  365.96  4571.4  365.08  4589.5  364.65
  4599.6  365.64  4609.7  365.59  4619.8  364.61  4640.6  365.34 4668.97364.3663
    4771  364.89  4891.9  363.75  4906.1  363.08  4906.6  362.28  4912.5  362.28
    4913  363.08  4968.3  364.59  4982.5  363.46  4996.6  363.31  5010.8  363.36
    5018  364.33 5033.69364.3662  5062.8  365.21  5102.9  366.76  5211.1  367.84
  5367.5  366.56  5412.2     368  5461.9  368.96    5467  368.61  5553.2  370.58
#Mann= 7 ,-1 , 0
  4379.2     .05       0  4472.4     .07       0  4571.4     .12       0
  4906.1     .07       0    4913     .12       0  5062.8      .1       0
  5211.1     .05       0
Bank Sta=4668.97,5033.69
XS Rating Curve= 0 ,0
Exp/Cntr=0.3,0.1

Type RM Length L Ch R = 1 ,6970    ,277,277,277
BEGIN DESCRIPTION:
Mapping XS 2f74e679
END DESCRIPTION:
XS GIS Cut Line= 6
      2053824.27     13439322.53      2053899.82     13438967.43
      2053903.08     13438793.82       2053821.7     13438709.18
      2053688.23     13438529.06      2053378.45     13438470.77
#Sta/Elev= 30
  4367.2  367.73  4460.1  366.63  4528.3  366.04  4558.8  364.81  4579.4  366.54
  4590.8  368.32  4599.8   368.1    4610  366.47  4630.2  365.63 4892.97363.7943
    4930  361.59    4944  362.23  4951.2  361.51  4958.1  362.51  4965.4  361.16
  4972.3  361.41  4979.5  360.07  4986.4  361.19  4990.2  359.91  4990.7  359.11
  4996.6  359.11  4997.1  359.91  5000.6  360.57  5007.8  360.07 5042.89363.7943
  5059.3  365.01    5137  367.43  5210.4  367.75  5370.9  366.07  5560.7  370.42
#Mann= 7 ,-1 , 0
  4367.2     .05       0  4460.1     .07       0  4558.8     .12       0
  4990.2     .07       0  4997.1     .12       0  5059.3      .1       0
  5210.4     .05       0
Bank Sta=4892.97,5042.89
XS Rating Curve= 0 ,0
Exp/Cntr=0.3,0.1

Type RM Length L Ch R = 1 ,6693    ,243,243,243
BEGIN DESCRIPTION:
Mapping XS 67496026
END DESCRIPTION:
XS GIS Cut Line= 2
      2054557.13     13438924.07      2053757.98     13438459.03
#Sta/Elev= 30
  4439.2  371.79  4490.4  370.74  4549.1  368.69  4586.4  368.88  4707.1  363.83
 4711.39 363.696  4731.2  363.11  4789.9  362.72  4884.3  363.54  4923.1  363.93
  4966.2  362.93  4989.7  358.83    4996  358.09  5009.2  358.16  5024.9  359.14
  5046.4  358.14  5050.5  357.37  5051.3  356.57  5058.5  356.57  5059.3  357.37
  5077.9  358.54  5083.7  358.48  5105.2  360.52  5112.7  361.69 5141.35 363.696
  5196.9  366.46  5228.5  367.76  5251.6   368.1  5297.1  367.72  5363.8  366.09
#Mann= 8 ,-1 , 0
  4439.2     .05       0  4707.1      .1       0  4884.3     .12       0
  4989.7     .07       0    4996     .12       0  5050.5     .07       0
  5059.3     .12       0  5196.9      .1       0
Bank Sta=4711.39,5141.35
XS Rating Curve= 0 ,0
Exp/Cntr=0.3,0.1

Type RM Length L Ch R = 1 ,6450    ,17,17,17
BEGIN DESCRIPTION:
Mapping XS b1f0fa6c
END DESCRIPTION:
XS GIS Cut Line= 4
      2054556.02     13438901.26      2054170.87     13438637.79
      2054146.57     13438472.85      2054048.82     13438344.24
#Sta/Elev= 30
  4367.5  371.49  4452.9  368.65  4538.4  367.17  4589.8  364.38 4613.89363.6391
  4695.9  362.67  4732.2  360.42  4775.9  363.06  4796.8  361.39  4811.7   363.1
    4830  363.13  4921.9  361.29  4975.4  360.84  4992.8  354.91  4993.6  354.11
  5000.8  354.11  5001.6  354.91  5014.4  357.95  5022.6  361.29  5028.9  360.56
  5035.8  363.85  5043.4  365.14  5049.9  363.65    5058  364.68  5064.3   362.9
 5067.93363.6393  5072.5  364.57  5078.8  364.16  5093.4  365.33  5162.4  364.74
#Mann= 7 ,-1 , 0
  4367.5     .05       0  4589.8      .1       0    4830     .07       0
  4921.9     .12       0  4992.8     .07       0  5001.6     .12       0
  5049.9      .1       0
Bank Sta=4613.89,5067.93
XS Rating Curve= 0 ,0
Exp/Cntr=0.3,0.1

Type RM Length L Ch R = 1 ,6433    ,27,27,27
BEGIN DESCRIPTION:
Mapping XS 03b7465d
END DESCRIPTION:
XS GIS Cut Line= 4
      2054564.75     13438869.83      2054193.44     13438613.48
      2054169.14      13438479.8      2054087.52     13438335.68
#Sta/Elev= 30
  4397.9  370.69  4583.6  365.51 4624.43363.6282  4710.9   362.4  4752.8  359.56
  4810.8  362.56  4824.5  362.65  4833.3  360.55  4839.4  363.09  4849.1  362.35
  4857.7  364.09  4865.6  364.17  4870.7  362.94  4911.9   364.7    4924  365.49
  4929.1  363.75  4949.2  364.93  4969.5  364.28  4982.5  359.17  4984.9  355.59
  4995.5  355.45  4996.3  354.65  5004.3  355.45  5013.5  359.68 5018.93363.6305
  5021.5   365.5  5048.8  366.84  5086.4  366.23  5102.3  367.05  5150.6   364.6
#Mann= 6 ,-1 , 0
  4397.9     .05       0  4583.6      .1       0  4911.9     .12       0
  4995.5     .07       0  5004.3     .12       0  5048.8      .1       0
Bank Sta=4624.43,5018.93
XS Rating Curve= 0 ,0
Exp/Cntr=0.3,0.1

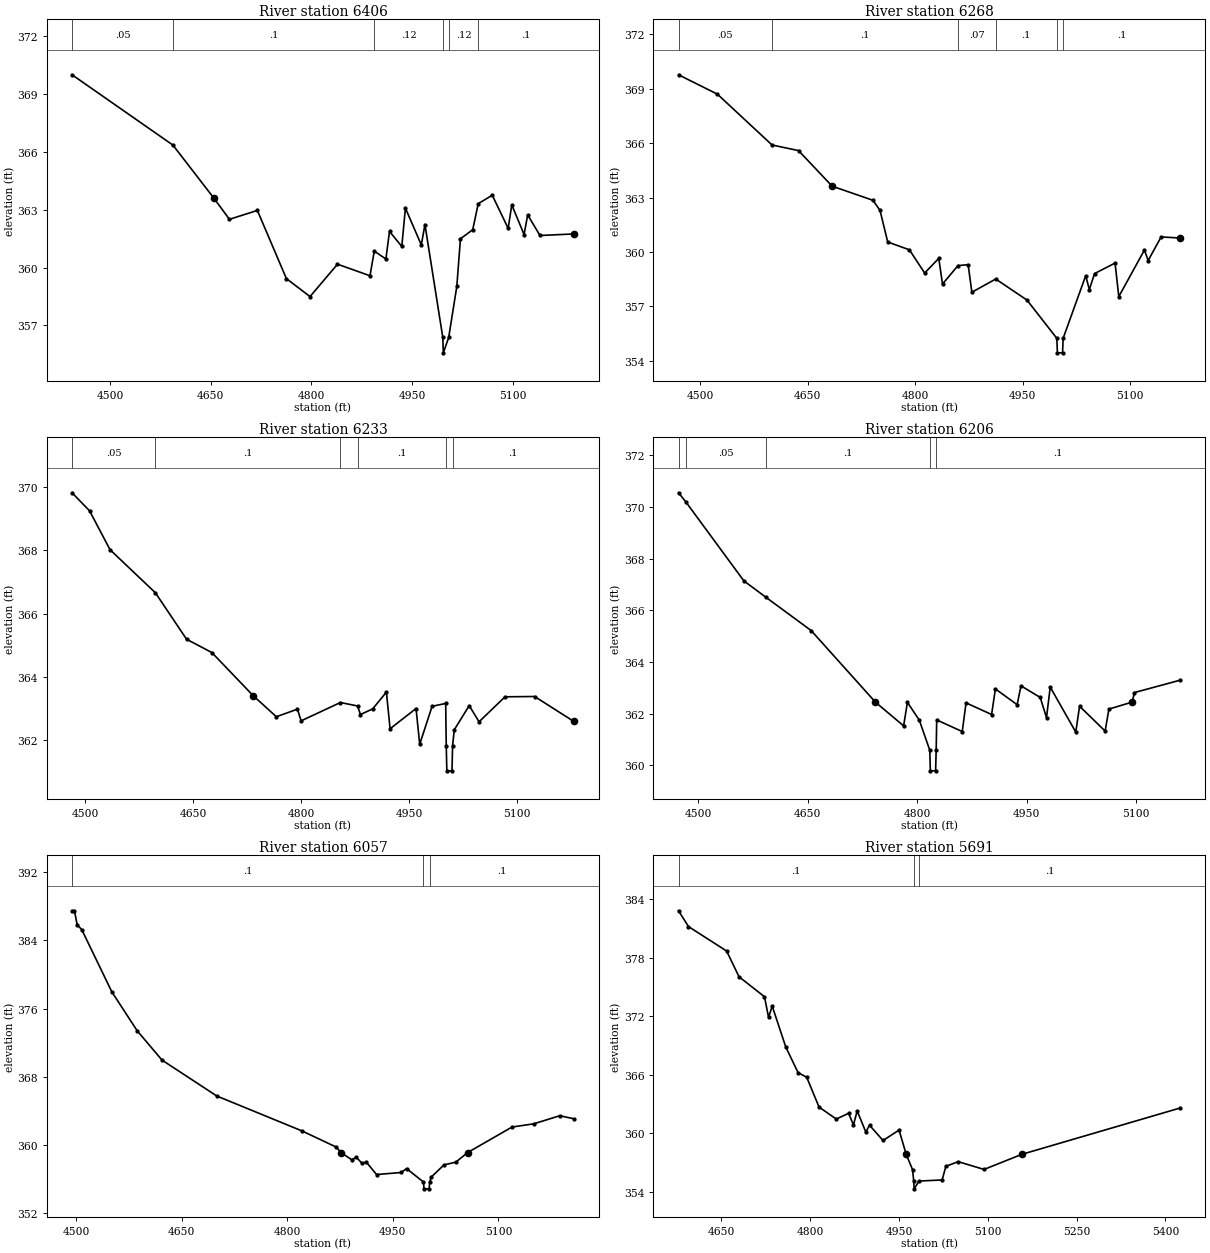
Type RM Length L Ch R = 1 ,6406    ,138,138,138
BEGIN DESCRIPTION:
Mapping XS 9f7214fe
END DESCRIPTION:
XS GIS Cut Line= 3
      2054559.32     13438849.22        2054249.     13438603.06
      2054112.17     13438279.18
#Sta/Elev= 30
  4443.4  370.01  4593.7  366.36 4654.18363.6314  4677.9  362.51  4719.5  362.97
  4762.8  359.43    4798   358.5  4838.9  360.18  4887.3  359.58  4893.7  360.86
    4911  360.45  4916.4  361.88  4934.7   361.1  4940.1  363.09  4963.8  361.18
  4969.2  362.24  4995.8  356.38  4996.6  355.58  5004.6  356.38  5016.7  359.03
  5022.1   361.5  5040.4  361.97  5048.6  363.32  5069.5  363.76  5093.2  362.04
  5098.6  363.26  5116.9  361.72  5122.3  362.74  5140.6  361.67  5191.1  361.75
#Mann= 6 ,-1 , 0
  4443.4     .05       0  4593.7      .1       0  4893.7     .12       0
  4995.8     .07       0  5004.6     .12       0  5048.6      .1       0
Bank Sta=4654.18,5191.1
XS Rating Curve= 0 ,0
Exp/Cntr=0.3,0.1

Type RM Length L Ch R = 1 ,6268    ,35,35,35
BEGIN DESCRIPTION:
Mapping XS a00780ca
END DESCRIPTION:
XS GIS Cut Line= 3
      2054557.14     13438839.44      2054380.56     13438672.53
      2054268.33     13438228.99
#Sta/Elev= 30
  4469.7  369.77    4524   368.7  4600.2   365.9  4637.2  365.59 4684.15 363.628
  4741.1  362.85    4751  362.29  4761.7  360.55    4792  360.12  4813.3  358.84
    4833  359.65  4838.2  358.23  4859.8  359.25    4874   359.3  4879.2  357.78
  4912.5  358.51  4956.1  357.35  4997.8  355.24  4998.6  354.44  5005.8  354.44
  5006.6  355.24  5038.1  358.69  5043.2  357.93  5050.5  358.81  5079.1  359.39
  5084.3  357.54  5120.1  360.11  5125.3  359.53  5143.4  360.83  5170.2  360.77
#Mann= 6 ,-1 , 0
  4469.7     .05       0  4600.2      .1       0  4859.8     .07       0
  4912.5      .1       0  4997.8     .07       0  5006.6      .1       0
Bank Sta=4684.15,5170.2
XS Rating Curve= 0 ,0
Exp/Cntr=0.3,0.1

Type RM Length L Ch R = 1 ,6233    ,27,27,27
BEGIN DESCRIPTION:
Mapping XS 44f583eb
END DESCRIPTION:
XS GIS Cut Line= 3
      2054564.74     13438829.68      2054409.15     13438649.92
      2054297.62      13438203.8
#Sta/Elev= 30
  4481.4  369.82  4505.7  369.25  4534.2  368.02  4597.2  366.66  4640.6  365.19
  4675.7  364.77 4733.16363.4068  4765.4  362.74  4794.7  362.98  4799.8  362.61
  4854.5  363.19  4878.3  363.08  4882.3  362.81  4899.4  362.99  4918.4  363.52
  4923.5  362.36  4959.6     363  4964.7  361.87  4981.9  363.07  5000.8  363.16
  5001.6  361.83  5002.4  361.03  5009.6  361.03  5010.4  361.83  5012.8  362.33
  5033.5  363.09  5047.2  362.58  5083.3  363.37  5124.5  363.38    5179  362.59
#Mann= 6 ,-1 , 0
  4481.4     .05       0  4597.2      .1       0  4854.5     .07       0
  4878.3      .1       0  5001.6     .07       0  5010.4      .1       0
Bank Sta=4733.16,5179
XS Rating Curve= 0 ,0
Exp/Cntr=0.3,0.1

Type RM Length L Ch R = 1 ,6206    ,149,149,149
BEGIN DESCRIPTION:
Mapping XS 1c24112a
END DESCRIPTION:
XS GIS Cut Line= 3
      2054589.66     13438826.39      2054442.75     13438657.26
       2054323.8     13438209.52
#Sta/Elev= 30
  4473.2  370.55  4483.4  370.19  4562.7  367.14  4593.2   366.5  4654.8  365.22
 4742.84362.4495  4781.5  361.53  4786.7  362.44    4803  361.75  4817.3  360.59
  4818.1  359.79  4825.3  359.79  4826.1  360.59  4826.8  361.76  4861.8  361.31
    4867  362.42    4902  361.97  4907.2  362.96    4937  362.35  4942.2  363.08
  4968.6  362.63  4977.2  361.85  4982.3  363.03  5017.3  361.29  5022.5  362.29
  5057.5  361.33  5062.7  362.18 5094.49362.4496  5097.7  362.82  5160.5   363.3
#Mann= 5 ,-1 , 0
  4473.2      .1       0  4483.4     .05       0  4593.2      .1       0
  4817.3     .07       0  4826.1      .1       0
Bank Sta=4742.84,5094.49
XS Rating Curve= 0 ,0
Exp/Cntr=0.3,0.1

Type RM Length L Ch R = 1 ,6057    ,366,366,366
BEGIN DESCRIPTION:
UNT 050 in RCW 11.0
END DESCRIPTION:
XS GIS Cut Line= 3
      2054875.03     13438625.02        2054475.       13438275.
      2054381.56     13438119.81
#Sta/Elev= 30
  4494.4  387.49  4497.8  387.49  4501.6  385.85  4508.2  385.27  4550.9  377.96
    4587  373.38  4622.1  369.95  4699.9  365.73  4820.5  361.64  4869.8  359.72
  4876.2359.0884  4891.6  358.24  4898.3  358.52  4905.9  357.84  4912.5  357.95
  4926.8   356.5  4961.9  356.74  4969.5   357.2  4993.5  355.62  4994.3  354.82
  5001.5  354.82  5002.4  355.62  5004.6  356.21  5022.6  357.63  5039.5  357.96
 5056.31359.0887  5119.3  362.08  5150.2  362.46  5187.1  363.41  5207.1  363.05
#Mann= 3 ,-1 , 0
  4494.4      .1       0  4993.5     .07       0  5002.4      .1       0
Bank Sta=4876.2,5056.31
XS Rating Curve= 0 ,0
Exp/Cntr=0.3,0.1

Type RM Length L Ch R = 1 ,5691    ,254,254,254
BEGIN DESCRIPTION:
Mapping XS 60a40261
END DESCRIPTION:
XS GIS Cut Line= 3
      2055170.41     13438442.45      2054743.36     13438116.95
      2054433.48     13438129.97
#Sta/Elev= 30
    4578  382.82  4594.8   381.2  4659.2  378.69  4680.1  376.05  4723.1     374
  4729.9   371.9  4736.2  373.03    4759  368.85  4779.8  366.21  4794.4  365.74
  4815.2  362.68  4844.3  361.45  4865.1  362.04  4873.3  360.84  4879.6  362.29
  4894.2  360.11  4900.4  360.82  4923.2  359.25  4950.3  360.32  4962.3357.8342
  4973.1  356.25    4975  355.09  4975.8  354.29  4983.9  355.09    5023   355.2
  5029.3   356.6  5050.1  357.08  5093.7  356.28 5157.68357.8328  5425.1  362.59
#Mann= 3 ,-1 , 0
    4578      .1       0    4975     .07       0  4983.9      .1       0
Bank Sta=4962.3,5157.68
XS Rating Curve= 0 ,0
Exp/Cntr=0.3,0.1

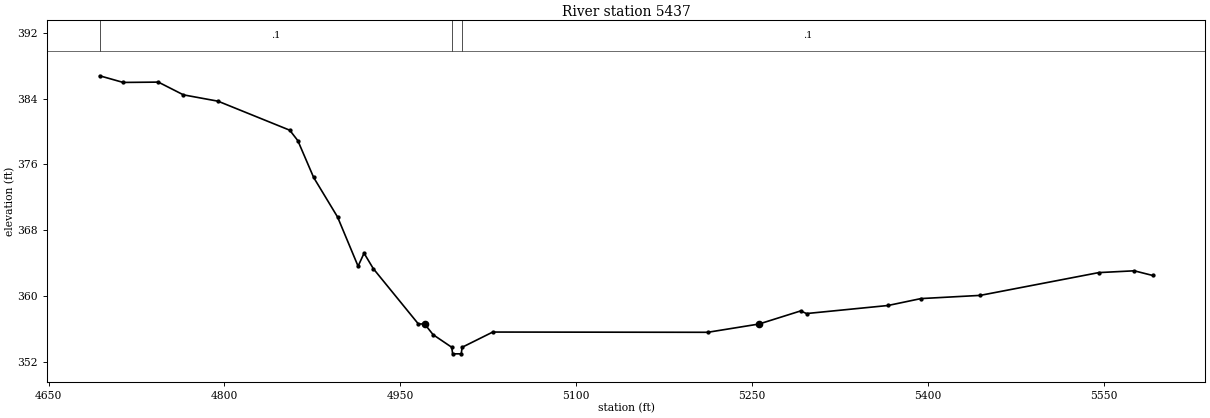
Type RM Length L Ch R = 1 ,5437    ,299,299,299
BEGIN DESCRIPTION:
UNT 050 in RCW 10.0
END DESCRIPTION:
XS GIS Cut Line= 3
      2055284.14     13438123.01      2054789.58     13438025.69
      2054399.39     13438083.57
#Sta/Elev= 30
  4693.5  386.78  4713.6  385.97  4743.6  386.01    4765  384.46  4794.5  383.69
  4855.7  380.16  4862.6  378.89  4876.1  374.41  4896.5   369.6    4914  363.62
  4919.1   365.2    4927  363.32  4965.4   356.6  4970.8 356.586    4978  355.29
  4993.9  353.76  4994.7  352.96    5002  352.96  5002.8  353.76  5028.9  355.61
  5212.3  355.58 5256.06356.5864  5291.6  358.18  5296.6  357.86  5366.1  358.84
  5394.2  359.68  5444.8  360.07  5545.9  362.84  5576.2  363.06    5592  362.49
#Mann= 3 ,-1 , 0
  4693.5      .1       0  4993.9     .07       0  5002.8      .1       0
Bank Sta=4970.8,5256.06
XS Rating Curve= 0 ,0
Exp/Cntr=0.3,0.1