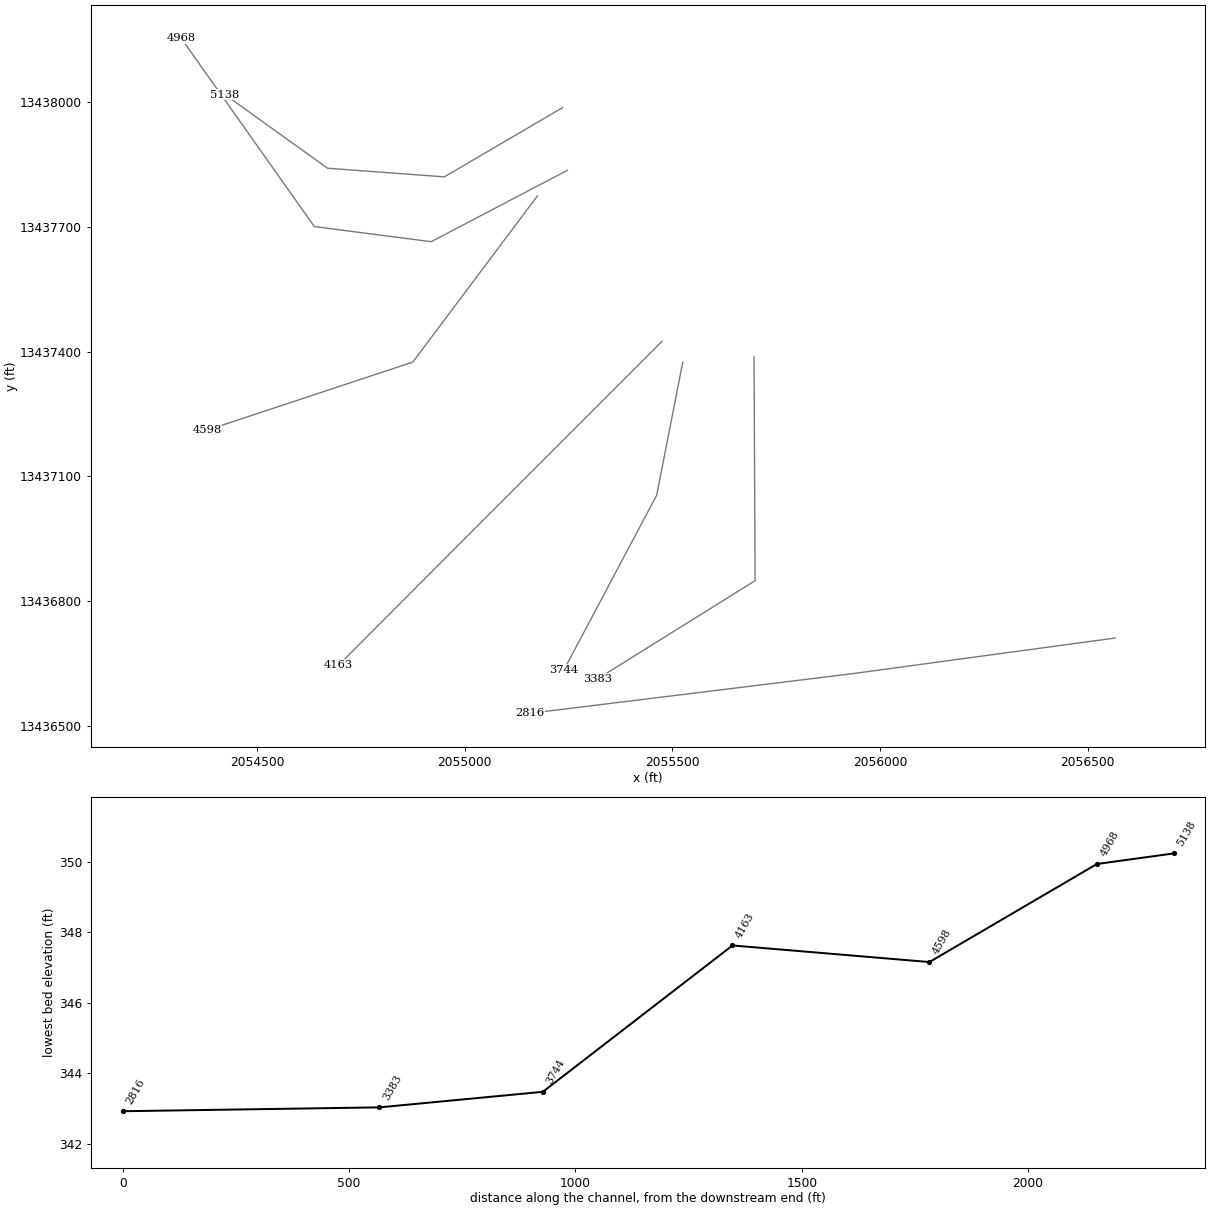
HEC-RAS study UNT 050 in RCW.prj: UNT 050 in RCW Base Level Engineering

--- UNT 050 in RCW.g01 (geometry) --- (continued)

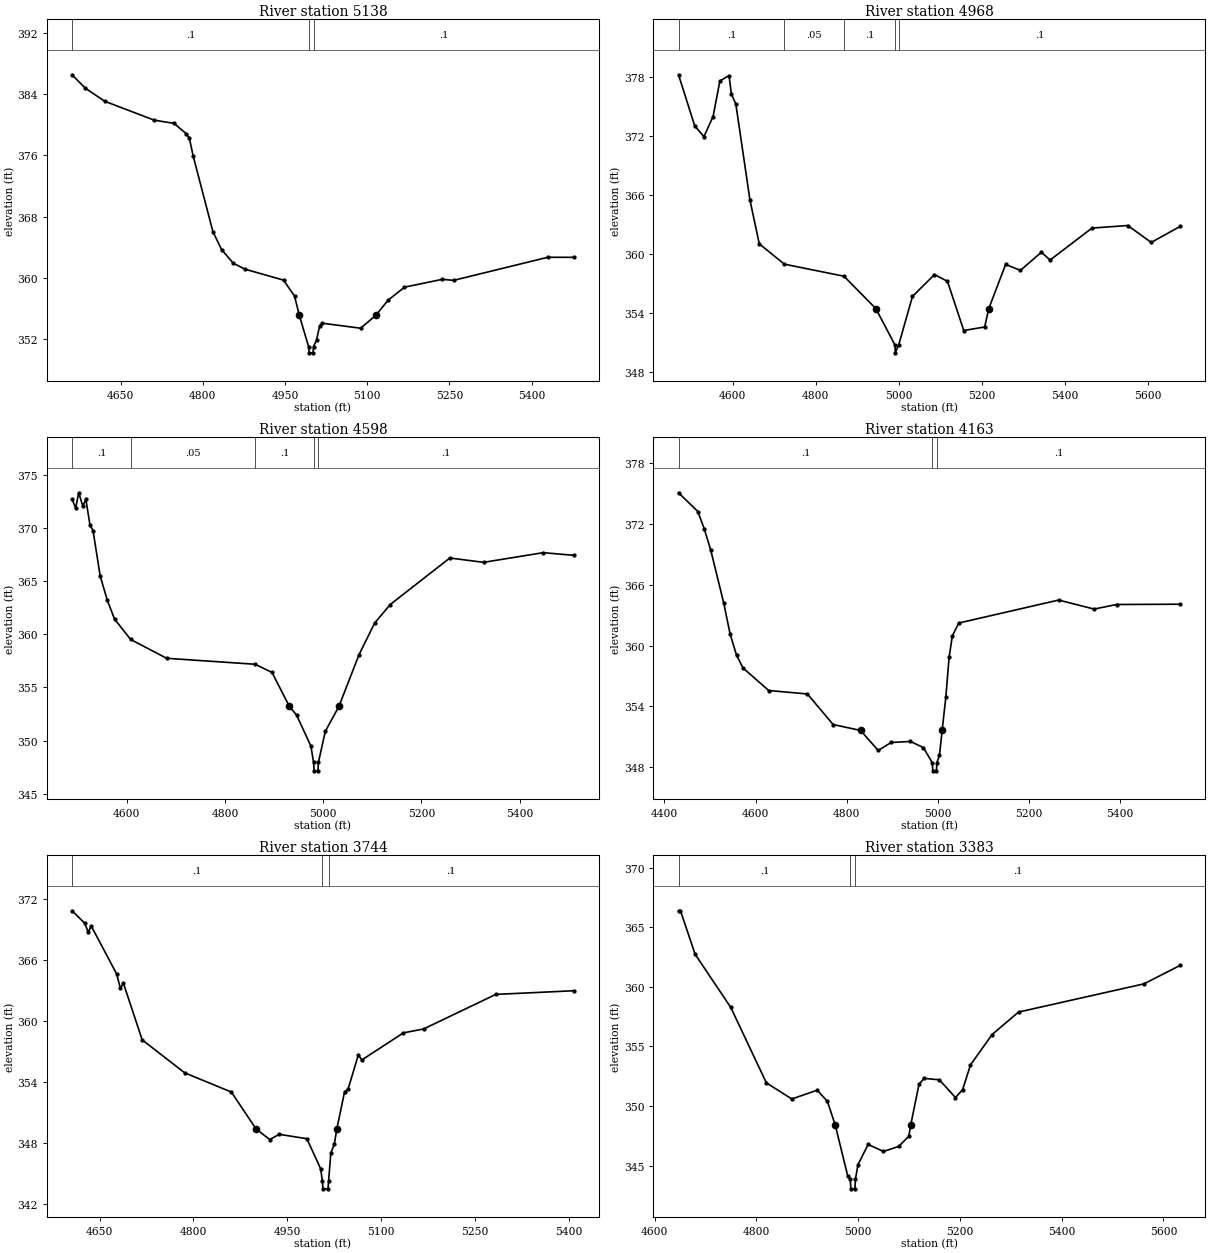
Type RM Length L Ch R = 1 ,5138    ,170,170,170
BEGIN DESCRIPTION:
UNT 050 in RCW 9.0
END DESCRIPTION:
XS GIS Cut Line= 4
      2055235.58     13437987.61      2054950.84     13437820.93
      2054669.59     13437841.76      2054423.06     13438018.85
#Sta/Elev= 30
  4561.5  386.49  4585.3  384.76    4621  383.04  4711.1  380.58  4747.6  380.15
  4769.7  378.81  4775.5  378.23  4782.3  375.94  4818.5  366.03  4834.2  363.71
  4855.7  361.92  4877.2  361.14  4947.4  359.72  4967.5  357.62 4976.12355.1115
  4993.1  351.04  4993.9  350.24  5001.2  350.24    5002  351.04  5007.6  351.94
  5013.4   353.8  5018.4   354.1  5087.8  353.45 5115.46355.1126  5137.9  357.09
    5168   358.8  5236.8  359.82  5257.6  359.69  5429.5   362.7    5477  362.69
#Mann= 3 ,-1 , 0
  4561.5      .1       0  4993.1     .07       0    5002      .1       0
Bank Sta=4976.12,5115.46
XS Rating Curve= 0 ,0
Exp/Cntr=0.3,0.1

Type RM Length L Ch R = 1 ,4968    ,370,370,370
BEGIN DESCRIPTION:
Mapping XS ee7e478e
END DESCRIPTION:
XS GIS Cut Line= 4
      2055247.32     13437836.72      2054919.16     13437664.83
      2054637.91     13437701.28      2054317.58     13438154.43
#Sta/Elev= 30
  4469.5  378.22  4508.6  373.01  4530.7  371.93  4552.7  373.97  4569.1  377.59
  4591.2  378.14  4596.8  376.27  4607.6  375.24  4641.5   365.5    4664  361.03
  4724.4  358.96  4868.2  357.73 4944.83354.4413    4991  350.74  4991.8  349.94
  4999.9  350.74  5033.2  355.68  5086.2   357.9  5117.5  357.21  5156.7  352.21
  5207.1  352.57 5216.97354.4402  5257.6  358.93  5293.3  358.33  5343.8  360.17
  5364.7  359.38  5465.7  362.63  5551.8  362.89  5608.4  361.17  5678.5  362.81
#Mann= 5 ,-1 , 0
  4469.5      .1       0  4724.4     .05       0  4868.2      .1       0
    4991     .07       0  4999.9      .1       0
Bank Sta=4944.83,5216.97
XS Rating Curve= 0 ,0
Exp/Cntr=0.3,0.1

Type RM Length L Ch R = 1 ,4598    ,435,435,435
BEGIN DESCRIPTION:
UNT 050 in RCW 8.0
END DESCRIPTION:
XS GIS Cut Line= 3
        2055175.       13437775.        2054875.       13437375.
      2054379.36     13437210.88
#Sta/Elev= 30
  4488.4  372.71  4495.7  371.86  4501.9   373.3  4510.3  372.05  4516.5  372.69
  4524.9  370.26  4531.1  369.75  4545.7  365.47  4560.3  363.18  4574.9  361.43
  4607.7  359.51  4681.1  357.74  4861.2  357.18  4895.7  356.41 4930.91353.2267
  4945.7   352.4  4974.9  349.49  4980.3  347.96  4981.3  347.16  4989.2  347.16
  4990.2  347.96  5004.2  350.87 5032.02353.2261  5072.9  358.08  5104.6  361.04
  5136.3  362.79  5257.9  367.17  5326.6  366.76  5448.1  367.67  5510.5  367.42
#Mann= 5 ,-1 , 0
  4488.4      .1       0  4607.7     .05       0  4861.2      .1       0
  4980.3     .07       0  4990.2      .1       0
Bank Sta=4930.91,5032.02
XS Rating Curve= 0 ,0
Exp/Cntr=0.3,0.1

Type RM Length L Ch R = 1 ,4163    ,419,419,419
BEGIN DESCRIPTION:
UNT 050 in RCW 7.0
END DESCRIPTION:
XS GIS Cut Line= 3
      2055475.01     13437425.01        2055075.       13437025.
      2054696.52      13436645.6
#Sta/Elev= 30
    4431  375.08  4473.4  373.23  4487.6   371.5  4501.7  369.42    4530  364.24
  4544.2  361.14  4558.3  359.05  4572.4  357.79    4629  355.56  4713.9  355.22
  4770.4   352.2  4830.6351.6198  4869.4  349.64  4897.7  350.43  4940.1  350.53
  4968.4  349.93  4988.2  348.43  4989.2  347.63  4997.2  347.63  4998.1  348.43
  5003.8  349.15  5009.7351.6197  5017.9  354.95    5025  358.84  5032.1  360.95
  5046.2  362.22  5265.4  364.49  5343.2   363.6  5392.7  364.05  5532.6  364.08
#Mann= 3 ,-1 , 0
    4431      .1       0  4988.2     .07       0  4998.1      .1       0
Bank Sta=4830.6,5009.7
XS Rating Curve= 0 ,0
Exp/Cntr=0.3,0.1

Type RM Length L Ch R = 1 ,3744    ,361,361,361
BEGIN DESCRIPTION:
UNT 050 in RCW 6.0
END DESCRIPTION:
XS GIS Cut Line= 3
      2055524.99     13437374.96      2055462.13     13437054.44
      2055239.09      13436634.3
#Sta/Elev= 30
  4605.9  370.88  4626.2  369.65  4631.6  368.79  4636.7  369.37  4677.2  364.65
    4683  363.27  4688.1  363.72    4718  358.16    4786  354.91  4860.6  353.02
  4899.9349.3988  4921.8  348.34  4937.3  348.85  4981.3  348.42  5003.3  345.47
  5006.1  344.28  5007.1  343.48  5015.1  343.48  5016.1  344.28  5019.6  346.99
  5025.3  347.91 5029.27   349.4  5041.6  353.04  5047.2  353.31  5063.6  356.67
  5069.2  356.18  5135.7  358.85  5167.8  359.23  5283.4  362.64  5408.2     363
#Mann= 3 ,-1 , 0
  4605.9      .1       0  5006.1     .07       0  5016.1      .1       0
Bank Sta=4899.9,5029.27
XS Rating Curve= 0 ,0
Exp/Cntr=0.3,0.1

Type RM Length L Ch R = 1 ,3383    ,567,567,567
BEGIN DESCRIPTION:
UNT 050 in RCW 5.0
END DESCRIPTION:
XS GIS Cut Line= 3
       2055696.5     13437387.73      2055699.11     13436848.71
      2055319.45     13436612.07
#Sta/Elev= 30
  4646.8   366.4  4650.6   366.4  4679.5  362.74  4749.5  358.28  4819.5  351.94
  4869.5  350.59  4919.5  351.33  4939.5  350.38 4954.73348.4152  4979.5   344.1
  4984.5  343.84  4985.5  343.04  4993.5  343.04  4994.5  343.84  4999.5  345.07
  5019.5  346.77  5049.5  346.18  5079.5   346.6  5099.5  347.46 5103.28348.4163
  5119.5  351.83  5129.5  352.32  5159.5   352.2  5191.2  350.71  5205.3  351.38
  5220.7  353.45  5263.1     356  5315.1  357.89  5561.7  360.26  5633.2  361.82
#Mann= 3 ,-1 , 0
  4646.8      .1       0  4984.5     .07       0  4994.5      .1       0
Bank Sta=4954.73,5103.28
XS Rating Curve= 0 ,0
Exp/Cntr=0.3,0.1

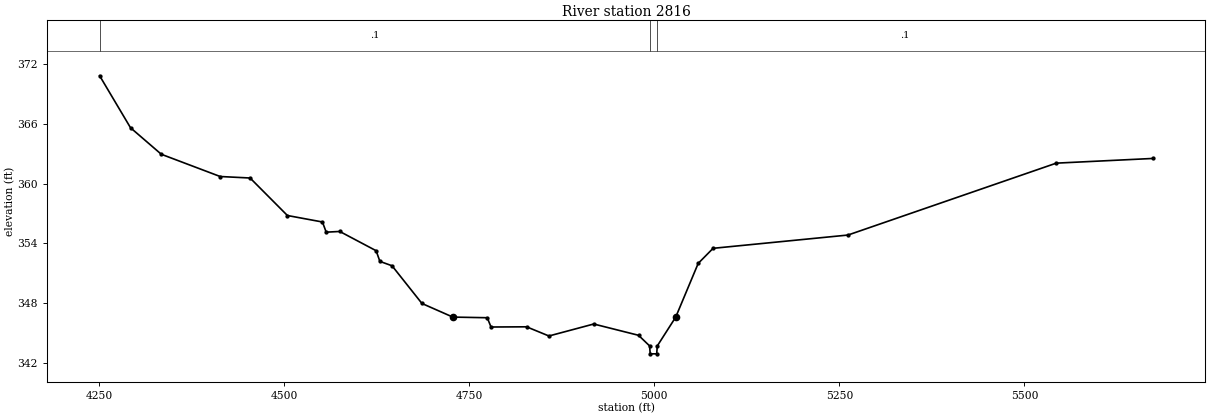
Type RM Length L Ch R = 1 ,2816    ,0,0,0
BEGIN DESCRIPTION:
UNT 050 in RCW 4.0
END DESCRIPTION:
XS GIS Cut Line= 3
      2056566.32     13436710.69      2055932.61     13436624.75
      2055155.67     13436529.26
#Sta/Elev= 30
    4251  370.81  4292.7   365.6  4334.3  362.94  4413.8  360.71  4454.2  360.56
  4504.6   356.8  4551.9  356.15    4557  355.13  4575.3   355.2  4624.4  353.27
  4629.5   352.2  4645.9  351.76  4686.3  347.98 4728.04346.6144  4774.5  346.55
  4779.6  345.62  4827.6  345.64  4857.8  344.72  4918.3  345.92  4978.8  344.79
  4993.7  343.73  4994.6  342.93  5003.3  342.93  5004.2  343.73 5029.05346.6145
  5059.4     352  5079.5  353.51  5261.6  354.84    5543  362.05  5673.3  362.52
#Mann= 3 ,-1 , 0
    4251      .1       0  4993.7     .07       0  5004.2      .1       0
Bank Sta=4728.04,5029.05
XS Rating Curve= 0 ,0
Exp/Cntr=0.3,0.1
LCMann Table=0

Chan Stop Cuts=-1
Use User Specified Reach Order=0
Composite Channel Slope=5