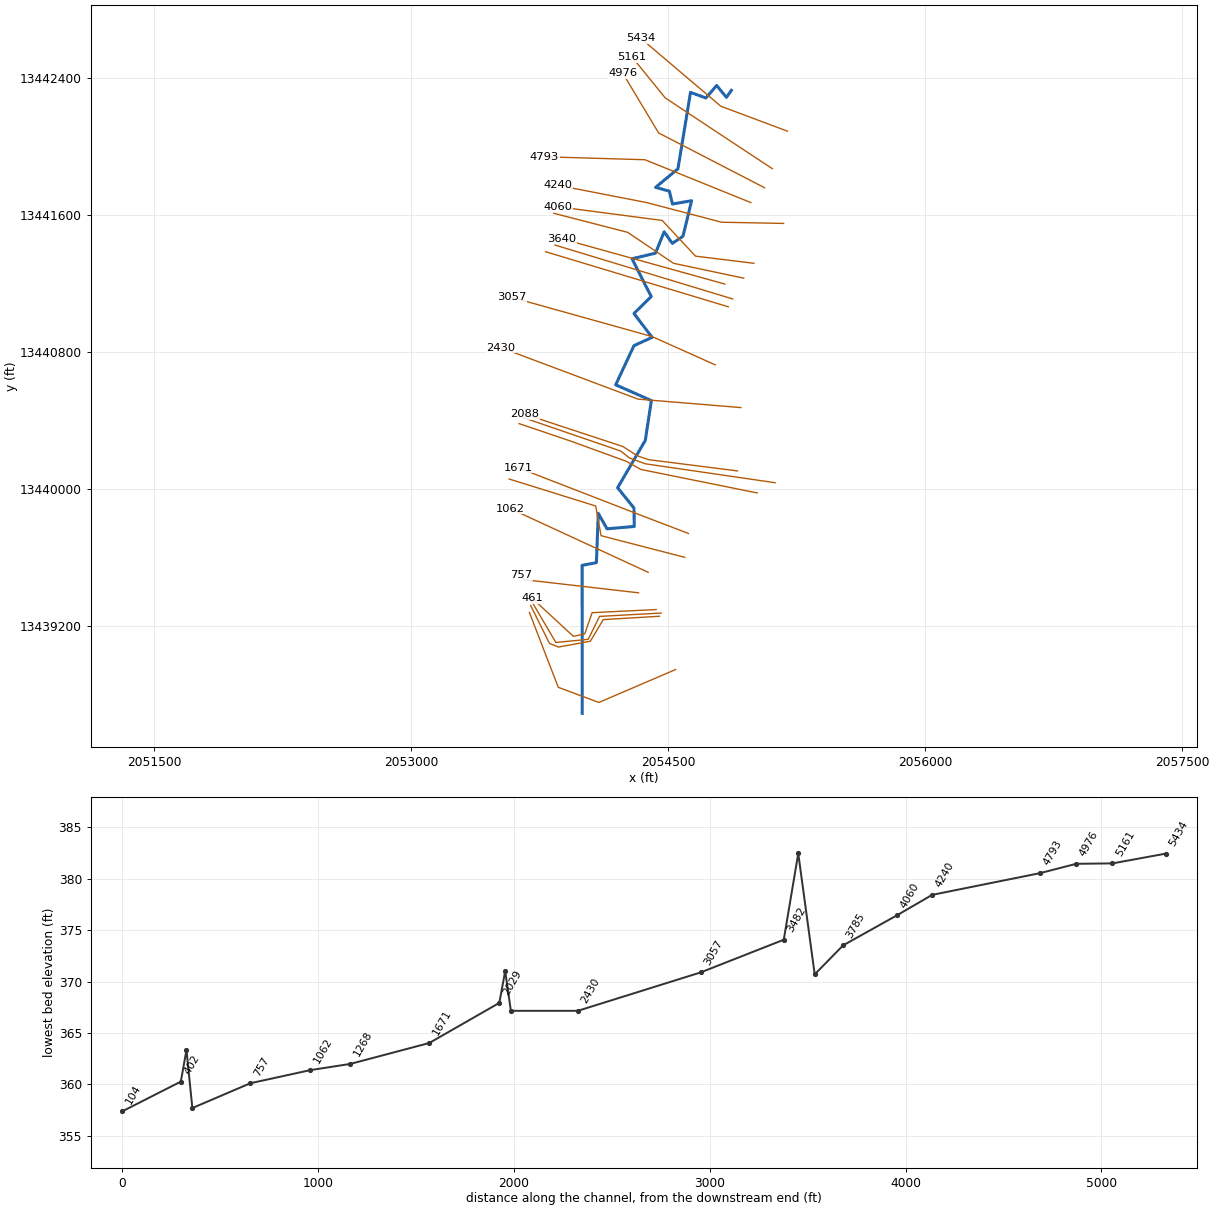
--- UNT 051 in RCW.prj (project) ---

Proj Title=UNT 051 in RCW Base Level Engineering
Current Plan=p01
Default Exp/Contr=0.3,0.1
English Units
Geom File=g01
Flow File=f01
Plan File=p01
BEGIN DESCRIPTION:
UNT 051 in RCW
END DESCRIPTION:

--- UNT 051 in RCW.p01 (plan) ---

Plan Title=Multiple Run
Short Identifier=Multiple
Geom File=g01
Flow File=f01
Subcritical Flow
K Sum by GR= 0
Std Step Tol= 0.01
Critical Tol= 0.01
Num of Std Step Trials= 20
Max Error Tol= 0.3
Flow Tol Ratio= 0.001
Split Flow NTrial= 30
Split Flow Tol= 0.02
Split Flow Ratio= 0.02
Log Output Level= 0
Friction Slope Method= 1
Unsteady Friction Slope Method= 2
Unsteady Bridges Friction Slope Method= 1
Parabolic Critical Depth
Global Vel Dist=  1 , 1 , 1
Global Log Level= 0
CheckData=True
Encroach Param= -1, 0, 0, 0
BEGIN DESCRIPTION:
Multiple Run
END DESCRIPTION:

--- UNT 051 in RCW.f01 (steady flow) ---

Flow Title=Multiple
Number of Profiles=7
Profile Names=10-year,25-year,50-year,1pct_min,100-year,1pct_plu,500-year
River Rch & RM= UNT 051 in RCW,Reach-1,5434
     158     214     259     157     314     626     466
River Rch & RM= UNT 051 in RCW,Reach-1,3640
     235     326     402     247     493     984     754
Boundary for River Rch & Prof#=UNT 051 in RCW,Reach-1,1
Up Type=0
Dn Type=3
Dn Slope=0.005
Boundary for River Rch & Prof#=UNT 051 in RCW,Reach-1,2
Up Type=0
Dn Type=3
Dn Slope=0.005
Boundary for River Rch & Prof#=UNT 051 in RCW,Reach-1,3
Up Type=0
Dn Type=3
Dn Slope=0.005
Boundary for River Rch & Prof#=UNT 051 in RCW,Reach-1,4
Up Type=0
Dn Type=3
Dn Slope=0.005
Boundary for River Rch & Prof#=UNT 051 in RCW,Reach-1,5
Up Type=0
Dn Type=3
Dn Slope=0.005
Boundary for River Rch & Prof#=UNT 051 in RCW,Reach-1,6
Up Type=0
Dn Type=3
Dn Slope=0.005
Boundary for River Rch & Prof#=UNT 051 in RCW,Reach-1,7
Up Type=0
Dn Type=3
Dn Slope=0.005

--- UNT 051 in RCW.g01 (geometry) ---

Geom Title=Existing Conditions

River Reach=UNT 051 in RCW,Reach-1
Reach XY= 30
      2054869.44     13442327.04      2054840.25     13442285.56
      2054783.31     13442355.00      2054720.81     13442282.09
      2054630.80     13442314.54      2054557.61     13441868.89
      2054427.06     13441760.56      2054507.61     13441738.34
      2054525.67     13441663.34      2054637.47     13441682.78
      2054586.78     13441475.14      2054524.97     13441433.47
      2054477.06     13441501.53      2054426.36     13441376.53
      2054289.73     13441343.85      2054401.71     13441123.36
      2054300.80     13441024.54      2054406.92     13440885.51
      2054301.02     13440836.90      2054194.25     13440608.60
      2054402.58     13440516.59      2054366.99     13440283.95
      2054205.53     13440007.91      2054301.02     13439889.85
      2054302.75     13439782.22      2054143.90     13439768.33
      2054092.68     13439858.60      2054081.83     13439570.84
      2053998.50     13439555.22      2053999.32     13438691.55

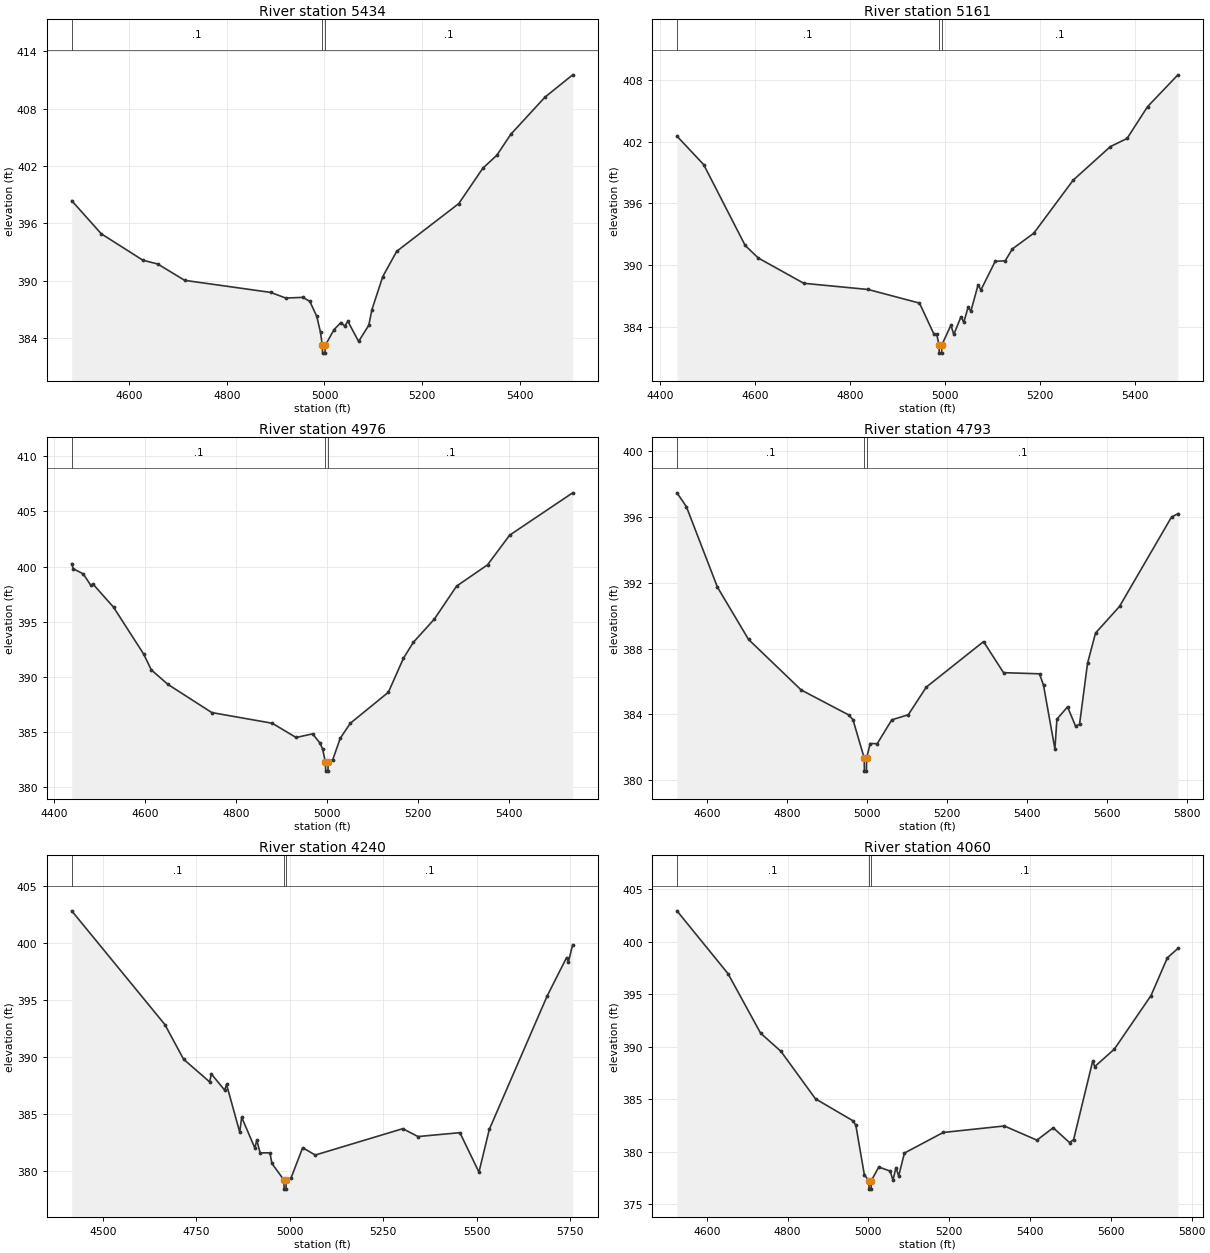
Type RM Length L Ch R = 1,5434,273,273,273
BEGIN DESCRIPTION:
UNT 051 in RCW 6.0
END DESCRIPTION:
XS GIS Cut Line= 3
      2055196.15     13442088.51      2054807.66     13442233.92
      2054340.73     13442629.99
#Sta/Elev= 30
  4481.8  398.38  4542.4  394.92  4627.9  392.15  4658.2  391.76  4713.4  390.05
  4889.8  388.79  4920.6  388.20  4955.8  388.27  4970.0  387.85  4984.3  386.28
  4991.9  384.60  4995.6  383.24  4996.1  382.44  5001.1  382.44  5001.6  383.24
  5019.5  384.89  5033.7  385.64  5041.5  385.27  5048.0  385.77  5070.0  383.66
  5090.9  385.36  5097.4  387.00  5119.5  390.44  5148.0  393.08  5275.4  398.08
  5324.8  401.78  5353.4  403.13  5382.0  405.32  5452.2  409.21  5508.9  411.54
#Mann=3,-1,0
  4481.8     0.1       0  4995.6    0.07       0  5001.6     0.1       0
Bank Sta=4995.6,5001.6
Exp/Cntr=0.3,0.1

Type RM Length L Ch R = 1,5161,185,185,185
BEGIN DESCRIPTION:
Mapping XS 1dc3965e
END DESCRIPTION:
XS GIS Cut Line= 4
      2055108.06     13441869.59      2054760.86     13442098.74
      2054483.08     13442282.77      2054290.26     13442520.36
#Sta/Elev= 30
  4435.8  402.53  4492.2  399.76  4579.5  391.93  4607.2  390.71  4703.0  388.26
  4838.4  387.66  4946.7  386.34  4976.8  383.36  4982.8  383.35  4987.8  382.29
  4988.3  381.49  4993.3  381.49  4993.8  382.29  5012.9  384.20  5018.9  383.30
  5034.0  385.01  5040.0  384.49  5049.0  385.92  5055.0  385.57  5070.1  388.10
  5076.1  387.62  5106.2  390.39  5127.2  390.44  5142.3  391.59  5187.5  393.12
  5270.4  398.26  5348.7  401.51  5383.9  402.30  5427.0  405.38  5491.0  408.47
#Mann=3,-1,0
  4435.8     0.1       0  4987.8    0.07       0  4993.8     0.1       0
Bank Sta=4987.8,4993.8
Exp/Cntr=0.3,0.1

Type RM Length L Ch R = 1,4976,183,183,183
BEGIN DESCRIPTION:
Mapping XS bb7ad0f1
END DESCRIPTION:
XS GIS Cut Line= 3
      2055062.91     13441758.48      2054444.89     13442077.91
      2054236.56     13442425.12
#Sta/Elev= 30
  4438.6  400.26  4441.9  399.80  4464.0  399.33  4480.6  398.29  4486.2  398.37
  4530.5  396.31  4596.9  392.05  4613.4  390.63  4650.1  389.31  4746.3  386.76
  4879.2  385.79  4931.5  384.50  4967.8  384.83  4984.3  383.98  4989.9  383.44
  4996.1  382.25  4996.6  381.45  5001.6  381.45  5002.1  382.25  5012.1  382.49
  5028.6  384.43  5050.7  385.79  5134.3  388.60  5167.5  391.69  5189.2  393.13
  5235.5  395.24  5284.1  398.22  5352.1  400.15  5400.7  402.84  5539.2  406.68
#Mann=3,-1,0
  4438.6     0.1       0  4996.1    0.07       0  5002.1     0.1       0
Bank Sta=4996.1,5002.1
Exp/Cntr=0.3,0.1

Type RM Length L Ch R = 1,4793,553,553,553
BEGIN DESCRIPTION:
Mapping XS aa686cc5
END DESCRIPTION:
XS GIS Cut Line= 3
      2054983.07     13441671.66      2054365.03     13441921.66
      2053779.08     13441938.99
#Sta/Elev= 30
  4524.7  397.48  4548.3  396.64  4626.0  391.74  4703.8  388.56  4835.2  385.49
  4954.1  383.97  4964.9  383.68  4993.1  381.35  4993.6  380.55  4998.6  380.55
  4999.1  381.35  5008.0  382.23  5025.6  382.22  5062.0  383.67  5103.3  383.98
  5148.3  385.66  5291.5  388.43  5341.5  386.54  5431.5  386.47  5441.5  385.77
  5470.0  381.90  5475.0  383.71  5501.6  384.46  5521.6  383.29  5531.6  383.40
  5551.6  387.11  5571.6  388.95  5631.6  390.57  5761.7  396.01  5777.6  396.21
#Mann=3,-1,0
  4524.7     0.1       0  4993.1    0.07       0  4999.1     0.1       0
Bank Sta=4993.1,4999.1
Exp/Cntr=0.3,0.1

Type RM Length L Ch R = 1,4240,180,180,180
BEGIN DESCRIPTION:
Mapping XS 3707bb68
END DESCRIPTION:
XS GIS Cut Line= 4
      2055174.04     13441550.13      2054812.94     13441557.07
      2054375.44     13441671.66      2053859.06     13441772.16
#Sta/Elev= 30
  4416.9  402.83  4666.0  392.86  4716.0  389.82  4785.4  387.84  4790.5  388.52
  4825.8  387.11  4830.9  387.61  4866.2  383.42  4871.3  384.74  4906.6  382.03
  4911.8  382.73  4920.7  381.61  4947.0  381.61  4952.2  380.68  4984.4  379.23
  4984.9  378.43  4989.9  378.43  4990.4  379.23  5003.4  379.41  5034.4  382.06
  5068.2  381.42  5302.1  383.73  5342.8  383.04  5454.9  383.38  5505.8  379.92
  5533.5  383.67  5688.4  395.38  5740.1  398.73  5745.2  398.37  5756.4  399.86
#Mann=3,-1,0
  4416.9     0.1       0  4984.4    0.07       0  4990.4     0.1       0
Bank Sta=4984.4,4990.4
Exp/Cntr=0.3,0.1

Type RM Length L Ch R = 1,4060,275,275,275
BEGIN DESCRIPTION:
Mapping XS 3a239959
END DESCRIPTION:
XS GIS Cut Line= 4
      2055000.49     13441317.49      2054660.17     13441359.16
      2054465.72     13441567.49      2053859.08     13441647.22
#Sta/Elev= 30
  4526.3  402.92  4652.7  396.94  4733.3  391.28  4783.7  389.55  4869.2  385.03
  4961.7  382.95  4969.0  382.52  4990.0  377.82  5001.2  377.24  5001.7  376.44
  5006.7  376.44  5007.2  377.24  5025.7  378.54  5054.0  378.16  5060.9  377.28
  5068.2  378.49  5075.0  377.70  5089.2  379.87  5185.1  381.83  5336.4  382.45
  5417.1  381.10  5457.4  382.28  5497.8  380.87  5507.9  381.15  5555.2  388.63
  5560.2  388.10  5608.7  389.76  5699.5  394.86  5739.9  398.45  5766.0  399.34
#Mann=3,-1,0
  4526.3     0.1       0  5001.2    0.07       0  5007.2     0.1       0
Bank Sta=5001.2,5007.2
Exp/Cntr=0.3,0.1

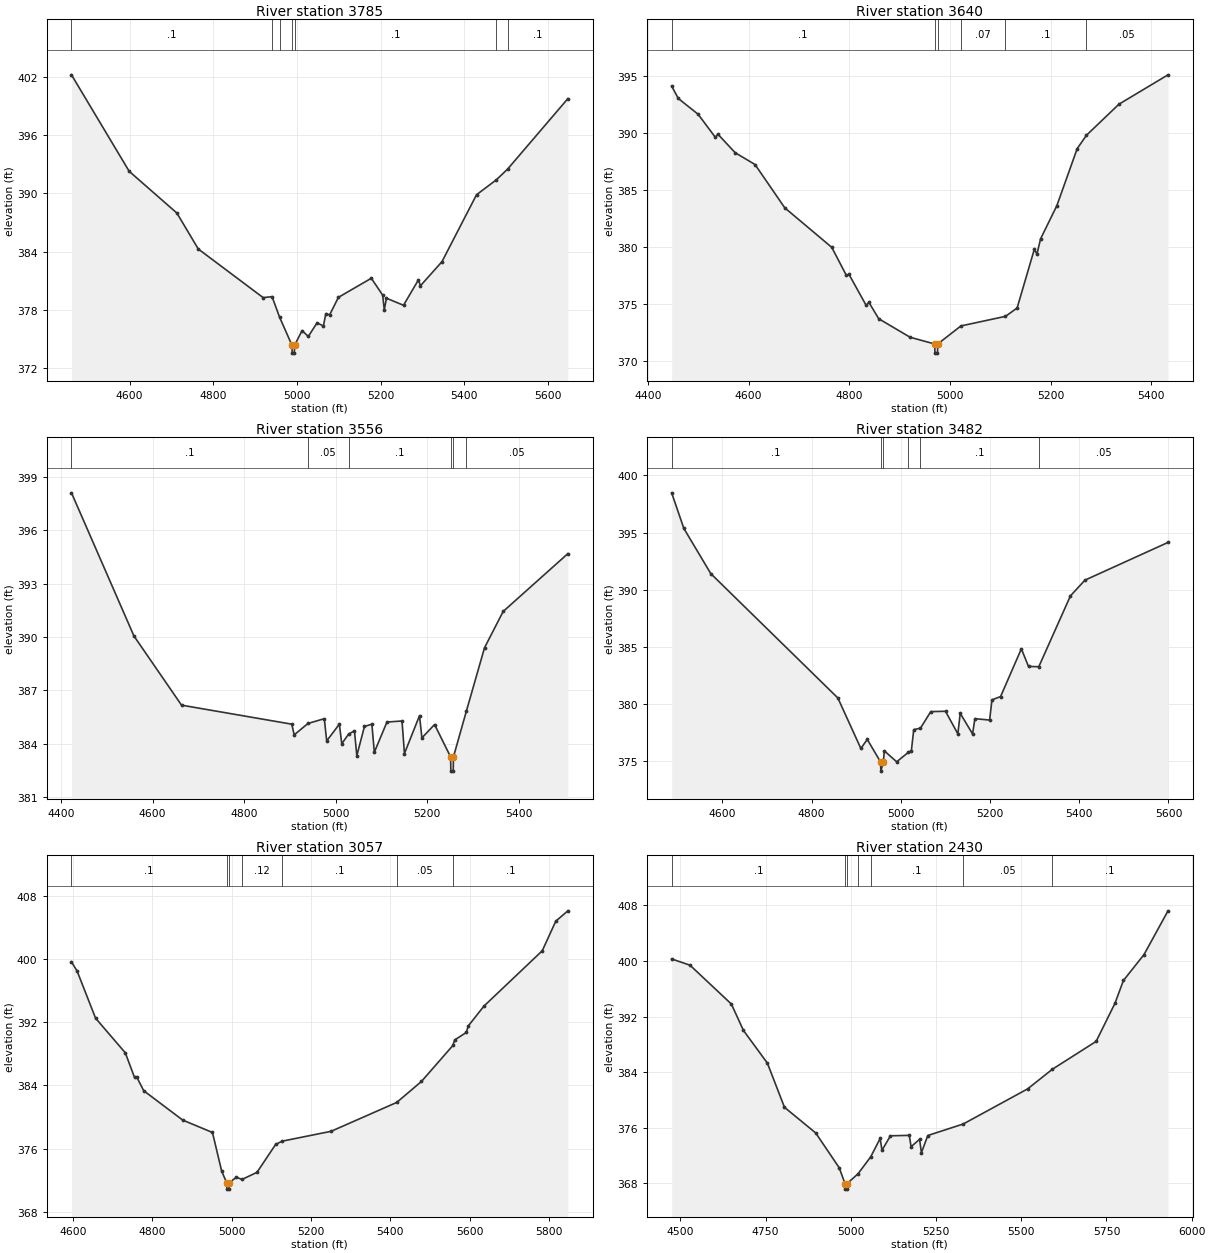
Type RM Length L Ch R = 1,3785,145,145,145
BEGIN DESCRIPTION:
Mapping XS aded1f9e
END DESCRIPTION:
XS GIS Cut Line= 4
      2054941.39     13441230.69      2054531.69     13441317.49
      2054264.33     13441498.05      2053833.74     13441609.17
#Sta/Elev= 30
  4461.2  402.25  4599.1  392.29  4713.1  387.98  4764.2  384.27  4919.2  379.25
  4940.5  379.35  4958.4  377.24  4988.2  374.32  4988.7  373.52  4993.7  373.52
  4994.2  374.32  5012.2  375.85  5027.1  375.24  5048.1  376.65  5063.1  376.32
  5069.1  377.60  5078.1  377.47  5099.1  379.28  5177.7  381.25  5204.8  379.51
  5208.7  377.99  5213.9  379.19  5254.6  378.46  5290.1  381.07  5295.2  380.48
  5346.5  382.96  5429.1  389.87  5476.7  391.42  5503.4  392.52  5647.3  399.79
#Mann=7,-1,0
  4461.2     0.1       0  4940.5    0.16       0  4958.4     0.1       0
  4988.2    0.07       0  4994.2     0.1       0  5476.7    0.05       0
  5503.4     0.1       0
Bank Sta=4988.2,4994.2
Exp/Cntr=0.3,0.1

Type RM Length L Ch R = 1,3640,84,84,84
BEGIN DESCRIPTION:
Mapping XS 515dd47e
END DESCRIPTION:
XS GIS Cut Line= 2
      2054831.57     13441196.17      2053881.09     13441460.32
#Sta/Elev= 30
  4447.0  394.08  4460.2  392.99  4499.6  391.61  4533.8  389.59  4539.0  389.86
  4573.3  388.24  4612.7  387.21  4671.8  383.42  4765.2  379.96  4794.3  377.50
  4799.5  377.59  4833.7  374.87  4838.9  375.15  4858.6  373.71  4920.9  372.09
  4969.8  371.50  4970.3  370.70  4975.3  370.70  4975.8  371.50  5021.9  373.08
  5110.5  373.92  5133.6  374.65  5167.8  379.79  5173.0  379.37  5180.3  380.71
  5212.5  383.60  5253.0  388.60  5271.4  389.77  5336.0  392.49  5433.5  395.06
#Mann=6,-1,0
  4447.0     0.1       0  4969.8    0.07       0  4975.8     0.1       0
  5021.9    0.07       0  5110.5     0.1       0  5271.4    0.05       0
Bank Sta=4969.8,4975.8
Exp/Cntr=0.3,0.1

Type RM Length L Ch R = 1,3556,74,74,74
BEGIN DESCRIPTION:
Mapping XS 98f6d184
END DESCRIPTION:
XS GIS Cut Line= 2
      2054877.14     13441109.37      2053839.91     13441424.01
#Sta/Elev= 30
  4423.0  398.11  4559.4  390.06  4663.3  386.17  4904.1  385.10  4909.3  384.50
  4939.5  385.14  4975.1  385.41  4980.3  384.16  5008.0  385.10  5013.2  384.00
  5028.1  384.54  5040.9  384.73  5046.1  383.33  5062.7  384.97  5079.0  385.10
  5084.3  383.52  5111.9  385.22  5144.8  385.28  5150.1  383.45  5183.0  385.58
  5188.2  384.33  5215.9  385.08  5250.9  383.26  5251.4  382.46  5256.6  382.46
  5257.1  383.26  5285.4  385.84  5325.0  389.40  5365.7  391.44  5506.9  394.69
#Mann=6,-1,0
  4423.0     0.1       0  4939.5    0.05       0  5028.1     0.1       0
  5250.9   0.033       0  5257.1     0.1       0  5285.4    0.05       0
Bank Sta=5250.9,5257.1
Exp/Cntr=0.3,0.1

Type RM Length L Ch R = 1,3482,425,425,425
BEGIN DESCRIPTION:
Mapping XS b8d940d9
END DESCRIPTION:
XS GIS Cut Line= 2
      2054851.10     13441063.79      2053785.56     13441384.98
#Sta/Elev= 30
  4486.1  398.48  4513.4  395.36  4573.9  391.39  4858.7  380.49  4910.3  376.06
  4924.7  376.85  4954.6  374.87  4955.1  374.07  4960.8  374.87  4962.9  375.85
  4990.6  374.89  5016.6  375.71  5023.6  375.87  5028.9  377.71  5044.0  377.84
  5067.1  379.29  5100.1  379.32  5127.8  377.34  5133.1  379.14  5160.8  377.33
  5166.0  378.67  5199.0  378.55  5204.3  380.32  5223.6  380.61  5270.2  384.80
  5286.2  383.25  5309.3  383.23  5380.2  389.44  5412.7  390.82  5599.0  394.13
#Mann=6,-1,0
  4486.1     0.1       0  4954.6    0.07       0  4960.8     0.1       0
  5016.6    0.05       0  5044.0     0.1       0  5309.3    0.05       0
Bank Sta=4954.6,4960.8
Exp/Cntr=0.3,0.1

Type RM Length L Ch R = 1,3057,627,627,627
BEGIN DESCRIPTION:
UNT 051 in RCW 5.0
END DESCRIPTION:
XS GIS Cut Line= 3
      2054774.96     13440725.02      2054406.26     13440890.17
      2053590.28     13441118.04
#Sta/Elev= 30
  4596.5  399.62  4610.8  398.44  4657.2  392.50  4732.2  388.12  4755.4  385.01
  4760.9  385.07  4778.6  383.33  4876.8  379.62  4951.9  378.05  4975.1  373.16
  4987.8  371.69  4988.3  370.89  4993.5  370.89  4994.0  371.69  5012.2  372.40
  5026.1  372.11  5064.1  373.01  5111.1  376.54  5127.3  376.95  5251.0  378.20
  5416.4  381.85  5478.7  384.50  5557.9  389.05  5562.6  389.75  5591.6  390.69
  5596.8  391.52  5636.1  394.02  5783.2  401.02  5817.3  404.76  5847.7  406.07
#Mann=7,-1,0
  4596.5     0.1       0  4987.8    0.07       0  4994.0     0.1       0
  5026.1    0.12       0  5127.3     0.1       0  5416.4    0.05       0
  5557.9     0.1       0
Bank Sta=4987.8,4994
Exp/Cntr=0.3,0.1

Type RM Length L Ch R = 1,2430,342,342,342
BEGIN DESCRIPTION:
UNT 051 in RCW 4.0
END DESCRIPTION:
XS GIS Cut Line= 3
      2054924.92     13440475.68      2054325.00     13440525.00
      2053525.04     13440824.99
#Sta/Elev= 30
  4474.3  400.30  4528.2  399.40  4649.5  393.81  4684.9  390.01  4755.2  385.30
  4805.3  378.94  4896.9  375.25  4965.9  370.24  4982.8  367.96  4983.3  367.16
  4988.5  367.16  4989.0  367.96  5021.0  369.36  5058.3  371.81  5086.0  374.45
  5091.4  372.76  5116.3  374.84  5171.5  374.90  5176.8  373.27  5201.7  374.33
  5207.1  372.41  5225.8  374.88  5329.9  376.54  5518.6  381.59  5591.6  384.43
  5719.7  388.43  5774.9  393.91  5799.8  397.20  5860.3  400.94  5930.6  407.23
#Mann=7,-1,0
  4474.3     0.1       0  4982.8    0.07       0  4989.0     0.1       0
  5021.0    0.07       0  5058.3     0.1       0  5329.9    0.05       0
  5591.6     0.1       0
Bank Sta=4982.8,4989
Exp/Cntr=0.3,0.1

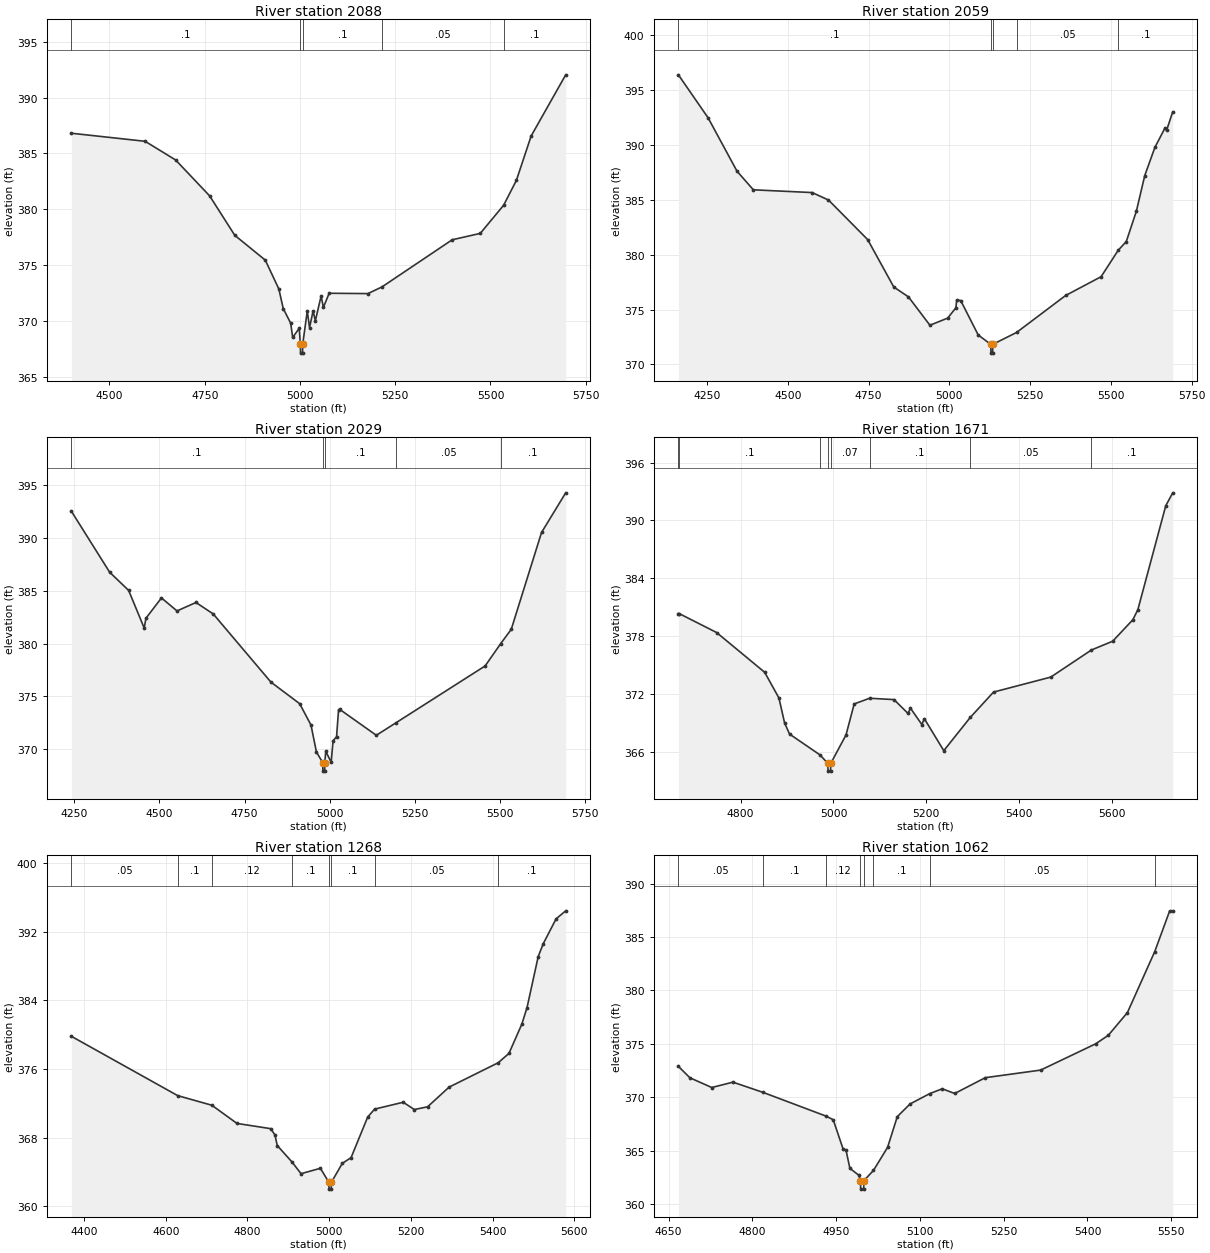
Type RM Length L Ch R = 1,2088,29,29,29
BEGIN DESCRIPTION:
Mapping XS aa682933
END DESCRIPTION:
XS GIS Cut Line= 5
      2054905.07     13440106.09      2054384.27     13440172.05
      2054320.04     13440194.62      2054236.71     13440248.44
      2053662.01     13440437.69
#Sta/Elev= 30
  4400.1  386.81  4593.6  386.09  4673.7  384.42  4763.0  381.21  4828.9  377.69
  4909.0  375.47  4944.6  372.89  4956.1  371.14  4975.6  369.84  4980.9  368.56
  4998.1  369.38  5001.0  367.96  5001.5  367.16  5006.7  367.16  5007.2  367.96
  5019.2  370.92  5025.2  369.44  5034.4  370.93  5040.4  370.06  5055.5  372.26
  5061.5  371.25  5076.6  372.51  5178.4  372.48  5215.4  373.08  5399.5  377.29
  5473.2  377.86  5534.4  380.37  5567.9  382.59  5606.8  386.57  5697.4  392.03
#Mann=5,-1,0
  4400.1     0.1       0  5001.0    0.07       0  5007.2     0.1       0
  5215.4    0.05       0  5534.4     0.1       0
Bank Sta=5001,5007.2
Exp/Cntr=0.3,0.1

Type RM Length L Ch R = 1,2059,30,30,30
BEGIN DESCRIPTION:
UNT 051 in RCW 3.0
END DESCRIPTION:
XS GIS Cut Line= 5
      2055124.60     13440037.30      2054366.91     13440147.75
      2054274.97     13440181.62      2054222.82     13440222.40
      2053655.37     13440417.09
#Sta/Elev= 30
  4161.6  396.37  4253.4  392.46  4343.1  387.59  4393.6  385.90  4575.5  385.65
  4626.1  384.97  4747.3  381.37  4828.2  377.05  4873.6  376.15  4940.0  373.57
  4995.1  374.22  5020.3  375.16  5022.9  375.86  5035.2  375.82  5089.5  372.68
  5128.4  371.83  5128.9  371.03  5134.1  371.03  5134.6  371.83  5208.1  372.91
  5360.1  376.28  5469.8  377.99  5522.8  380.40  5547.7  381.19  5578.9  383.95
  5604.9  387.20  5636.2  389.76  5667.5  391.53  5672.7  391.34  5691.4  393.00
#Mann=5,-1,0
  4161.6     0.1       0  5128.4    0.07       0  5134.6     0.1       0
  5208.1    0.05       0  5522.8     0.1       0
Bank Sta=5128.4,5134.6
Exp/Cntr=0.3,0.1

Type RM Length L Ch R = 1,2029,358,358,358
BEGIN DESCRIPTION:
Mapping XS 91db852a
END DESCRIPTION:
XS GIS Cut Line= 5
      2055019.69     13439977.61      2054340.87     13440114.76
      2054257.54     13440161.64      2053938.09     13440277.96
      2053630.78     13440382.13
#Sta/Elev= 30
  4241.1  392.51  4353.6  386.74  4409.4  385.02  4455.1  381.46  4460.2  382.39
  4505.8  384.31  4551.5  383.08  4607.3  383.88  4658.1  382.79  4827.4  376.35
  4911.9  374.31  4945.2  372.29  4961.2  369.74  4979.7  368.73  4980.2  367.93
  4985.4  367.93  4985.9  368.73  4988.6  369.81  5004.5  368.77  5010.2  370.80
  5020.4  371.19  5026.2  373.72  5029.2  373.78  5137.2  371.32  5195.8  372.52
  5457.0  377.88  5502.9  380.00  5533.7  381.34  5622.7  390.50  5693.7  394.25
#Mann=5,-1,0
  4241.1     0.1       0  4979.7    0.07       0  4985.9     0.1       0
  5195.8    0.05       0  5502.9     0.1       0
Bank Sta=4979.7,4985.9
Exp/Cntr=0.3,0.1

Type RM Length L Ch R = 1,1671,403,403,403
BEGIN DESCRIPTION:
UNT 051 in RCW 2.0
END DESCRIPTION:
XS GIS Cut Line= 3
      2054618.70     13439741.31      2054351.79     13439843.30
      2053625.00     13440125.00
#Sta/Elev= 30
  4665.9  380.35  4667.6  380.35  4748.2  378.39  4851.8  374.27  4882.5  371.61
  4894.7  369.03  4905.4  367.87  4971.3  365.70  4987.9  364.83  4988.4  364.03
  4993.7  364.03  4994.2  364.83  5027.1  367.78  5044.7  370.99  5078.0  371.58
  5130.5  371.44  5160.6  370.01  5166.0  370.55  5190.5  368.86  5195.9  369.46
  5237.8  366.15  5294.8  369.59  5345.0  372.22  5468.3  373.77  5556.0  376.58
  5601.8  377.49  5645.3  379.72  5656.0  380.76  5716.1  391.52  5731.1  392.86
#Mann=8,-1,0
  4665.9    0.05       0  4667.6     0.1       0  4971.3    0.07       0
  4987.9    0.07       0  4994.2    0.07       0  5078.0     0.1       0
  5294.8    0.05       0  5556.0     0.1       0
Bank Sta=4987.9,4994.2
Exp/Cntr=0.3,0.1

Type RM Length L Ch R = 1,1268,206,206,206
BEGIN DESCRIPTION:
Mapping XS 57a50b3d
END DESCRIPTION:
XS GIS Cut Line= 4
      2054597.26     13439601.97      2054108.95     13439728.28
      2054077.70     13439901.46      2053572.45     13440059.02
#Sta/Elev= 30
  4369.1  379.82  4629.3  372.90  4712.9  371.78  4774.3  369.66  4856.9  369.05
  4867.2  368.32  4872.9  367.08  4908.7  365.18  4931.1  363.80  4978.5  364.43
  4999.1  362.80  4999.6  362.00  5004.9  362.00  5005.4  362.80  5032.1  365.01
  5053.5  365.67  5094.2  370.41  5111.2  371.33  5181.1  372.13  5208.3  371.28
  5240.8  371.60  5293.2  373.89  5413.7  376.74  5439.9  377.83  5471.3  381.23
  5484.1  383.17  5511.4  389.11  5523.7  390.61  5555.1  393.51  5578.7  394.45
#Mann=8,-1,0
  4369.1    0.05       0  4629.3     0.1       0  4712.9    0.12       0
  4908.7     0.1       0  4999.1    0.07       0  5005.4     0.1       0
  5111.2    0.05       0  5413.7     0.1       0
Bank Sta=4999.1,5005.4
Exp/Cntr=0.3,0.1

Type RM Length L Ch R = 1,1062,305,305,305
BEGIN DESCRIPTION:
Mapping XS cbc061f3
END DESCRIPTION:
XS GIS Cut Line= 2
      2054383.72     13439514.72      2053580.29     13439885.84
#Sta/Elev= 30
  4667.6  372.89  4688.2  371.82  4727.3  370.91  4765.3  371.41  4818.7  370.46
  4931.9  368.23  4944.8  367.89  4962.2  365.19  4967.7  365.04  4974.6  363.34
  4990.7  362.69  4993.5  362.19  4994.0  361.39  4999.3  361.39  4999.8  362.19
  5016.8  363.14  5042.1  365.30  5059.5  368.18  5082.4  369.37  5117.3  370.33
  5139.9  370.79  5162.3  370.35  5217.0  371.83  5316.1  372.54  5414.6  375.00
  5437.3  375.80  5471.5  377.93  5520.4  383.64  5547.2  387.46  5552.6  387.46
#Mann=8,-1,0
  4667.6    0.05       0  4818.7     0.1       0  4931.9    0.12       0
  4993.5    0.07       0  4999.8    0.12       0  5016.8     0.1       0
  5117.3    0.05       0  5520.4     0.1       0
Bank Sta=4993.5,4999.8
Exp/Cntr=0.3,0.1

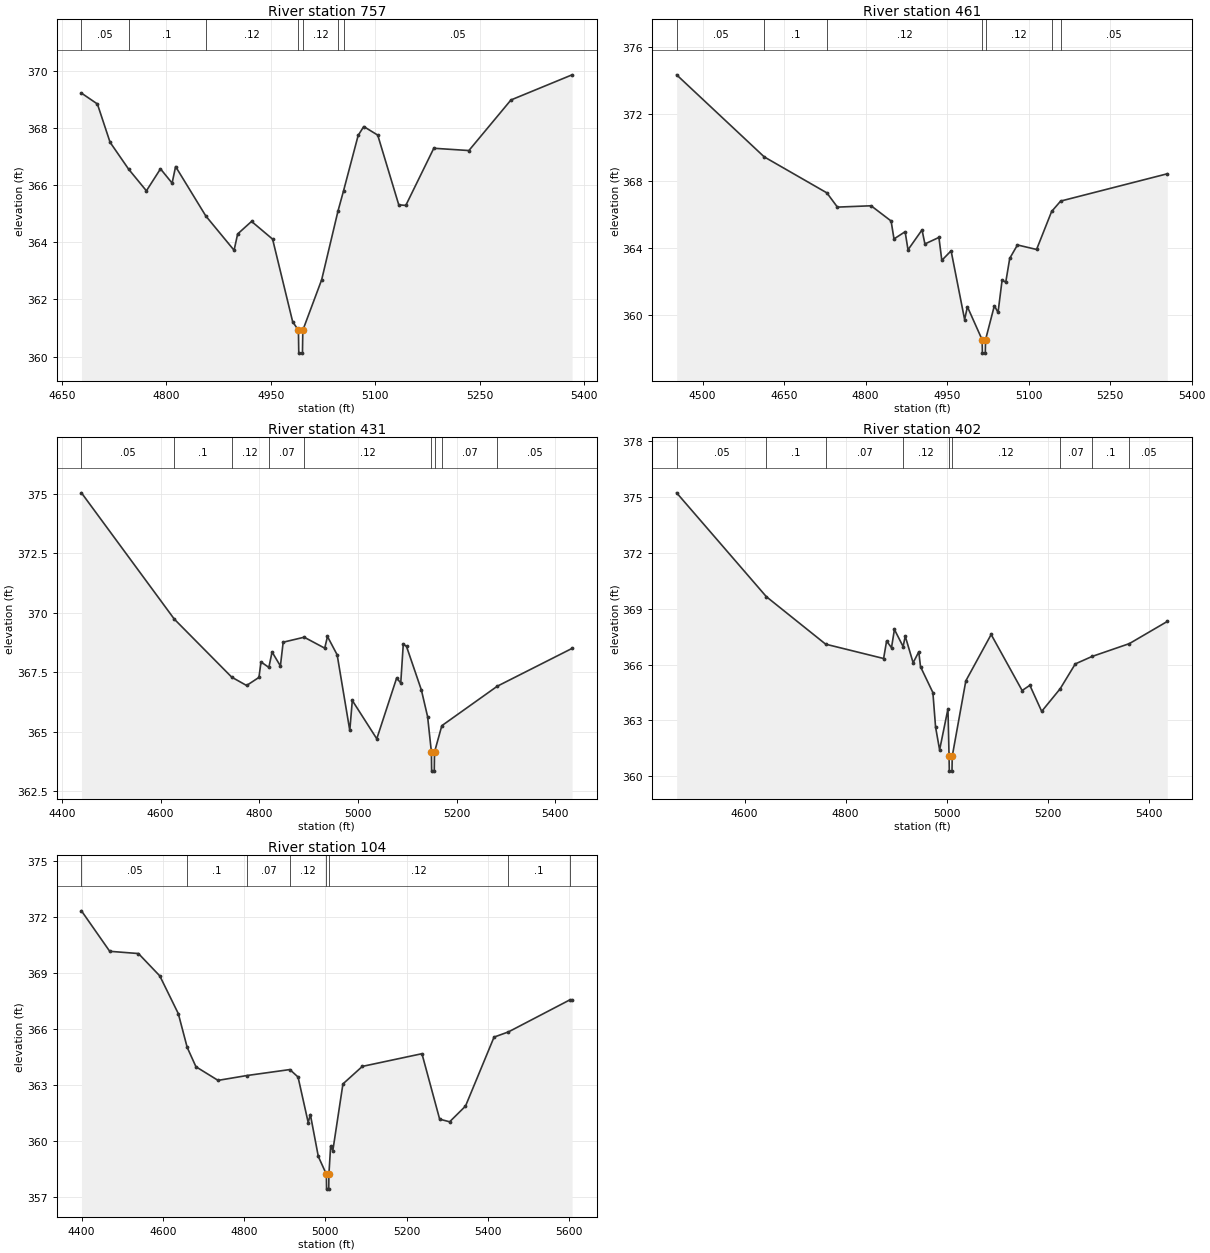
Type RM Length L Ch R = 1,757,296,296,296
BEGIN DESCRIPTION:
Mapping XS 36338c38
END DESCRIPTION:
XS GIS Cut Line= 3
      2054327.73     13439394.94      2053659.73     13439471.77
      2053642.79     13439499.14
#Sta/Elev= 30
  4678.1  369.22  4701.0  368.84  4719.2  367.50  4745.8  366.56  4771.4  365.80
  4791.6  366.57  4808.3  366.07  4813.3  366.65  4856.7  364.92  4897.3  363.72
  4902.4  364.29  4922.4  364.73  4952.6  364.11  4981.4  361.22  4989.7  360.92
  4990.2  360.12  4995.5  360.12  4996.0  360.92  5023.1  362.69  5046.5  365.09
  5054.6  365.81  5075.5  367.74  5083.5  368.05  5103.6  367.75  5133.8  365.31
  5143.9  365.29  5184.1  367.29  5234.5  367.21  5294.9  368.98  5382.7  369.86
#Mann=7,-1,0
  4678.1    0.05       0  4745.8     0.1       0  4856.7    0.12       0
  4989.7    0.07       0  4996.0    0.12       0  5046.5     0.1       0
  5054.6    0.05       0
Bank Sta=4989.7,4996
Exp/Cntr=0.3,0.1

Type RM Length L Ch R = 1,461,30,30,30
BEGIN DESCRIPTION:
Mapping XS ddbf5507
END DESCRIPTION:
XS GIS Cut Line= 5
      2054430.53     13439297.29      2054056.87     13439279.06
      2054013.90     13439155.36      2053947.49     13439141.04
      2053705.27     13439365.03
#Sta/Elev= 30
  4452.2  374.33  4613.4  369.43  4728.7  367.28  4748.1  366.43  4810.1  366.51
  4846.9  365.60  4852.2  364.53  4872.7  364.96  4878.0  363.88  4903.8  365.07
  4909.1  364.23  4934.9  364.62  4940.2  363.25  4957.3  363.82  4982.2  359.71
  4987.3  360.48  5014.4  358.51  5014.9  357.71  5020.2  357.71  5020.7  358.51
  5036.9  360.54  5043.7  360.14  5051.1  362.06  5057.9  361.95  5065.2  363.37
  5079.4  364.17  5114.6  363.90  5142.3  366.17  5158.9  366.79  5355.1  368.42
#Mann=7,-1,0
  4452.2    0.05       0  4613.4     0.1       0  4728.7    0.12       0
  5014.4    0.07       0  5020.7    0.12       0  5142.3    0.07       0
  5158.9    0.05       0
Bank Sta=5014.4,5020.7
Exp/Cntr=0.3,0.1

Type RM Length L Ch R = 1,431,29,29,29
BEGIN DESCRIPTION:
Mapping XS 19e973e2
END DESCRIPTION:
XS GIS Cut Line= 5
      2054459.25     13439276.89      2054100.05     13439257.36
      2054033.92     13439123.32      2053845.06     13439105.45
      2053695.48     13439360.18
#Sta/Elev= 30
  4439.7  375.05  4627.9  369.74  4744.3  367.30  4774.4  366.95  4799.4  367.29
  4803.6  367.94  4819.5  367.71  4826.0  368.36  4842.9  367.77  4848.5  368.77
  4891.1  368.98  4932.7  368.52  4938.3  369.01  4957.9  368.24  4983.5  365.06
  4988.6  366.32  5038.2  364.71  5078.4  367.26  5086.8  367.06  5091.9  368.69
  5098.5  368.59  5128.6  366.76  5141.2  365.64  5148.9  364.15  5149.4  363.35
  5154.7  363.35  5155.2  364.15  5170.0  365.26  5282.4  366.92  5434.0  368.51
#Mann=9,-1,0
  4439.7    0.05       0  4627.9     0.1       0  4744.3    0.12       0
  4819.5    0.07       0  4891.1    0.12       0  5148.9    0.07       0
  5155.2    0.12       0  5170.0    0.07       0  5282.4    0.05       0
Bank Sta=5148.9,5155.2
Exp/Cntr=0.3,0.1

Type RM Length L Ch R = 1,402,298,298,298
BEGIN DESCRIPTION:
Mapping XS 12f17357
END DESCRIPTION:
XS GIS Cut Line= 6
      2054450.12     13439258.23      2054121.97     13439238.70
      2054046.45     13439112.39      2053860.25     13439078.54
      2053808.17     13439099.37      2053697.99     13439321.04
#Sta/Elev= 30
  4465.6  375.23  4643.2  369.65  4760.5  367.10  4875.2  366.33  4881.1  367.27
  4890.8  366.91  4896.6  367.89  4913.8  366.97  4918.0  367.53  4933.6  366.10
  4944.8  366.69  4948.2  365.89  4972.7  364.50  4978.0  362.65  4986.0  361.42
  5002.5  363.62  5004.7  361.08  5005.2  360.28  5010.5  360.28  5011.0  361.08
  5037.9  365.13  5088.0  367.62  5149.3  364.61  5164.6  364.89  5188.0  363.49
  5224.7  364.71  5254.5  366.04  5287.7  366.44  5361.5  367.13  5436.5  368.32
#Mann=9,-1,0
  4465.6    0.05       0  4643.2     0.1       0  4760.5    0.07       0
  4913.8    0.12       0  5004.7    0.07       0  5011.0    0.12       0
  5224.7    0.07       0  5287.7     0.1       0  5361.5    0.05       0
Bank Sta=5004.7,5011
Exp/Cntr=0.3,0.1

Type RM Length L Ch R = 1,104,0,0,0
BEGIN DESCRIPTION:
UNT 051 in RCW 1.0
END DESCRIPTION:
XS GIS Cut Line= 4
      2054544.04     13438947.45      2054096.15     13438755.19
      2053859.17     13438843.73      2053691.20     13439279.92
#Sta/Elev= 30
  4399.6  372.32  4469.2  370.15  4539.9  370.03  4592.5  368.83  4638.0  366.81
  4659.9  365.00  4681.5  363.96  4735.9  363.23  4806.9  363.49  4912.6  363.81
  4932.8  363.41  4957.8  360.97  4963.1  361.40  4982.7  359.15  5002.5  358.20
  5003.0  357.40  5008.3  357.40  5008.8  358.20  5013.0  359.70  5018.4  359.46
  5043.3  363.04  5091.1  363.98  5237.8  364.66  5281.4  361.15  5306.0  361.01
  5345.0  361.85  5415.3  365.55  5450.8  365.83  5602.2  367.55  5607.4  367.55
#Mann=8,-1,0
  4399.6    0.05       0  4659.9     0.1       0  4806.9    0.07       0
  4912.6    0.12       0  5002.5    0.07       0  5008.8    0.12       0
  5450.8     0.1       0  5602.2    0.05       0
Bank Sta=5002.5,5008.8
Exp/Cntr=0.3,0.1

Chan Stop Cuts=-1