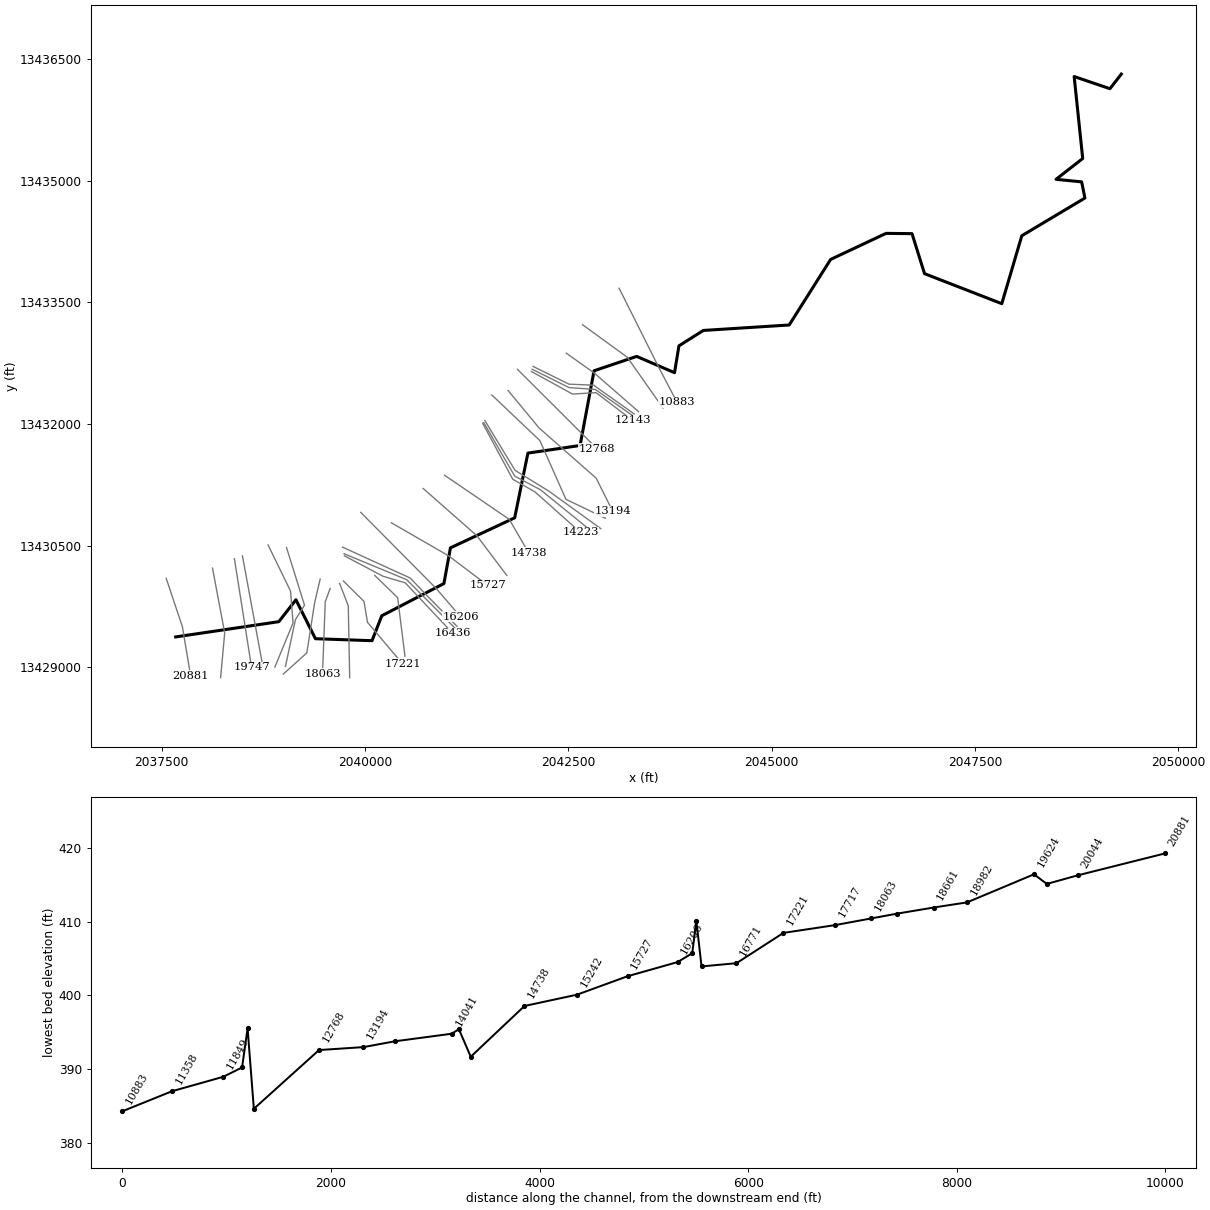
--- UNT 052 in RCW.prj (project) ---

Proj Title=UNT 052 in RCW Base Level Engineering
Current Plan=p01
Default Exp/Contr=0.3,0.1
English Units
Geom File=g01
Flow File=f01
Plan File=p01
BEGIN DESCRIPTION:
UNT 052 in RCW
END DESCRIPTION:

--- UNT 052 in RCW.p01 (plan) ---

Plan Title=Multiple Run
Short Identifier=Multiple
Geom File=g01
Flow File=f01
Subcritical Flow
K Sum by GR= 0
Std Step Tol= 0.01
Critical Tol= 0.01
Num of Std Step Trials= 20
Max Error Tol= 0.3
Flow Tol Ratio= 0.001
Split Flow NTrial= 30
Split Flow Tol= 0.02
Split Flow Ratio= 0.02
Log Output Level= 0
Friction Slope Method= 1
Unsteady Friction Slope Method= 2
Unsteady Bridges Friction Slope Method= 1
Parabolic Critical Depth
Global Vel Dist=  1 , 1 , 1
Global Log Level= 0
CheckData=True
Encroach Param= -1, 0, 0, 0
BEGIN DESCRIPTION:
Multiple Run
END DESCRIPTION:

--- UNT 052 in RCW.f01 (steady flow) ---

Flow Title=Multiple
Number of Profiles=7
Profile Names=10-year,25-year,50-year,1pct_min,100-year,1pct_plu,500-year
River Rch & RM= UNT 052 in RCW,Reach-1,20881
     172     235     286     174     347     693     521
River Rch & RM= UNT 052 in RCW,Reach-1,20044
     223     308     378     231     461     920     697
River Rch & RM= UNT 052 in RCW,Reach-1,14223
     322     453     563     349     696    1388    1079
River Rch & RM= UNT 052 in RCW,Reach-1,8104
     344     484     600     371     740    1476    1142
Boundary for River Rch & Prof#=UNT 052 in RCW,Reach-1,1
Up Type=0
Dn Type=3
Dn Slope=0.005
Boundary for River Rch & Prof#=UNT 052 in RCW,Reach-1,2
Up Type=0
Dn Type=3
Dn Slope=0.005
Boundary for River Rch & Prof#=UNT 052 in RCW,Reach-1,3
Up Type=0
Dn Type=3
Dn Slope=0.005
Boundary for River Rch & Prof#=UNT 052 in RCW,Reach-1,4
Up Type=0
Dn Type=3
Dn Slope=0.005
Boundary for River Rch & Prof#=UNT 052 in RCW,Reach-1,5
Up Type=0
Dn Type=3
Dn Slope=0.005
Boundary for River Rch & Prof#=UNT 052 in RCW,Reach-1,6
Up Type=0
Dn Type=3
Dn Slope=0.005
Boundary for River Rch & Prof#=UNT 052 in RCW,Reach-1,7
Up Type=0
Dn Type=3
Dn Slope=0.005

--- UNT 052 in RCW.g01 (geometry) ---

Geom Title=Existing Conditions

River Reach=UNT 052 in RCW,Reach-1
Reach XY= 30
      2037672.02     13429376.56      2038940.80     13429564.54
      2039150.80     13429834.54      2039390.80     13429354.54
      2040086.89     13429330.12      2040206.68     13429637.41
      2040970.80     13430034.54      2041050.80     13430474.54
      2041840.80     13430844.54      2042003.56     13431642.62
      2042645.05     13431736.37      2042816.92     13432657.38
      2043340.80     13432834.54      2043806.51     13432633.94
      2043860.80     13432964.54      2044160.80     13433154.54
      2045216.66     13433221.83      2045726.21     13434029.99
      2046407.64     13434351.17      2046727.08     13434347.70
      2046880.80     13433854.54      2047830.80     13433484.54
      2048077.17     13434322.09      2048853.21     13434786.93
      2048812.84     13434986.15      2048497.74     13435017.40
      2048825.86     13435273.91      2048720.80     13436284.54
      2049160.80     13436134.54      2049300.80     13436314.54

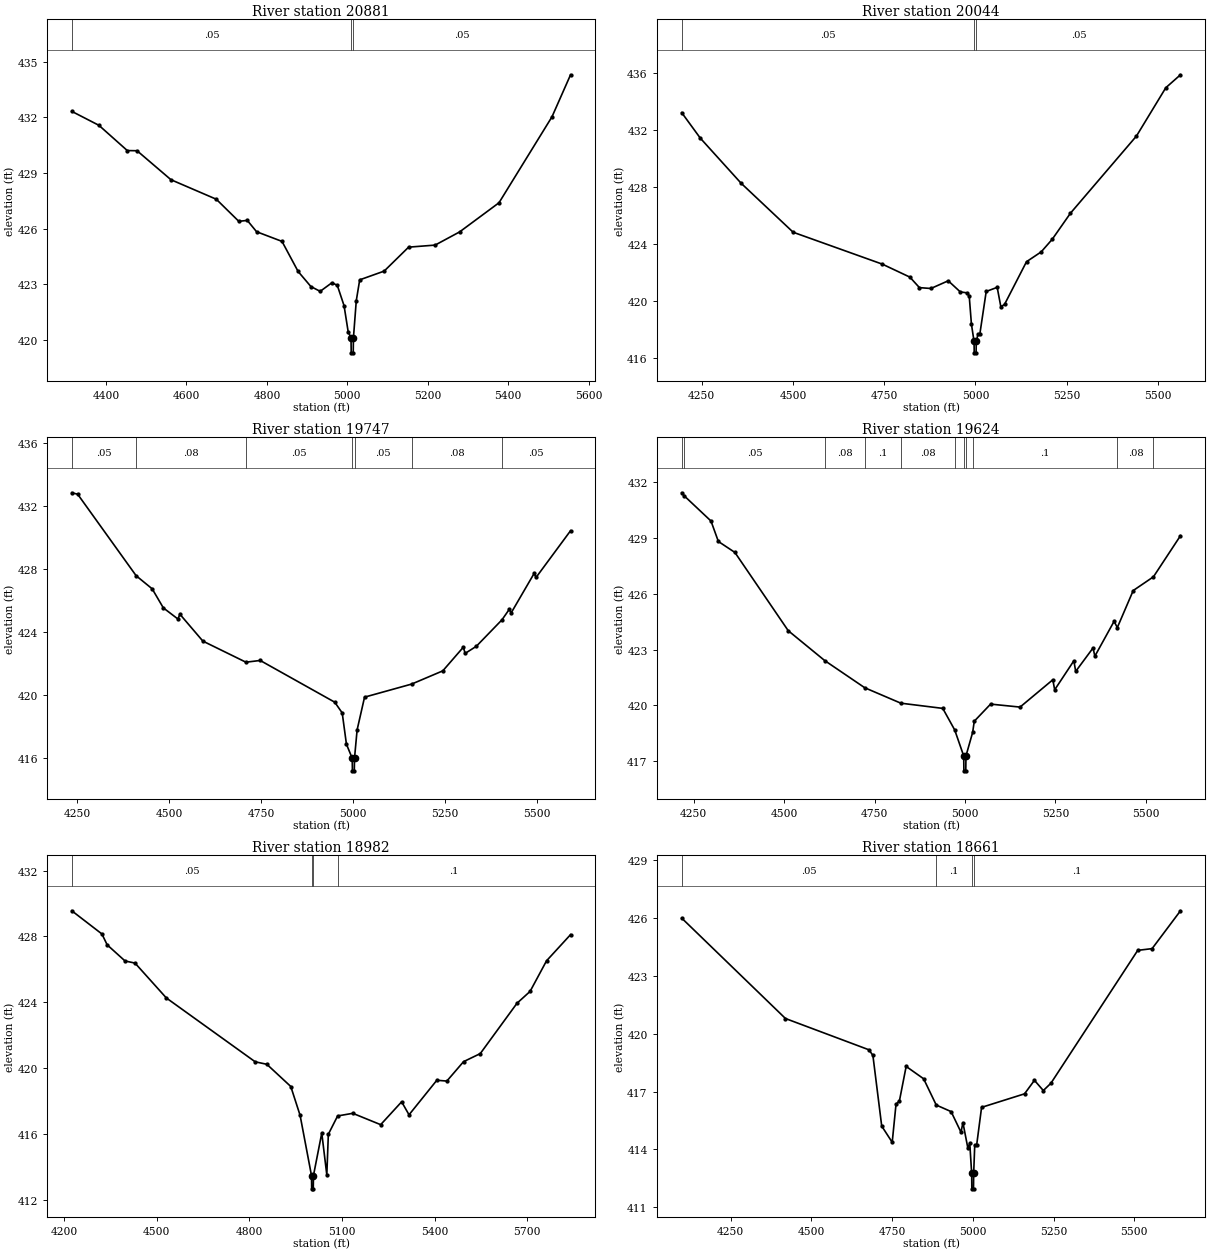
Type RM Length L Ch R = 1,20881,837,837,837
BEGIN DESCRIPTION:
UNT 052 in RCW 35.0
END DESCRIPTION:
XS GIS Cut Line= 3
      2037555.73     13430098.96      2037755.73     13429498.96
      2037855.64     13428899.48
#Sta/Elev= 30
  4314.8  432.32  4382.2  431.57  4452.8  430.21  4477.1  430.20  4561.4  428.64
  4674.1  427.59  4730.1  426.40  4751.2  426.45  4774.3  425.84  4837.5  425.32
  4877.6  423.70  4909.3  422.89  4932.4  422.63  4961.4  423.09  4974.9  422.96
  4991.8  421.86  5002.0  420.46  5009.1  420.12  5009.6  419.32  5014.6  419.32
  5015.1  420.12  5022.2  422.13  5030.7  423.25  5091.5  423.72  5152.3  425.01
  5218.2  425.12  5279.1  425.83  5377.1  427.40  5508.9  432.03  5555.0  434.29
#Mann=3,-1,0
  4314.8    0.05       0  5009.1    0.03       0  5015.1    0.05       0
Bank Sta=5009.1,5015.1
Exp/Cntr=0.3,0.1

Type RM Length L Ch R = 1,20044,297,297,297
BEGIN DESCRIPTION:
UNT 052 in RCW 34.0
END DESCRIPTION:
XS GIS Cut Line= 3
      2038124.99     13430225.05      2038275.00     13429425.00
      2038225.00     13428874.96
#Sta/Elev= 30
  4195.4  433.21  4246.3  431.42  4358.2  428.25  4500.7  424.81  4744.9  422.57
  4820.3  421.66  4846.6  420.92  4878.0  420.86  4925.5  421.40  4958.5  420.62
  4978.0  420.55  4983.1  420.30  4989.0  418.36  4996.2  417.14  4996.7  416.34
  5001.8  416.34  5002.3  417.14  5006.8  417.63  5011.9  417.63  5029.5  420.65
  5059.6  420.94  5069.6  419.58  5079.7  419.74  5139.9  422.74  5180.1  423.43
  5210.2  424.31  5260.4  426.15  5441.2  431.57  5521.5  434.96  5561.7  435.87
#Mann=3,-1,0
  4195.4    0.05       0  4996.2    0.03       0  5002.3    0.05       0
Bank Sta=4996.2,5002.3
Exp/Cntr=0.3,0.1

Type RM Length L Ch R = 1,19747,123,123,123
BEGIN DESCRIPTION:
Mapping XS cf7f007c
END DESCRIPTION:
XS GIS Cut Line= 2
      2038394.41     13430340.71      2038605.36     13429002.13
#Sta/Elev= 30
  4236.2  432.83  4252.1  432.74  4411.1  427.56  4454.6  426.73  4484.9  425.52
  4524.7  424.81  4529.8  425.12  4592.3  423.41  4709.3  422.07  4748.1  422.18
  4950.6  419.53  4970.9  418.85  4982.4  416.86  4998.1  415.97  4998.6  415.17
  5003.8  415.17  5004.3  415.97  5011.4  417.77  5031.6  419.85  5159.5  420.68
  5244.2  421.52  5299.9  423.02  5305.0  422.63  5335.3  423.08  5404.9  424.76
  5424.9  425.43  5429.9  425.20  5492.4  427.71  5497.5  427.45  5591.3  430.42
#Mann=7,-1,0
  4236.2    0.05       0  4411.1    0.08       0  4709.3    0.05       0
  4998.1    0.03       0  5004.3    0.05       0  5159.5    0.08       0
  5404.9    0.05       0
Bank Sta=4998.1,5004.3
Exp/Cntr=0.3,0.1

Type RM Length L Ch R = 1,19624,642,642,642
BEGIN DESCRIPTION:
Mapping XS 1540250a
END DESCRIPTION:
XS GIS Cut Line= 2
      2038493.37     13430374.57      2038743.17     13429018.90
#Sta/Elev= 30
  4217.0  431.44  4224.2  431.27  4297.9  429.92  4318.3  428.82  4364.0  428.23
  4511.4  424.02  4612.4  422.41  4722.9  420.95  4822.6  420.12  4938.5  419.84
  4971.5  418.68  4996.4  417.28  4996.9  416.48  5002.1  416.48  5002.6  417.28
  5021.1  418.55  5025.6  419.15  5070.7  420.07  5152.1  419.91  5242.7  421.38
  5247.8  420.84  5300.8  422.40  5305.9  421.83  5353.8  423.09  5358.9  422.65
  5411.9  424.52  5421.0  424.19  5464.9  426.18  5520.8  426.92  5595.5  429.13
#Mann=11,-1,0
  4217.0    0.08       0  4224.2    0.05       0  4612.4    0.08       0
  4722.9     0.1       0  4822.6    0.08       0  4971.5    0.05       0
  4996.4    0.03       0  5002.6    0.05       0  5021.1     0.1       0
  5421.0    0.08       0  5520.8     0.1       0
Bank Sta=4996.4,5002.6
Exp/Cntr=0.3,0.1

Type RM Length L Ch R = 1,18982,321,321,321
BEGIN DESCRIPTION:
Mapping XS 332a032b
END DESCRIPTION:
XS GIS Cut Line= 4
      2038808.46     13430509.99      2039084.52     13429942.24
      2039115.77     13429549.01      2038891.82     13429004.76
#Sta/Elev= 30
  4225.6  429.56  4323.1  428.15  4340.1  427.49  4397.9  426.51  4430.3  426.38
  4531.7  424.26  4819.3  420.38  4856.9  420.23  4934.4  418.88  4964.5  417.13
  5001.5  413.46  5002.0  412.66  5007.2  412.66  5007.7  413.46  5034.7  416.05
  5051.0  413.51  5056.0  415.98  5086.0  417.09  5135.0  417.25  5225.3  416.56
  5293.2  417.95  5317.1  417.16  5407.1  419.26  5439.5  419.21  5493.6  420.39
  5547.7  420.88  5666.6  423.94  5708.9  424.66  5762.2  426.52  5839.9  428.11
#Mann=4,-1,0
  4225.6    0.05       0  5001.5    0.03       0  5007.7    0.05       0
  5086.0     0.1       0
Bank Sta=5001.5,5007.7
Exp/Cntr=0.3,0.1

Type RM Length L Ch R = 1,18661,350,350,350
BEGIN DESCRIPTION:
Mapping XS 6d8c8b0c
END DESCRIPTION:
XS GIS Cut Line= 4
      2039035.04     13430478.72      2039256.40     13429767.76
      2039144.42     13429588.07      2039022.03     13429012.59
#Sta/Elev= 30
  4098.4  425.98  4419.8  420.78  4678.3  419.16  4690.5  418.87  4717.8  415.21
  4750.3  414.37  4762.1  416.34  4772.6  416.51  4793.5  418.30  4847.6  417.66
  4886.7  416.30  4932.7  415.96  4963.4  414.89  4969.3  415.39  4984.6  414.07
  4990.5  414.32  4996.4  412.76  4996.9  411.96  5002.1  411.96  5002.6  412.76
  5005.9  414.21  5011.8  414.22  5027.1  416.18  5160.1  416.88  5190.8  417.58
  5218.3  417.05  5241.9  417.43  5510.7  424.31  5555.2  424.40  5643.1  426.36
#Mann=4,-1,0
  4098.4    0.05       0  4886.7     0.1       0  4996.4    0.07       0
  5002.6     0.1       0
Bank Sta=4996.4,5002.6
Exp/Cntr=0.3,0.1

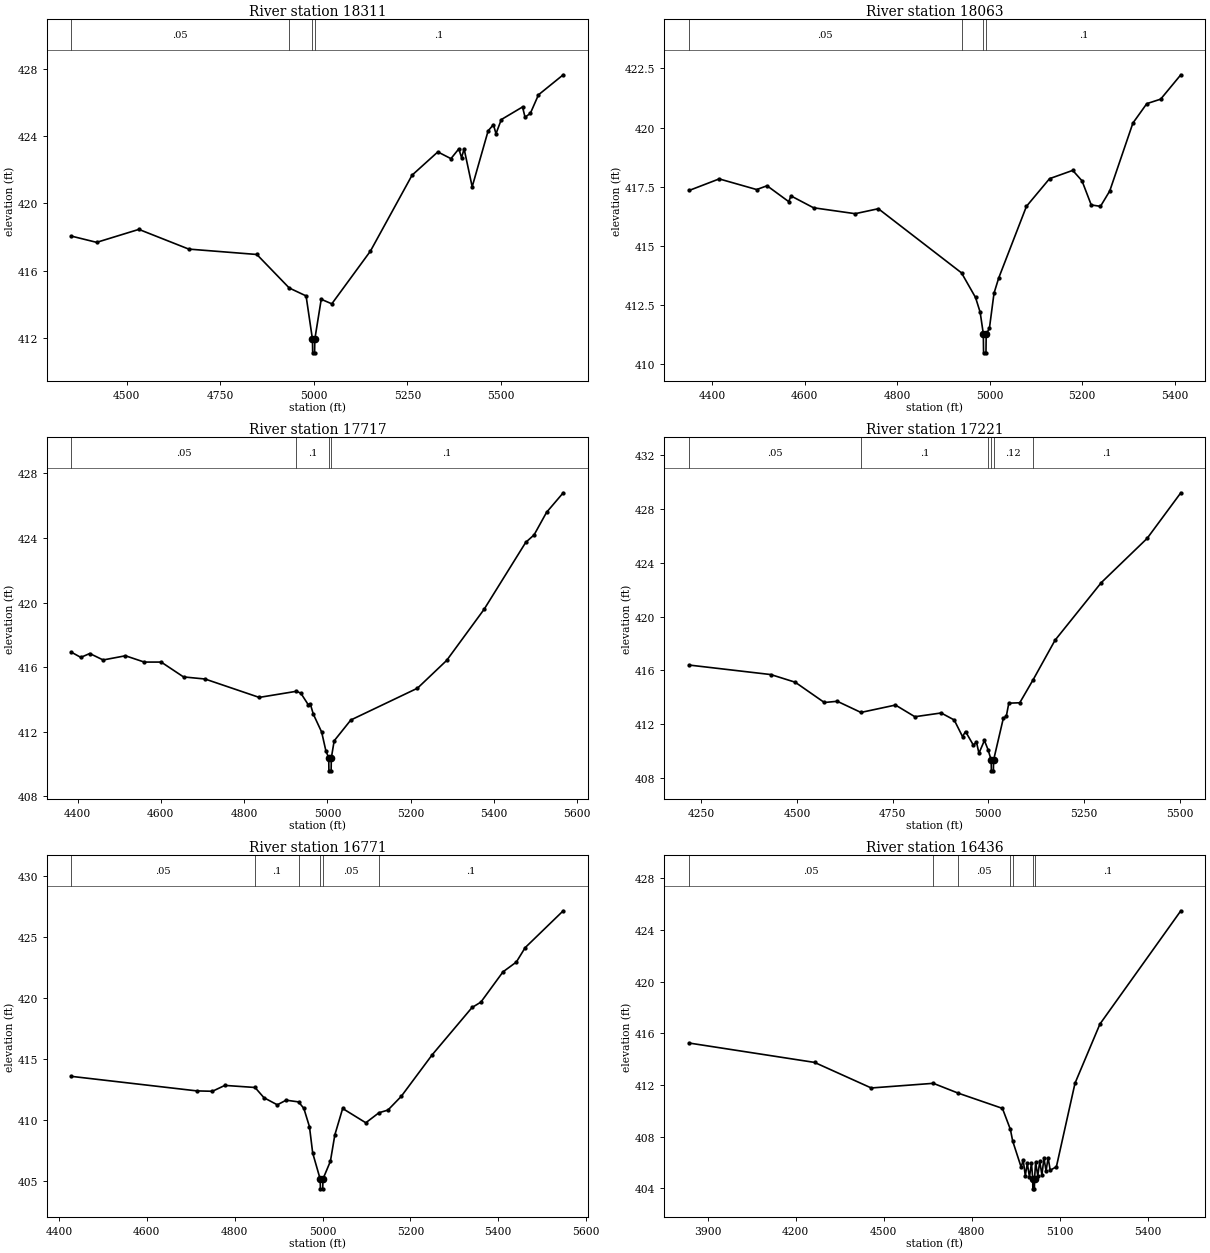
Type RM Length L Ch R = 1,18311,248,248,248
BEGIN DESCRIPTION:
Mapping XS 73e8af59
END DESCRIPTION:
XS GIS Cut Line= 4
      2039449.10     13430090.64      2039381.40     13429799.01
      2039285.04     13429179.22      2038996.64     13428919.40
#Sta/Elev= 30
  4352.0  418.06  4419.4  417.69  4532.3  418.46  4665.6  417.29  4847.7  416.97
  4934.3  414.98  4979.3  414.51  4996.4  411.93  4996.9  411.13  5002.1  411.13
  5002.6  411.93  5019.8  414.31  5048.1  414.04  5151.3  417.17  5262.7  421.68
  5331.5  423.06  5366.6  422.66  5387.6  423.24  5395.0  422.72  5401.8  423.24
  5423.4  420.99  5466.0  424.31  5480.2  424.68  5487.0  424.14  5501.2  424.98
  5558.0  425.73  5564.7  425.12  5578.9  425.35  5600.6  426.45  5666.8  427.64
#Mann=4,-1,0
  4352.0    0.05       0  4934.3     0.1       0  4996.4    0.07       0
  5002.6     0.1       0
Bank Sta=4996.4,5002.6
Exp/Cntr=0.3,0.1

Type RM Length L Ch R = 1,18063,346,346,346
BEGIN DESCRIPTION:
Mapping XS ef8980f5
END DESCRIPTION:
XS GIS Cut Line= 3
      2039571.51     13429973.50      2039511.61     13429809.43
      2039477.75     13428921.44
#Sta/Elev= 30
  4350.1  417.34  4415.3  417.83  4496.3  417.38  4518.8  417.54  4565.6  416.87
  4570.6  417.11  4619.3  416.61  4709.3  416.36  4759.4  416.57  4939.2  413.86
  4969.5  412.82  4979.5  412.20  4986.4  411.28  4986.9  410.48  4992.1  410.48
  4992.6  411.28  4999.5  411.51  5009.5  413.00  5019.6  413.64  5079.6  416.67
  5129.6  417.84  5179.7  418.19  5199.7  417.75  5219.7  416.73  5239.7  416.67
  5259.7  417.32  5309.8  420.19  5339.8  421.01  5369.8  421.20  5413.4  422.23
#Mann=4,-1,0
  4350.1    0.05       0  4939.2     0.1       0  4986.4    0.07       0
  4992.6     0.1       0
Bank Sta=4986.4,4992.6
Exp/Cntr=0.3,0.1

Type RM Length L Ch R = 1,17717,496,496,496
BEGIN DESCRIPTION:
Mapping XS be8c64e5
END DESCRIPTION:
XS GIS Cut Line= 3
      2039688.24     13430036.04      2039794.59     13429760.38
      2039811.95     13428875.01
#Sta/Elev= 30
  4385.3  416.92  4407.8  416.60  4429.3  416.84  4461.4  416.44  4515.0  416.70
  4560.1  416.31  4600.8  416.31  4654.4  415.39  4706.1  415.26  4836.2  414.12
  4925.7  414.50  4936.2  414.38  4953.9  413.67  4958.9  413.71  4966.2  413.08
  4986.2  411.97  4996.2  410.82  5003.1  410.37  5003.6  409.57  5008.9  409.57
  5009.4  410.37  5016.2  411.43  5056.2  412.72  5216.2  414.69  5286.3  416.41
  5376.3  419.58  5476.3  423.73  5496.3  424.19  5526.3  425.59  5566.3  426.80
#Mann=4,-1,0
  4385.3    0.05       0  4925.7     0.1       0  5003.1    0.07       0
  5009.4     0.1       0
Bank Sta=5003.1,5009.4
Exp/Cntr=0.3,0.1

Type RM Length L Ch R = 1,17221,450,450,450
BEGIN DESCRIPTION:
Mapping XS 7610c680
END DESCRIPTION:
XS GIS Cut Line= 4
      2039733.82     13430066.38      2039987.73     13429814.64
      2040031.14     13429556.39      2040460.44     13429046.86
#Sta/Elev= 30
  4217.5  416.39  4431.4  415.68  4495.1  415.11  4571.2  413.60  4605.1  413.69
  4666.9  412.86  4757.2  413.41  4807.9  412.54  4876.6  412.82  4910.7  412.30
  4932.5  411.06  4940.3  411.44  4961.1  410.41  4968.9  410.67  4975.4  409.82
  4989.7  410.77  4999.2  410.09  5007.4  409.31  5007.9  408.51  5013.2  408.51
  5013.7  409.31  5039.2  412.43  5046.9  412.57  5053.5  413.55  5082.1  413.58
  5117.0  415.29  5174.4  418.24  5295.3  422.53  5415.0  425.82  5503.2  429.22
#Mann=6,-1,0
  4217.5    0.05       0  4666.9     0.1       0  4999.2    0.12       0
  5007.4    0.07       0  5013.7    0.12       0  5117.0     0.1       0
Bank Sta=5007.4,5013.7
Exp/Cntr=0.3,0.1

Type RM Length L Ch R = 1,16771,335,335,335
BEGIN DESCRIPTION:
Mapping XS a6fd0057
END DESCRIPTION:
XS GIS Cut Line= 3
      2040120.54     13430134.52      2040401.80     13429860.21
      2040491.95     13429138.99
#Sta/Elev= 30
  4428.3  413.60  4713.9  412.41  4749.3  412.38  4777.6  412.86  4846.3  412.69
  4866.7  411.85  4897.0  411.27  4917.1  411.65  4945.3  411.51  4957.4  410.98
  4970.2  409.48  4977.6  407.32  4994.6  405.19  4995.1  404.39  5000.4  404.39
  5000.9  405.19  5017.9  406.65  5028.0  408.81  5045.8  410.97  5098.5  409.80
  5128.4  410.62  5148.9  410.84  5179.1  411.96  5249.7  415.37  5340.4  419.24
  5360.5  419.68  5410.9  422.16  5441.2  422.96  5461.3  424.14  5548.0  427.16
#Mann=6,-1,0
  4428.3    0.05       0  4846.3     0.1       0  4945.3    0.05       0
  4994.6   0.035       0  5000.9    0.05       0  5128.4     0.1       0
Bank Sta=4994.6,5000.9
Exp/Cntr=0.3,0.1

Type RM Length L Ch R = 1,16436,50,50,50
BEGIN DESCRIPTION:
Mapping XS fa16b1c9
END DESCRIPTION:
XS GIS Cut Line= 4
      2039746.75     13430376.18      2040222.00     13430124.46
      2040494.74     13430043.51      2041080.37     13429420.42
#Sta/Elev= 30
  3836.2  415.24  4264.2  413.74  4457.7  411.76  4669.3  412.12  4754.2  411.36
  4905.1  410.18  4932.3  408.55  4940.1  407.65  4969.0  405.63  4975.9  406.18
  4983.2  404.97  4990.0  405.93  4997.3  404.86  5004.2  405.94  5008.4  404.75
  5008.9  403.95  5014.2  403.95  5014.7  404.75  5018.4  406.01  5025.7  404.95
  5032.5  406.08  5039.8  405.02  5046.7  406.33  5054.0  405.33  5060.9  406.36
  5068.2  405.39  5089.2  405.66  5152.7  412.13  5237.7  416.71  5513.6  425.48
#Mann=7,-1,0
  3836.2    0.05       0  4669.3    0.08       0  4754.2    0.05       0
  4932.3    0.12       0  4940.1     0.1       0  5008.4    0.07       0
  5014.7     0.1       0
Bank Sta=5008.4,5014.7
Exp/Cntr=0.3,0.1

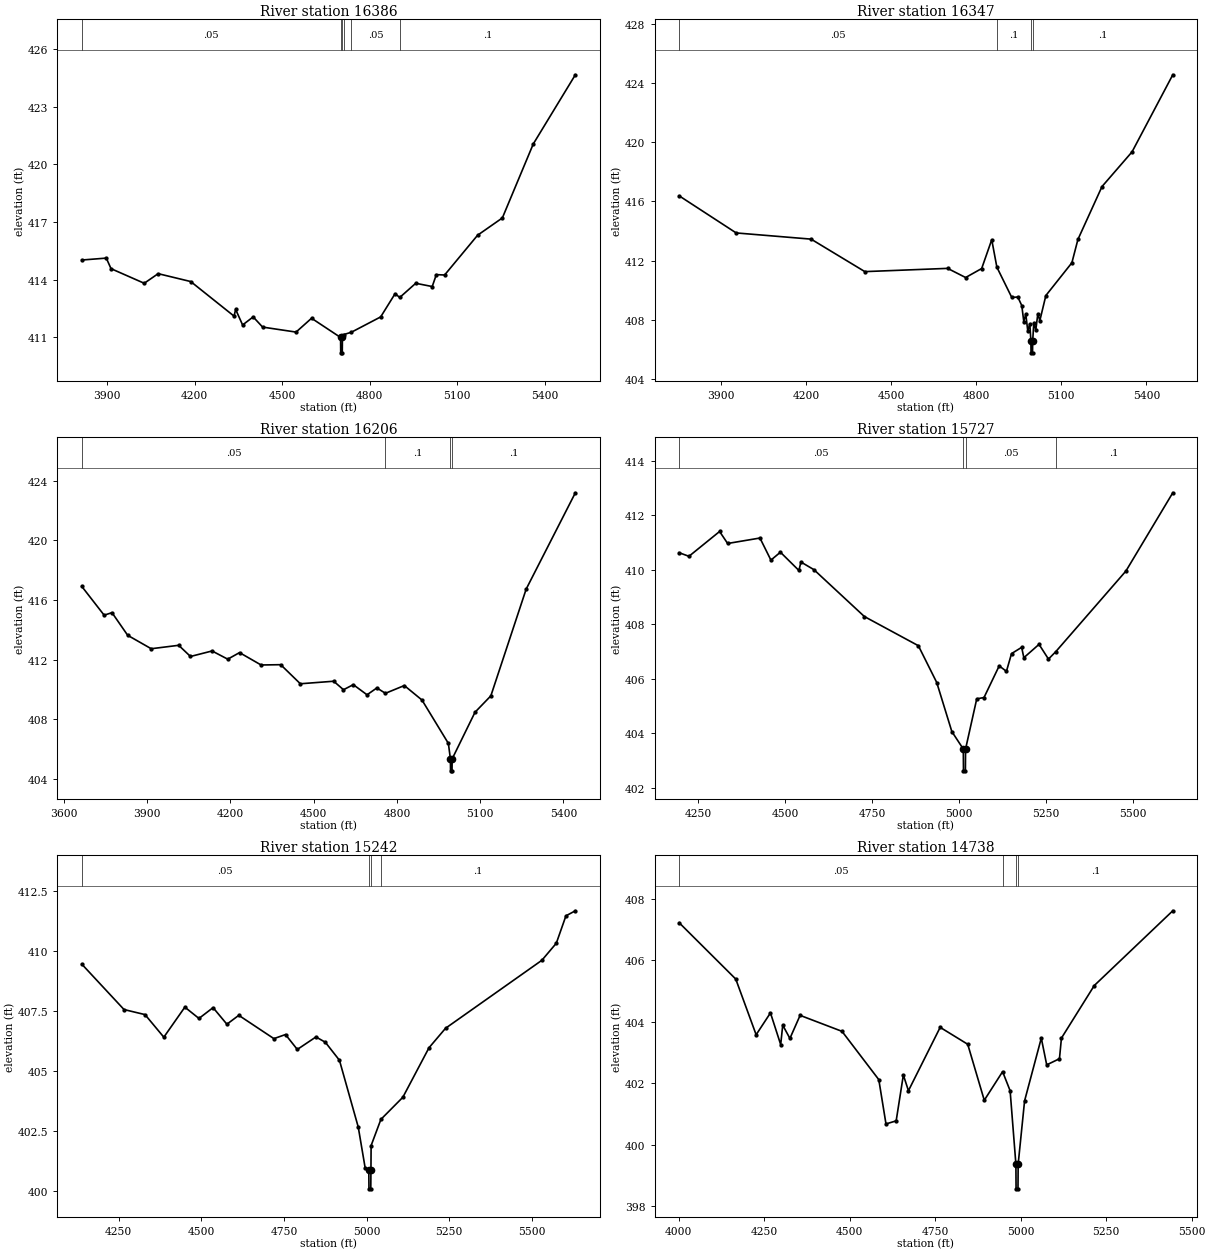
Type RM Length L Ch R = 1,16386,39,39,39
BEGIN DESCRIPTION:
Mapping XS 521dbda7
END DESCRIPTION:
XS GIS Cut Line= 3
      2039742.41     13430402.23      2040513.57     13430081.83
      2041117.95     13429473.92
#Sta/Elev= 30
  3813.0  415.02  3897.0  415.12  3913.3  414.57  4027.1  413.81  4074.9  414.31
  4186.5  413.90  4335.1  412.10  4340.5  412.45  4364.4  411.64  4400.6  412.06
  4433.0  411.53  4547.7  411.27  4600.8  411.99  4700.3  410.99  4700.8  410.19
  4706.1  410.19  4706.6  410.99  4710.8  411.14  4737.0  411.26  4837.8  412.06
  4887.3  413.27  4903.1  413.07  4958.0  413.81  5014.5  413.64  5028.7  414.26
  5057.0  414.24  5170.1  416.31  5255.0  417.21  5361.0  421.06  5505.3  424.66
#Mann=6,-1,0
  3813.0    0.05       0  4700.3    0.07       0  4706.6    0.05       0
  4710.8    0.08       0  4737.0    0.05       0  4903.1     0.1       0
Bank Sta=4700.3,4706.6
Exp/Cntr=0.3,0.1

Type RM Length L Ch R = 1,16347,141,141,141
BEGIN DESCRIPTION:
Mapping XS 9320bc63
END DESCRIPTION:
XS GIS Cut Line= 4
      2039725.02     13430482.54      2040556.11     13430102.57
      2040753.36     13429895.80      2041130.95     13429507.80
#Sta/Elev= 30
  3752.0  416.38  3952.9  413.87  4217.2  413.45  4406.8  411.25  4698.7  411.47
  4762.3  410.85  4818.9  411.46  4854.4  413.41  4872.5  411.55  4925.1  409.50
  4946.3  409.53  4960.4  408.95  4967.4  407.87  4974.5  408.37  4981.5  407.23
  4988.7  407.72  4992.5  406.55  4993.0  405.75  4998.3  405.75  4998.8  406.55
  5002.8  407.78  5009.8  407.30  5017.0  408.40  5024.0  407.93  5045.3  409.63
  5137.1  411.85  5158.4  413.43  5243.3  417.01  5349.3  419.36  5493.0  424.58
#Mann=4,-1,0
  3752.0    0.05       0  4872.5     0.1       0  4992.5    0.07       0
  4998.8     0.1       0
Bank Sta=4992.5,4998.8
Exp/Cntr=0.3,0.1

Type RM Length L Ch R = 1,16206,479,479,479
BEGIN DESCRIPTION:
UNT 052 in RCW 28.0
END DESCRIPTION:
XS GIS Cut Line= 3
      2039947.81     13430911.86      2040875.00     13429975.00
      2041175.01     13429624.98
#Sta/Elev= 30
  3664.0  416.91  3744.6  414.98  3772.9  415.15  3829.5  413.63  3914.3  412.73
  4013.3  412.96  4055.8  412.21  4133.6  412.58  4190.1  412.03  4232.6  412.47
  4310.3  411.64  4381.0  411.66  4451.8  410.38  4572.0  410.55  4607.3  409.98
  4642.7  410.32  4692.2  409.64  4727.6  410.10  4758.5  409.74  4826.6  410.26
  4890.2  409.29  4985.4  406.38  4992.7  405.34  4993.2  404.54  4998.5  404.54
  4999.0  405.34  5081.4  408.47  5138.5  409.57  5265.8  416.73  5443.1  423.19
#Mann=4,-1,0
  3664.0    0.05       0  4758.5     0.1       0  4992.7    0.07       0
  4999.0     0.1       0
Bank Sta=4992.7,4999
Exp/Cntr=0.3,0.1

Type RM Length L Ch R = 1,15727,485,485,485
BEGIN DESCRIPTION:
UNT 052 in RCW 27.0
END DESCRIPTION:
XS GIS Cut Line= 3
      2040324.58     13430783.37      2041027.17     13430377.17
      2041510.16     13430010.93
#Sta/Elev= 30
  4195.8  410.62  4223.8  410.49  4311.8  411.40  4334.9  410.96  4427.7  411.16
  4459.2  410.35  4486.5  410.64  4539.6  409.97  4545.4  410.28  4582.7  410.00
  4727.7  408.28  4882.7  407.21  4935.5  405.86  4978.9  404.06  5011.8  403.42
  5012.3  402.62  5017.8  402.62  5018.3  403.42  5050.4  405.26  5071.3  405.31
  5114.9  406.47  5135.7  406.27  5150.3  406.92  5179.4  407.15  5185.7  406.77
  5229.3  407.26  5256.4  406.72  5277.3  406.99  5478.9  409.95  5613.5  412.82
#Mann=4,-1,0
  4195.8    0.05       0  5011.8    0.03       0  5018.3    0.05       0
  5277.3     0.1       0
Bank Sta=5011.8,5018.3
Exp/Cntr=0.3,0.1

Type RM Length L Ch R = 1,15242,504,504,504
BEGIN DESCRIPTION:
UNT 052 in RCW 26.0
END DESCRIPTION:
XS GIS Cut Line= 3
      2040716.02     13431206.14      2041375.00     13430625.00
      2041744.70     13430134.05
#Sta/Elev= 30
  4138.2  409.46  4266.0  407.57  4329.5  407.36  4386.4  406.42  4450.0  407.67
  4492.7  407.20  4535.4  407.65  4577.2  406.96  4613.2  407.33  4719.4  406.36
  4754.5  406.53  4790.2  405.91  4846.6  406.43  4875.0  406.21  4917.7  405.46
  4974.6  402.68  4995.5  400.98  5006.5  400.91  5007.0  400.11  5012.5  400.11
  5013.0  400.91  5013.5  401.91  5043.1  403.00  5109.5  403.92  5188.6  405.98
  5238.6  406.79  5530.1  409.62  5573.8  410.33  5602.9  411.47  5631.4  411.68
#Mann=4,-1,0
  4138.2    0.05       0  5006.5    0.03       0  5013.0    0.05       0
  5043.1     0.1       0
Bank Sta=5006.5,5013
Exp/Cntr=0.3,0.1

Type RM Length L Ch R = 1,14738,515,515,515
BEGIN DESCRIPTION:
UNT 052 in RCW 25.0
END DESCRIPTION:
XS GIS Cut Line= 3
      2040978.59     13431370.00      2041775.00     13430825.00
      2042014.44     13430410.53
#Sta/Elev= 30
  4001.1  407.22  4166.5  405.39  4226.1  403.58  4268.0  404.29  4297.9  403.26
  4303.9  403.89  4324.9  403.46  4354.7  404.21  4477.3  403.69  4584.9  402.12
  4605.9  400.68  4635.7  400.78  4656.7  402.27  4671.6  401.76  4764.4  403.82
  4845.0  403.27  4893.4  401.45  4947.0  402.38  4969.0  401.76  4985.9  399.37
  4986.4  398.57  4992.0  398.57  4992.5  399.37  5011.3  401.43  5060.2  403.47
  5076.0  402.60  5113.3  402.80  5119.1  403.47  5215.2  405.18  5444.8  407.61
#Mann=4,-1,0
  4001.1    0.05       0  4947.0     0.1       0  4985.9    0.07       0
  4992.5     0.1       0
Bank Sta=4985.9,4992.5
Exp/Cntr=0.3,0.1

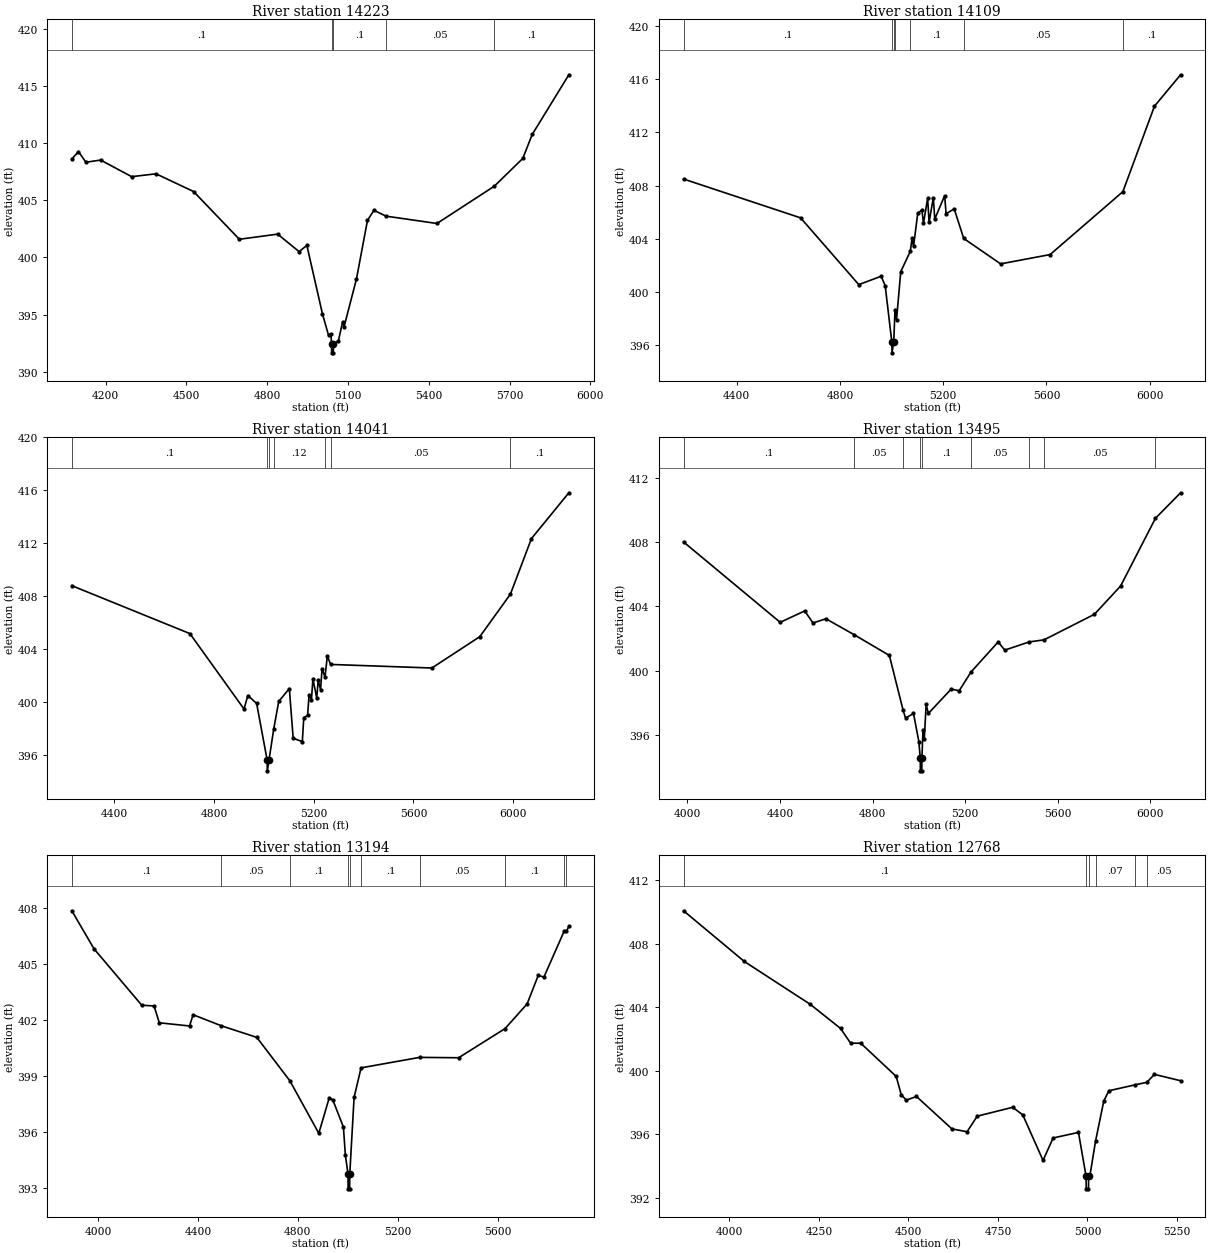
Type RM Length L Ch R = 1,14223,114,114,114
BEGIN DESCRIPTION:
Mapping XS e7877593
END DESCRIPTION:
XS GIS Cut Line= 4
      2041447.58     13432010.40      2041817.38     13431320.28
      2042090.82     13431164.03      2042648.14     13430666.61
#Sta/Elev= 30
  4074.9  408.60  4099.6  409.25  4127.2  408.32  4181.7  408.51  4297.0  407.06
  4387.3  407.31  4526.9  405.76  4696.7  401.59  4838.9  402.04  4918.7  400.51
  4947.3  401.06  5005.1  395.08  5027.9  393.19  5036.7  393.30  5038.9  392.47
  5039.4  391.67  5045.5  391.67  5046.1  392.47  5064.1  392.69  5079.9  394.36
  5085.7  393.97  5131.5  398.13  5172.3  403.24  5196.2  404.12  5241.3  403.61
  5430.2  402.97  5643.3  406.23  5748.8  408.65  5783.9  410.75  5919.8  415.96
#Mann=5,-1,0
  4074.9     0.1       0  5038.9    0.07       0  5046.1     0.1       0
  5241.3    0.05       0  5643.3     0.1       0
Bank Sta=5038.9,5046.1
Exp/Cntr=0.3,0.1

Type RM Length L Ch R = 1,14109,68,68,68
BEGIN DESCRIPTION:
Mapping XS b94c291c
END DESCRIPTION:
XS GIS Cut Line= 4
      2041460.60     13432018.20      2041840.82     13431359.34
      2042158.52     13431190.07      2042783.54     13430682.25
#Sta/Elev= 30
  4194.0  408.49  4647.6  405.57  4873.1  400.55  4959.9  401.18  4975.5  400.45
  5001.2  396.22  5001.7  395.42  5008.4  396.22  5013.5  398.67  5019.4  397.92
  5035.7  401.52  5072.7  403.06  5079.7  404.06  5085.3  403.42  5101.6  405.93
  5117.9  406.15  5123.6  405.15  5139.9  407.03  5145.5  405.24  5161.8  407.08
  5167.5  405.48  5205.8  407.24  5211.4  405.88  5242.7  406.25  5279.7  404.02
  5422.7  402.11  5614.5  402.81  5896.4  407.54  6018.9  413.97  6120.0  416.33
#Mann=7,-1,0
  4194.0     0.1       0  5001.2    0.07       0  5008.4     0.1       0
  5013.5    0.12       0  5072.7     0.1       0  5279.7    0.05       0
  5896.4     0.1       0
Bank Sta=5001.2,5008.4
Exp/Cntr=0.3,0.1

Type RM Length L Ch R = 1,14041,546,546,546
BEGIN DESCRIPTION:
Mapping XS a1cae662
END DESCRIPTION:
XS GIS Cut Line= 4
      2041473.63     13432044.24      2041846.02     13431429.65
      2042260.09     13431174.45      2042900.36     13430711.16
#Sta/Elev= 30
  4228.8  408.79  4702.8  405.17  4920.0  399.47  4935.5  400.49  4970.7  399.89
  5013.1  395.60  5013.6  394.80  5020.3  395.60  5039.5  397.98  5059.4  400.04
  5102.0  401.02  5117.4  397.26  5154.1  397.01  5160.0  398.82  5175.4  399.00
  5181.2  400.53  5190.8  400.19  5196.6  401.73  5212.0  400.32  5217.9  401.63
  5227.4  400.94  5233.3  402.50  5245.1  401.90  5254.6  403.47  5267.7  402.84
  5674.2  402.57  5866.8  404.94  5989.5  408.15  6074.0  412.35  6224.1  415.81
#Mann=7,-1,0
  4228.8     0.1       0  5013.1    0.07       0  5020.3     0.1       0
  5039.5    0.12       0  5245.1     0.1       0  5267.7    0.05       0
  5989.5     0.1       0
Bank Sta=5013.1,5020.3
Exp/Cntr=0.3,0.1

Type RM Length L Ch R = 1,13495,301,301,301
BEGIN DESCRIPTION:
Mapping XS 19afc08b
END DESCRIPTION:
XS GIS Cut Line= 4
      2041559.54     13432359.37      2042150.71     13431796.84
      2042471.02     13431072.88      2042956.44     13430839.26
#Sta/Elev= 30
  3983.9  408.01  4401.2  403.01  4507.2  403.72  4542.7  402.97  4599.0  403.23
  4721.8  402.23  4872.7  400.95  4931.9  397.55  4942.6  397.05  4976.9  397.34
  5000.1  395.59  5006.1  394.57  5006.7  393.77  5012.8  393.77  5013.3  394.57
  5017.9  396.33  5023.4  395.72  5031.6  397.90  5041.2  397.34  5139.8  398.86
  5174.1  398.75  5225.4  399.92  5342.6  401.79  5371.3  401.28  5476.3  401.79
  5540.7  401.92  5758.3  403.51  5871.4  405.27  6021.7  409.48  6130.3  411.07
#Mann=9,-1,0
  3983.9     0.1       0  4721.8    0.05       0  4931.9     0.1       0
  5006.1    0.07       0  5013.3     0.1       0  5225.4    0.05       0
  5476.3     0.1       0  5540.7    0.05       0  6021.7     0.1       0
Bank Sta=5006.1,5013.3
Exp/Cntr=0.3,0.1

Type RM Length L Ch R = 1,13194,426,426,426
BEGIN DESCRIPTION:
Mapping XS 26a0d4f4
END DESCRIPTION:
XS GIS Cut Line= 4
      2041760.09     13432414.02      2042140.30     13431953.09
      2042843.42     13431333.30      2043046.53     13430924.48
#Sta/Elev= 30
  3894.4  407.85  3983.0  405.82  4174.5  402.80  4224.0  402.76  4244.8  401.86
  4366.0  401.69  4380.3  402.29  4493.3  401.70  4635.4  401.08  4767.9  398.76
  4883.9  395.95  4925.7  397.85  4939.9  397.74  4982.6  396.28  4990.2  394.80
  5000.8  393.78  5001.3  392.98  5007.5  392.98  5008.0  393.78  5025.3  397.87
  5053.3  399.45  5287.8  400.01  5444.0  399.99  5630.2  401.55  5718.5  402.87
  5763.3  404.40  5785.7  404.30  5867.6  406.78  5876.2  406.75  5885.7  407.02
#Mann=10,-1,0
  3894.4     0.1       0  4493.3    0.05       0  4767.9     0.1       0
  5000.8    0.07       0  5008.0     0.1       0  5053.3     0.1       0
  5287.8    0.05       0  5630.2     0.1       0  5867.6    0.05       0
  5876.2     0.1       0
Bank Sta=5000.8,5008
Exp/Cntr=0.3,0.1

Type RM Length L Ch R = 1,12768,625,625,625
BEGIN DESCRIPTION:
UNT 052 in RCW 21.0
END DESCRIPTION:
XS GIS Cut Line= 3
      2041874.97     13432675.03      2042675.00     13431875.00
      2042856.74     13431693.45
#Sta/Elev= 30
  3871.9  410.07  4041.7  406.88  4225.5  404.19  4310.4  402.67  4338.6  401.74
  4366.9  401.74  4465.9  399.65  4480.1  398.49  4494.2  398.16  4522.5  398.39
  4621.5  396.35  4663.9  396.17  4692.2  397.15  4791.2  397.71  4819.5  397.23
  4876.0  394.37  4904.3  395.78  4975.0  396.13  4996.2  393.38  4996.7  392.58
  5002.9  392.58  5003.4  393.38  5006.8  393.38  5022.7  395.58  5045.7  398.10
  5059.9  398.75  5132.8  399.12  5166.0  399.28  5187.2  399.78  5260.2  399.38
#Mann=6,-1,0
  3871.9     0.1       0  4996.2    0.07       0  5003.4     0.1       0
  5022.7    0.07       0  5132.8     0.1       0  5166.0    0.05       0
Bank Sta=4996.2,5003.4
Exp/Cntr=0.3,0.1

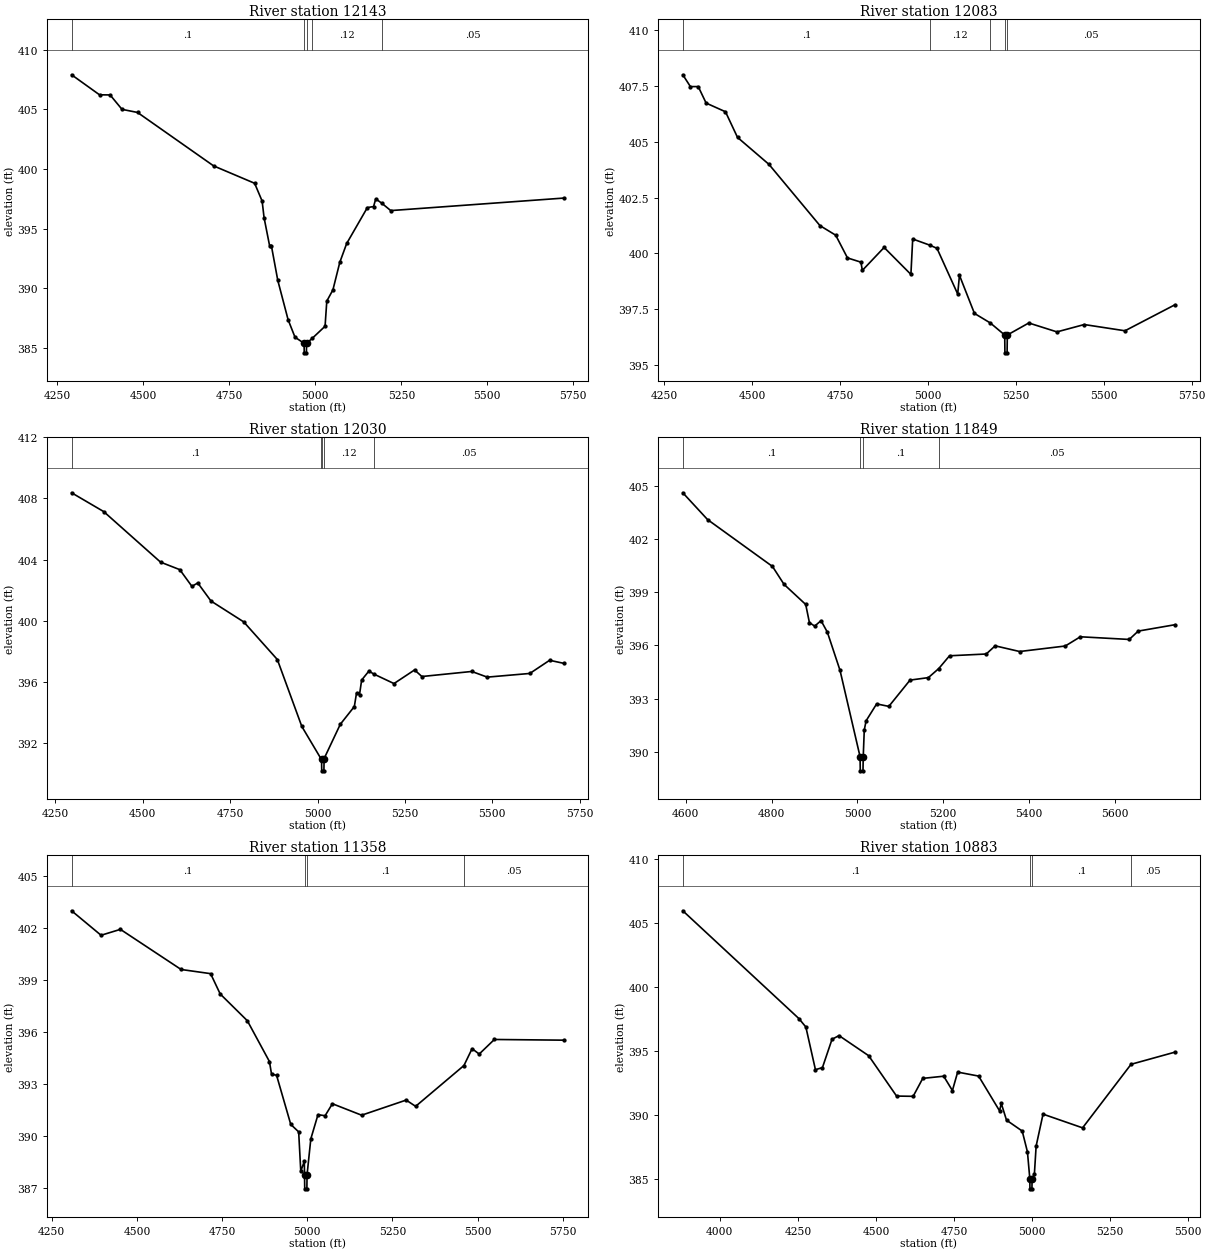
Type RM Length L Ch R = 1,12143,60,60,60
BEGIN DESCRIPTION:
UNT 052 in RCW 20.0
END DESCRIPTION:
XS GIS Cut Line= 4
      2042046.95     13432648.05      2042552.62     13432370.26
      2042841.25     13432387.62      2043290.81     13432045.56
#Sta/Elev= 30
  4291.3  407.91  4372.5  406.23  4403.2  406.22  4437.9  405.01  4483.0  404.75
  4704.1  400.27  4823.4  398.81  4845.2  397.32  4850.9  395.92  4866.8  393.59
  4872.0  393.59  4890.7  390.67  4920.7  387.37  4940.8  385.90  4967.1  385.39
  4967.7  384.59  4973.9  384.59  4974.5  385.39  4991.4  385.82  5028.2  386.82
  5033.2  388.93  5051.0  389.87  5071.0  392.18  5091.0  393.76  5151.1  396.77
  5169.2  396.86  5175.5  397.50  5193.0  397.14  5219.1  396.52  5722.3  397.57
#Mann=5,-1,0
  4291.3     0.1       0  4967.1    0.07       0  4974.5     0.1       0
  4991.4    0.12       0  5193.0    0.05       0
Bank Sta=4967.1,4974.5
Exp/Cntr=0.3,0.1

Type RM Length L Ch R = 1,12083,53,53,53
BEGIN DESCRIPTION:
Mapping XS 6d88513a
END DESCRIPTION:
XS GIS Cut Line= 4
      2042055.68     13432676.24      2042509.22     13432450.55
      2042832.57     13432426.68      2043298.43     13432099.50
#Sta/Elev= 30
  4302.7  408.01  4324.3  407.48  4346.6  407.48  4369.0  406.74  4424.1  406.35
  4458.3  405.20  4547.7  403.99  4692.8  401.24  4737.6  400.81  4771.1  399.79
  4809.3  399.60  4813.4  399.23  4875.3  400.26  4951.5  399.05  4956.6  400.64
  5005.7  400.36  5025.7  400.22  5084.6  398.17  5089.6  399.01  5132.2  397.30
  5177.4  396.87  5218.3  396.33  5218.9  395.53  5225.1  395.53  5225.7  396.33
  5286.8  396.87  5366.9  396.47  5444.5  396.80  5560.4  396.52  5702.8  397.69
#Mann=5,-1,0
  4302.7     0.1       0  5005.7    0.12       0  5177.4    0.05       0
  5218.3    0.07       0  5225.7    0.05       0
Bank Sta=5218.3,5225.7
Exp/Cntr=0.3,0.1

Type RM Length L Ch R = 1,12030,181,181,181
BEGIN DESCRIPTION:
Mapping XS d2632763
END DESCRIPTION:
XS GIS Cut Line= 4
      2042067.77     13432710.99      2042508.78     13432492.22
      2042810.87     13432480.07      2043311.32     13432125.07
#Sta/Elev= 30
  4296.5  408.37  4388.5  407.14  4551.0  403.84  4606.0  403.35  4640.7  402.26
  4657.5  402.48  4695.3  401.30  4788.8  399.94  4885.1  397.48  4955.1  393.11
  5009.2  391.03  5011.5  391.01  5012.1  390.21  5018.3  390.21  5018.9  391.01
  5065.2  393.25  5105.4  394.41  5111.6  395.29  5120.2  395.19  5126.3  396.14
  5147.2  396.73  5160.3  396.54  5218.8  395.91  5277.7  396.80  5298.6  396.37
  5441.3  396.70  5485.6  396.33  5607.4  396.57  5664.0  397.43  5704.7  397.23
#Mann=5,-1,0
  4296.5     0.1       0  5009.2    0.12       0  5011.5    0.07       0
  5018.9    0.12       0  5160.3    0.05       0
Bank Sta=5011.5,5018.9
Exp/Cntr=0.3,0.1

Type RM Length L Ch R = 1,11849,491,491,491
BEGIN DESCRIPTION:
UNT 052 in RCW 19.0
END DESCRIPTION:
XS GIS Cut Line= 3
      2042475.02     13432874.99      2042825.00     13432625.00
      2043364.27     13432153.23
#Sta/Elev= 30
  4593.3  404.60  4651.0  403.09  4802.2  400.45  4829.2  399.44  4879.6  398.31
  4888.2  397.29  4900.5  397.09  4915.3  397.40  4930.0  396.75  4959.5  394.60
  5006.2  389.74  5006.7  388.94  5013.0  388.94  5013.6  389.74  5016.0  391.24
  5020.3  391.76  5044.8  392.71  5073.2  392.57  5122.6  394.05  5165.3  394.19
  5189.5  394.70  5214.6  395.42  5300.1  395.52  5320.9  395.98  5377.9  395.66
  5484.2  395.97  5519.3  396.49  5633.2  396.34  5654.1  396.81  5739.9  397.17
#Mann=4,-1,0
  4593.3     0.1       0  5006.2    0.07       0  5013.6     0.1       0
  5189.5    0.05       0
Bank Sta=5006.2,5013.6
Exp/Cntr=0.3,0.1

Type RM Length L Ch R = 1,11358,475,475,475
BEGIN DESCRIPTION:
UNT 052 in RCW 18.0
END DESCRIPTION:
XS GIS Cut Line= 3
      2042675.04     13433224.97      2043225.00     13432825.00
      2043664.24     13432198.94
#Sta/Elev= 30
  4308.3  402.99  4394.8  401.58  4451.6  401.92  4629.7  399.61  4716.3  399.37
  4744.5  398.20  4824.1  396.66  4889.0  394.31  4895.2  393.58  4909.9  393.52
  4951.6  390.69  4974.8  390.26  4981.0  387.99  4991.4  388.57  4992.0  387.78
  4992.6  386.98  4998.9  386.98  4999.4  387.78  5010.5  389.86  5031.5  391.25
  5052.4  391.19  5073.8  391.88  5159.6  391.22  5290.3  392.09  5318.1  391.73
  5459.9  394.08  5483.8  395.05  5504.7  394.74  5549.2  395.58  5753.1  395.54
#Mann=4,-1,0
  4308.3     0.1       0  4992.0    0.07       0  4999.4     0.1       0
  5459.9    0.05       0
Bank Sta=4992,4999.4
Exp/Cntr=0.3,0.1

Type RM Length L Ch R = 1,10883,707,707,707
BEGIN DESCRIPTION:
UNT 052 in RCW 17.0
END DESCRIPTION:
XS GIS Cut Line= 3
      2043124.98     13433675.04      2043625.00     13432675.00
      2043837.95     13432268.59
#Sta/Elev= 30
  3881.4  405.96  4253.2  397.55  4275.6  396.89  4306.3  393.56  4328.7  393.72
  4359.4  395.93  4381.8  396.22  4476.8  394.65  4566.2  391.50  4619.3  391.48
  4650.1  392.88  4717.2  393.05  4745.1  391.93  4761.9  393.37  4829.0  393.06
  4896.1  390.35  4901.7  390.92  4918.4  389.62  4968.7  388.77  4985.5  387.14
  4993.0  385.06  4993.5  384.26  4999.8  384.26  5000.4  385.06  5007.7  385.41
  5013.3  387.60  5035.4  390.09  5162.1  389.02  5317.4  393.98  5458.3  394.93
#Mann=4,-1,0
  3881.4     0.1       0  4993.0    0.07       0  5000.4     0.1       0
  5317.4    0.05       0
Bank Sta=4993,5000.4
Exp/Cntr=0.3,0.1