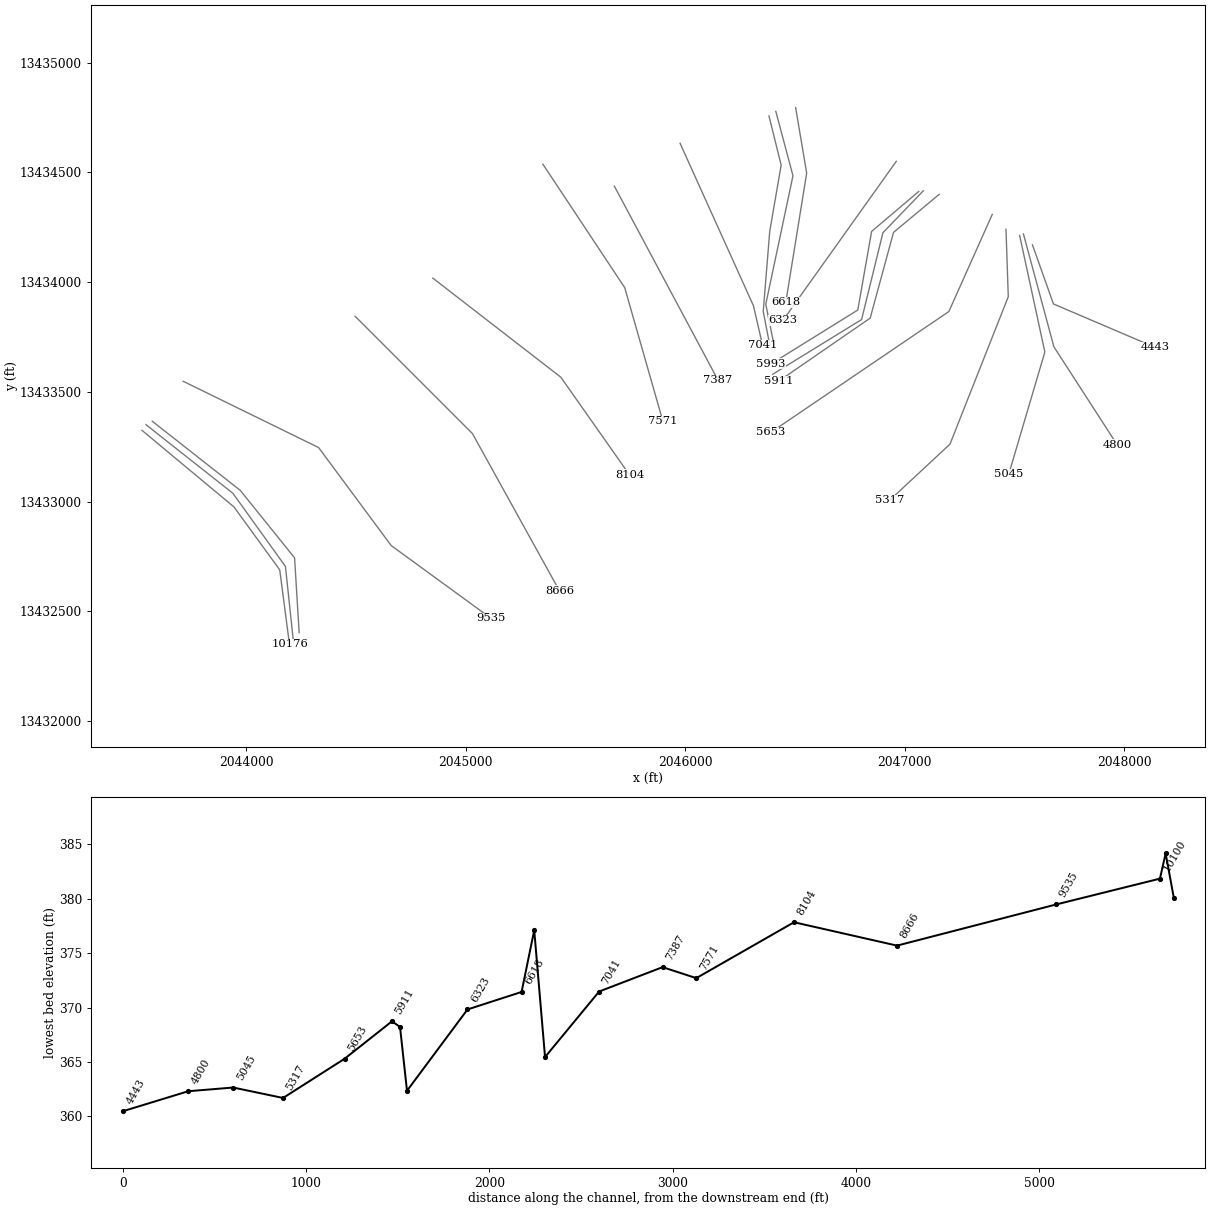
HEC-RAS study UNT 052 in RCW.prj: UNT 052 in RCW Base Level Engineering

--- UNT 052 in RCW.g01 (geometry) --- (continued)

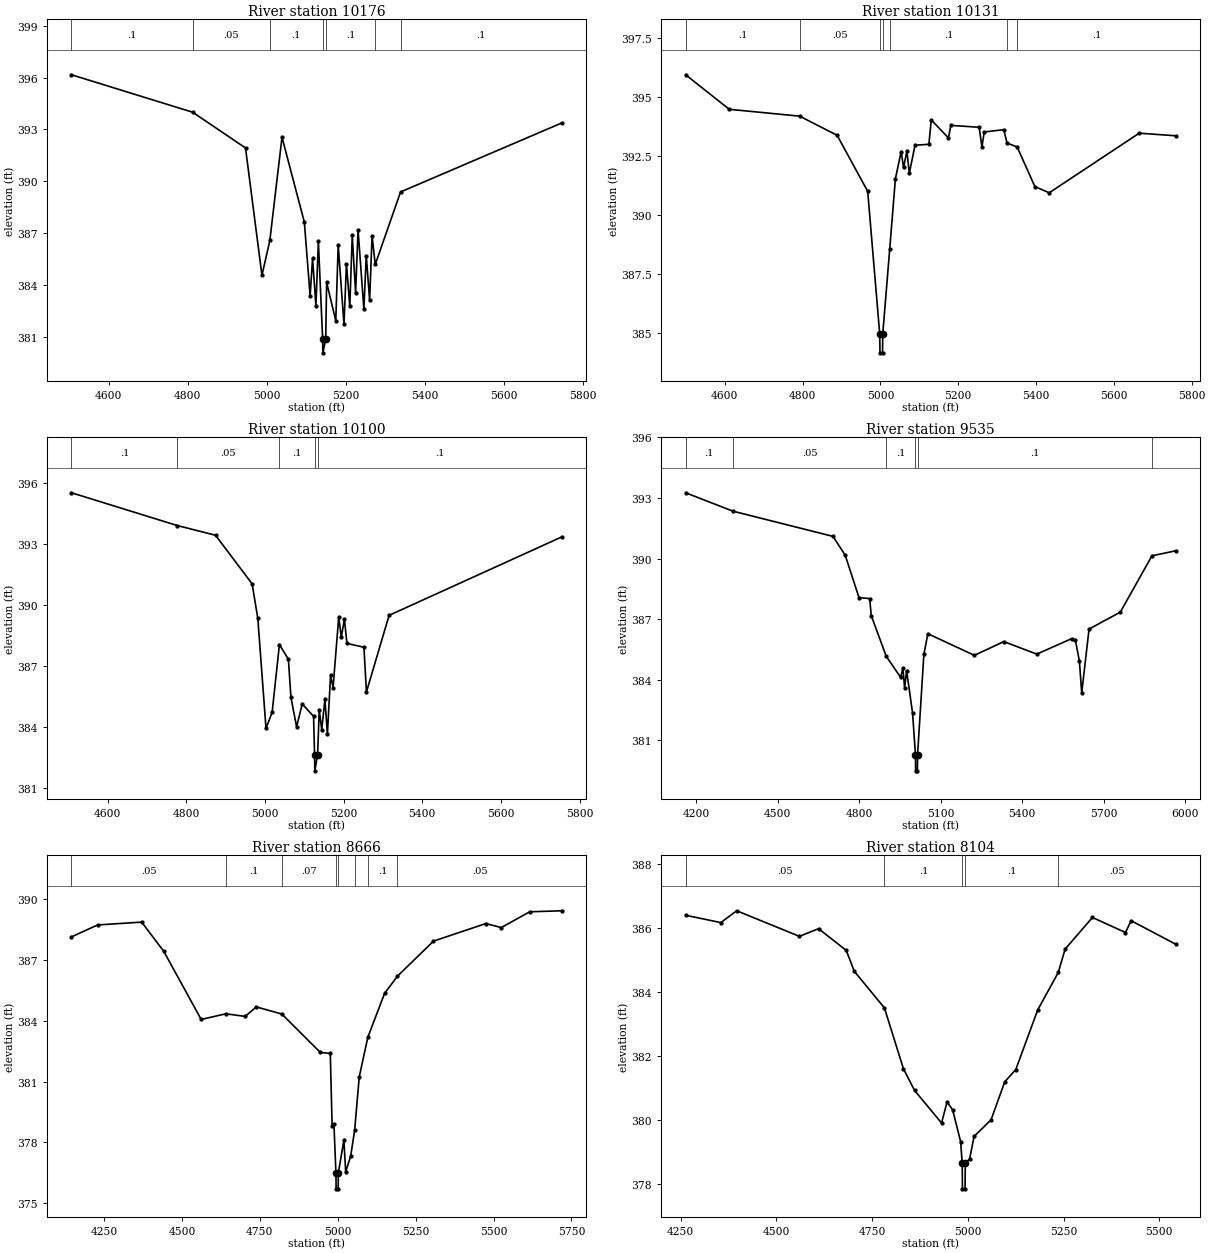
Type RM Length L Ch R = 1,10176,45,45,45
BEGIN DESCRIPTION:
UNT 052 in RCW 16.0
END DESCRIPTION:
XS GIS Cut Line= 4
      2043524.98     13433325.02      2043944.55     13432975.58
      2044152.88     13432689.12      2044197.16     13432350.54
#Sta/Elev= 30
  4505.6  396.17  4812.5  394.00  4946.3  391.93  4987.9  384.55  5007.9  386.57
  5038.7  392.55  5095.3  387.63  5109.9  383.37  5116.1  385.53  5124.6  382.79
  5130.8  386.52  5141.6  380.86  5142.2  380.06  5149.4  380.86  5151.7  384.14
  5174.9  381.92  5181.0  386.30  5195.7  381.71  5201.9  385.22  5210.4  382.75
  5216.6  386.86  5225.1  383.54  5231.3  387.19  5246.0  382.58  5252.1  385.69
  5260.6  383.10  5266.8  386.84  5274.8  385.18  5338.9  389.38  5747.3  393.38
#Mann=7,-1,0
  4505.6     0.1       0  4812.5    0.05       0  5007.9     0.1       0
  5141.6    0.03       0  5149.4     0.1       0  5274.8    0.12       0
  5338.9     0.1       0
Bank Sta=5141.6,5149.4
Exp/Cntr=0.3,0.1

Type RM Length L Ch R = 1,10131,31,31,31
BEGIN DESCRIPTION:
Mapping XS 3019e9d6
END DESCRIPTION:
XS GIS Cut Line= 4
      2043543.48     13433350.60      2043939.34     13433038.08
      2044178.92     13432704.75      2044215.38     13432361.04
#Sta/Elev= 30
  4499.2  395.94  4611.3  394.48  4792.3  394.19  4888.6  393.38  4967.2  391.01
  4998.1  384.98  4998.8  384.18  5005.3  384.18  5005.9  384.98  5023.8  388.57
  5038.5  391.55  5053.3  392.69  5059.4  392.02  5068.0  392.71  5074.2  391.78
  5088.9  392.96  5124.5  393.00  5130.6  394.03  5174.8  393.27  5181.0  393.80
  5253.7  393.72  5260.8  392.90  5266.9  393.52  5317.2  393.62  5325.3  393.05
  5351.4  392.89  5397.0  391.21  5433.9  390.95  5665.2  393.47  5759.7  393.36
#Mann=7,-1,0
  4499.2     0.1       0  4792.3    0.05       0  4998.1    0.03       0
  5005.9    0.05       0  5023.8     0.1       0  5325.3    0.12       0
  5351.4     0.1       0
Bank Sta=4998.1,5005.9
Exp/Cntr=0.3,0.1

Type RM Length L Ch R = 1,10100,565,565,565
BEGIN DESCRIPTION:
Mapping XS eff33bf6
END DESCRIPTION:
XS GIS Cut Line= 4
      2043572.18     13433366.19      2043973.19     13433051.10
      2044220.59     13432743.81      2044241.42     13432402.65
#Sta/Elev= 30
  4508.4  395.54  4777.0  393.93  4874.5  393.45  4967.5  391.06  4982.0  389.36
  5002.8  383.95  5018.4  384.74  5036.9  388.07  5059.7  387.35  5066.2  385.47
  5080.5  384.03  5094.9  385.15  5123.7  384.54  5126.2  382.66  5126.9  381.86
  5134.0  382.66  5138.1  384.85  5144.5  383.89  5152.5  385.37  5158.9  383.67
  5166.9  386.56  5173.3  385.96  5187.7  389.44  5194.1  388.43  5202.1  389.32
  5208.5  388.13  5251.7  387.94  5258.1  385.74  5315.7  389.51  5754.7  393.37
#Mann=5,-1,0
  4508.4     0.1       0  4777.0    0.05       0  5036.9     0.1       0
  5126.2    0.03       0  5134.0     0.1       0
Bank Sta=5126.2,5134
Exp/Cntr=0.3,0.1

Type RM Length L Ch R = 1,9535,869,869,869
BEGIN DESCRIPTION:
UNT 052 in RCW 15.0
END DESCRIPTION:
XS GIS Cut Line= 4
      2043712.79     13433548.49      2044329.97     13433246.42
      2044660.79     13432799.83      2045114.89     13432468.89
#Sta/Elev= 30
  4160.8  393.26  4334.6  392.35  4703.3  391.10  4748.3  390.16  4798.9  388.07
  4838.3  388.02  4843.9  387.18  4898.9  385.17  4952.1  384.12  4960.5  384.58
  4966.8  383.60  4974.1  384.45  4996.0  382.36  5006.7  380.29  5007.4  379.49
  5013.9  379.49  5014.5  380.29  5037.7  385.26  5052.3  386.28  5223.4  385.21
  5332.0  385.89  5453.3  385.27  5582.2  386.04  5595.4  385.96  5610.1  384.93
  5618.6  383.35  5645.7  386.51  5760.8  387.35  5877.2  390.14  5965.6  390.39
#Mann=6,-1,0
  4160.8     0.1       0  4334.6    0.05       0  4898.9     0.1       0
  5006.7    0.07       0  5014.5     0.1       0  5877.2    0.05       0
Bank Sta=5006.7,5014.5
Exp/Cntr=0.3,0.1

Type RM Length L Ch R = 1,8666,562,562,562
BEGIN DESCRIPTION:
UNT 052 in RCW 14.0
END DESCRIPTION:
XS GIS Cut Line= 3
      2044496.30     13433844.84      2045031.01     13433310.13
      2045426.84     13432594.85
#Sta/Elev= 30
  4145.4  388.15  4229.2  388.74  4370.6  388.88  4441.4  387.44  4561.6  384.07
  4641.0  384.35  4703.0  384.22  4738.3  384.69  4820.3  384.34  4944.1  382.44
  4976.0  382.39  4981.9  378.81  4987.7  378.89  4994.1  376.50  4994.7  375.70
  5001.3  375.70  5001.9  376.50  5019.7  378.10  5025.4  376.54  5041.5  377.32
  5054.3  378.61  5069.0  381.24  5096.5  383.19  5150.3  385.36  5191.7  386.21
  5307.2  387.94  5475.5  388.81  5524.7  388.61  5616.1  389.39  5719.1  389.44
#Mann=8,-1,0
  4145.4    0.05       0  4641.0     0.1       0  4820.3    0.07       0
  4994.1    0.07       0  5001.9    0.07       0  5054.3    0.12       0
  5096.5     0.1       0  5191.7    0.05       0
Bank Sta=4994.1,5001.9
Exp/Cntr=0.3,0.1

Type RM Length L Ch R = 1,8104,533,533,533
BEGIN DESCRIPTION:
UNT 052 in RCW 13.0
END DESCRIPTION:
XS GIS Cut Line= 3
      2044850.42     13434018.49      2045433.78     13433567.08
      2045746.27     13433122.66
#Sta/Elev= 30
  4262.7  386.41  4354.5  386.18  4396.1  386.55  4560.0  385.75  4609.9  385.99
  4682.3  385.31  4703.1  384.66  4782.0  383.51  4831.6  381.61  4860.6  380.93
  4931.2  379.91  4945.7  380.57  4960.2  380.32  4981.0  379.33  4985.2  378.65
  4985.8  377.85  4992.6  377.85  4993.3  378.65  5004.6  378.79  5016.2  379.49
  5060.6  380.01  5096.3  381.20  5125.1  381.58  5182.5  383.45  5236.1  384.62
  5254.0  385.35  5325.4  386.34  5411.7  385.87  5426.5  386.24  5543.6  385.50
#Mann=5,-1,0
  4262.7    0.05       0  4782.0     0.1       0  4985.2    0.07       0
  4993.3     0.1       0  5236.1    0.05       0
Bank Sta=4985.2,4993.3
Exp/Cntr=0.3,0.1

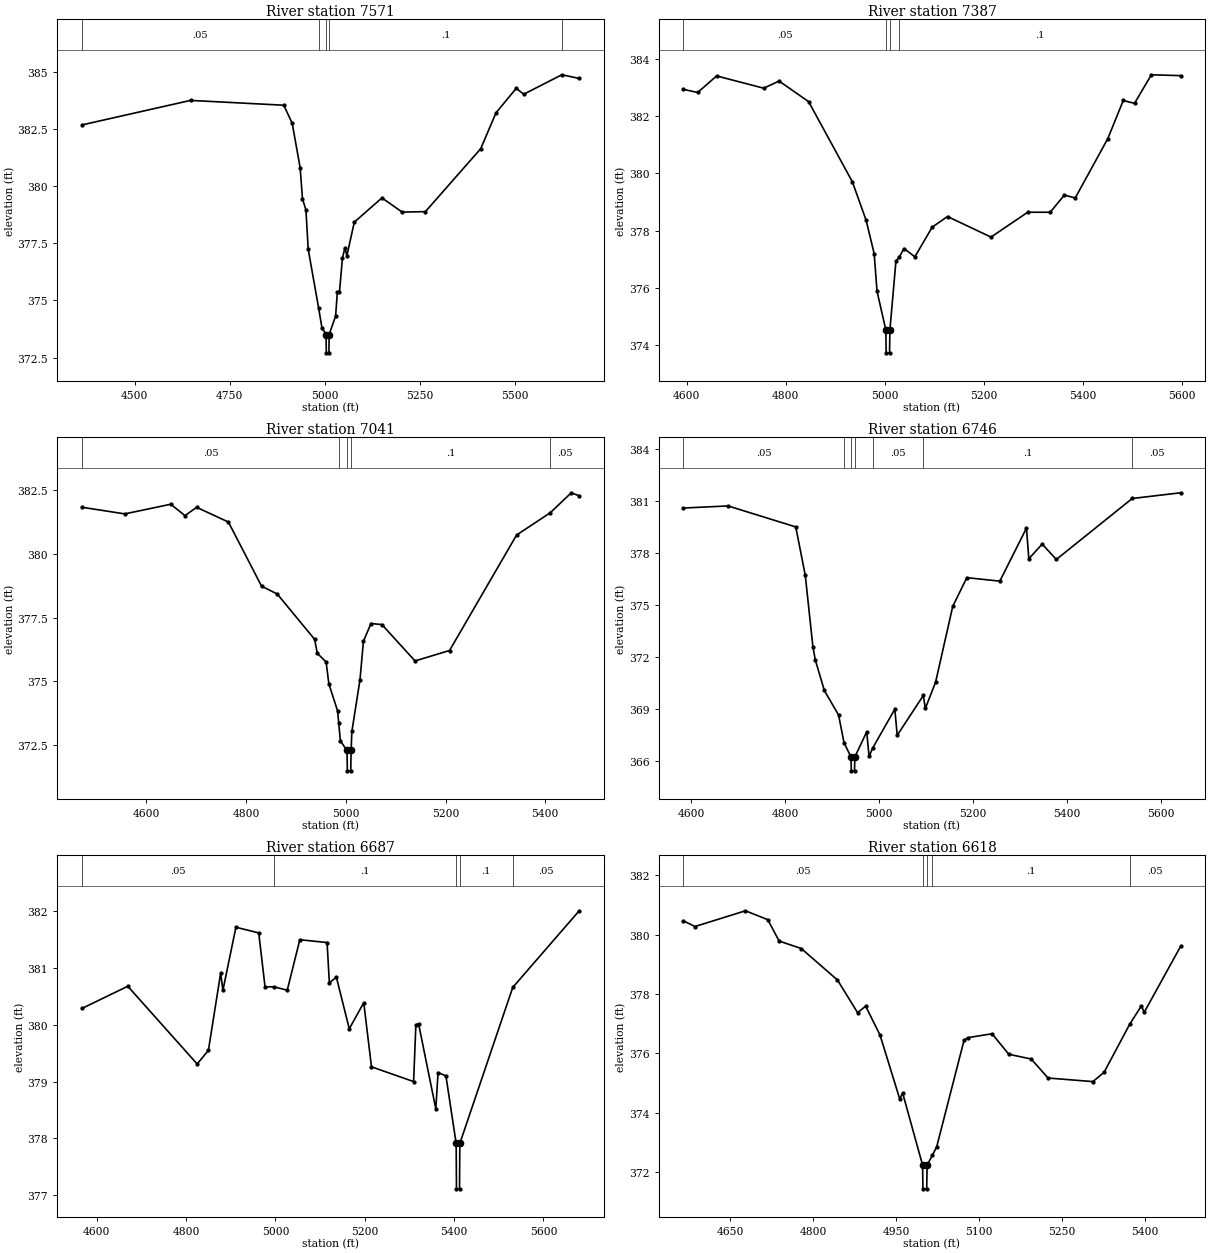
Type RM Length L Ch R = 1,7571,184,184,184
BEGIN DESCRIPTION:
UNT 052 in RCW 12.0
END DESCRIPTION:
XS GIS Cut Line= 3
      2045352.17     13434537.58      2045725.00     13433975.00
      2045899.06     13433365.68
#Sta/Elev= 30
  4361.2  382.67  4646.6  383.74  4892.1  383.53  4914.3  382.74  4935.3  380.79
  4941.3  379.44  4950.4  378.96  4956.4  377.24  4983.9  374.66  4992.5  373.81
  5003.4  373.51  5004.1  372.71  5010.9  372.71  5011.6  373.51  5028.6  374.32
  5033.1  375.36  5038.7  375.36  5046.5  376.85  5053.0  377.30  5058.2  376.95
  5077.7  378.42  5150.5  379.48  5203.8  378.86  5264.9  378.88  5410.5  381.63
  5450.8  383.20  5504.1  384.27  5523.6  384.01  5624.0  384.86  5669.8  384.70
#Mann=5,-1,0
  4361.2    0.05       0  4983.9     0.1       0  5003.4    0.07       0
  5011.6     0.1       0  5624.0    0.05       0
Bank Sta=5003.4,5011.6
Exp/Cntr=0.3,0.1

Type RM Length L Ch R = 1,7387,346,346,346
BEGIN DESCRIPTION:
Mapping XS 657ca5a2
END DESCRIPTION:
XS GIS Cut Line= 2
      2045677.70     13434437.75      2046150.42     13433553.03
#Sta/Elev= 30
  4593.8  382.94  4622.6  382.83  4660.8  383.41  4755.7  382.98  4786.8  383.23
  4846.4  382.51  4934.8  379.70  4962.4  378.36  4978.7  377.19  4984.4  375.88
  5002.2  374.52  5002.9  373.72  5009.7  373.72  5010.4  374.52  5022.6  376.93
  5028.9  377.06  5038.9  377.37  5060.8  377.08  5095.8  378.12  5126.7  378.49
  5214.4  377.77  5288.5  378.64  5333.9  378.64  5362.4  379.24  5384.4  379.14
  5450.2  381.22  5481.3  382.55  5504.0  382.45  5538.0  383.45  5596.9  383.42
#Mann=4,-1,0
  4593.8    0.05       0  5002.2    0.03       0  5010.4    0.05       0
  5028.9     0.1       0
Bank Sta=5002.2,5010.4
Exp/Cntr=0.3,0.1

Type RM Length L Ch R = 1,7041,295,295,295
BEGIN DESCRIPTION:
Mapping XS 5d60d87e
END DESCRIPTION:
XS GIS Cut Line= 3
      2045977.18     13434633.07      2046311.69     13433892.36
      2046353.12     13433712.62
#Sta/Elev= 30
  4470.9  381.84  4556.6  381.58  4648.8  381.96  4677.4  381.51  4700.6  381.84
  4764.4  381.26  4830.9  378.74  4862.4  378.43  4937.3  376.65  4942.7  376.10
  4960.4  375.76  4965.9  374.90  4983.5  373.83  4985.7  373.36  4989.0  372.66
  5002.3  372.28  5003.0  371.48  5009.8  371.48  5010.5  372.28  5012.1  373.03
  5028.4  375.07  5035.2  376.57  5050.3  377.27  5072.3  377.23  5138.7  375.80
  5208.0  376.21  5342.5  380.75  5409.7  381.62  5452.2  382.41  5468.1  382.29
#Mann=5,-1,0
  4470.9    0.05       0  4985.7     0.1       0  5002.3    0.07       0
  5010.5     0.1       0  5409.7    0.05       0
Bank Sta=5002.3,5010.5
Exp/Cntr=0.3,0.1

Type RM Length L Ch R = 1,6746,59,59,59
BEGIN DESCRIPTION:
Mapping XS b0b401a2
END DESCRIPTION:
XS GIS Cut Line= 5
      2046382.31     13434757.39      2046437.86     13434533.46
      2046385.77     13434231.38      2046356.18     13433866.35
      2046385.95     13433713.50
#Sta/Elev= 30
  4583.5  380.62  4678.7  380.74  4822.8  379.53  4843.1  376.74  4859.4  372.60
  4864.5  371.85  4883.7  370.09  4914.1  368.67  4925.6  367.08  4940.5  366.25
  4941.2  365.45  4948.0  365.45  4948.7  366.25  4974.0  367.70  4979.1  366.28
  4986.8  366.77  5033.9  369.01  5039.0  367.50  5094.6  369.80  5098.9  369.05
  5120.8  370.57  5157.3  374.94  5187.3  376.60  5257.6  376.40  5314.4  379.46
  5319.4  377.69  5347.9  378.54  5378.0  377.65  5539.7  381.17  5642.7  381.50
#Mann=7,-1,0
  4583.5    0.05       0  4925.6     0.1       0  4940.5   0.033       0
  4948.7     0.1       0  4986.8    0.05       0  5094.6     0.1       0
  5539.7    0.05       0
Bank Sta=4940.5,4948.7
Exp/Cntr=0.3,0.1

Type RM Length L Ch R = 1,6687,69,69,69
BEGIN DESCRIPTION:
Mapping XS be2565e8
END DESCRIPTION:
XS GIS Cut Line= 4
      2046413.54     13434778.29      2046491.68     13434484.85
      2046367.82     13433899.50      2046409.57     13433692.65
#Sta/Elev= 30
  4567.1  380.29  4669.4  380.68  4824.7  379.31  4849.9  379.55  4877.3  380.91
  4882.4  380.61  4911.5  381.72  4962.6  381.62  4976.7  380.67  4997.1  380.67
  5026.4  380.61  5054.6  381.50  5115.6  381.45  5120.7  380.74  5136.4  380.84
  5165.3  379.93  5197.7  380.39  5215.0  379.26  5309.3  379.00  5314.4  380.00
  5320.4  380.02  5359.0  378.52  5364.1  379.16  5381.7  379.10  5404.6  377.91
  5405.3  377.11  5412.1  377.11  5412.8  377.91  5531.3  380.66  5680.1  382.01
#Mann=5,-1,0
  4567.1    0.05       0  4997.1     0.1       0  5404.6    0.07       0
  5412.8     0.1       0  5531.3    0.05       0
Bank Sta=5404.6,5412.8
Exp/Cntr=0.3,0.1

Type RM Length L Ch R = 1,6618,295,295,295
BEGIN DESCRIPTION:
Mapping XS 12bc3fc7
END DESCRIPTION:
XS GIS Cut Line= 3
      2046503.82     13434795.65      2046554.18     13434497.00
      2046458.96     13433908.41
#Sta/Elev= 30
  4565.5  380.46  4586.4  380.27  4677.7  380.80  4718.1  380.50  4738.6  379.78
  4778.6  379.53  4844.1  378.47  4880.5  377.37  4895.1  377.59  4921.0  376.62
  4956.8  374.46  4961.9  374.67  4998.0  372.24  4998.7  371.44  5005.5  371.44
  5006.2  372.24  5015.8  372.57  5023.6  372.86  5073.0  376.44  5080.2  376.53
  5123.6  376.66  5154.0  375.97  5194.5  375.81  5224.9  375.17  5306.0  375.05
  5326.2  375.36  5372.6  376.98  5393.8  377.60  5398.8  377.38  5464.6  379.60
#Mann=5,-1,0
  4565.5    0.05       0  4998.0    0.03       0  5006.2    0.05       0
  5015.8     0.1       0  5372.6    0.05       0
Bank Sta=4998,5006.2
Exp/Cntr=0.3,0.1

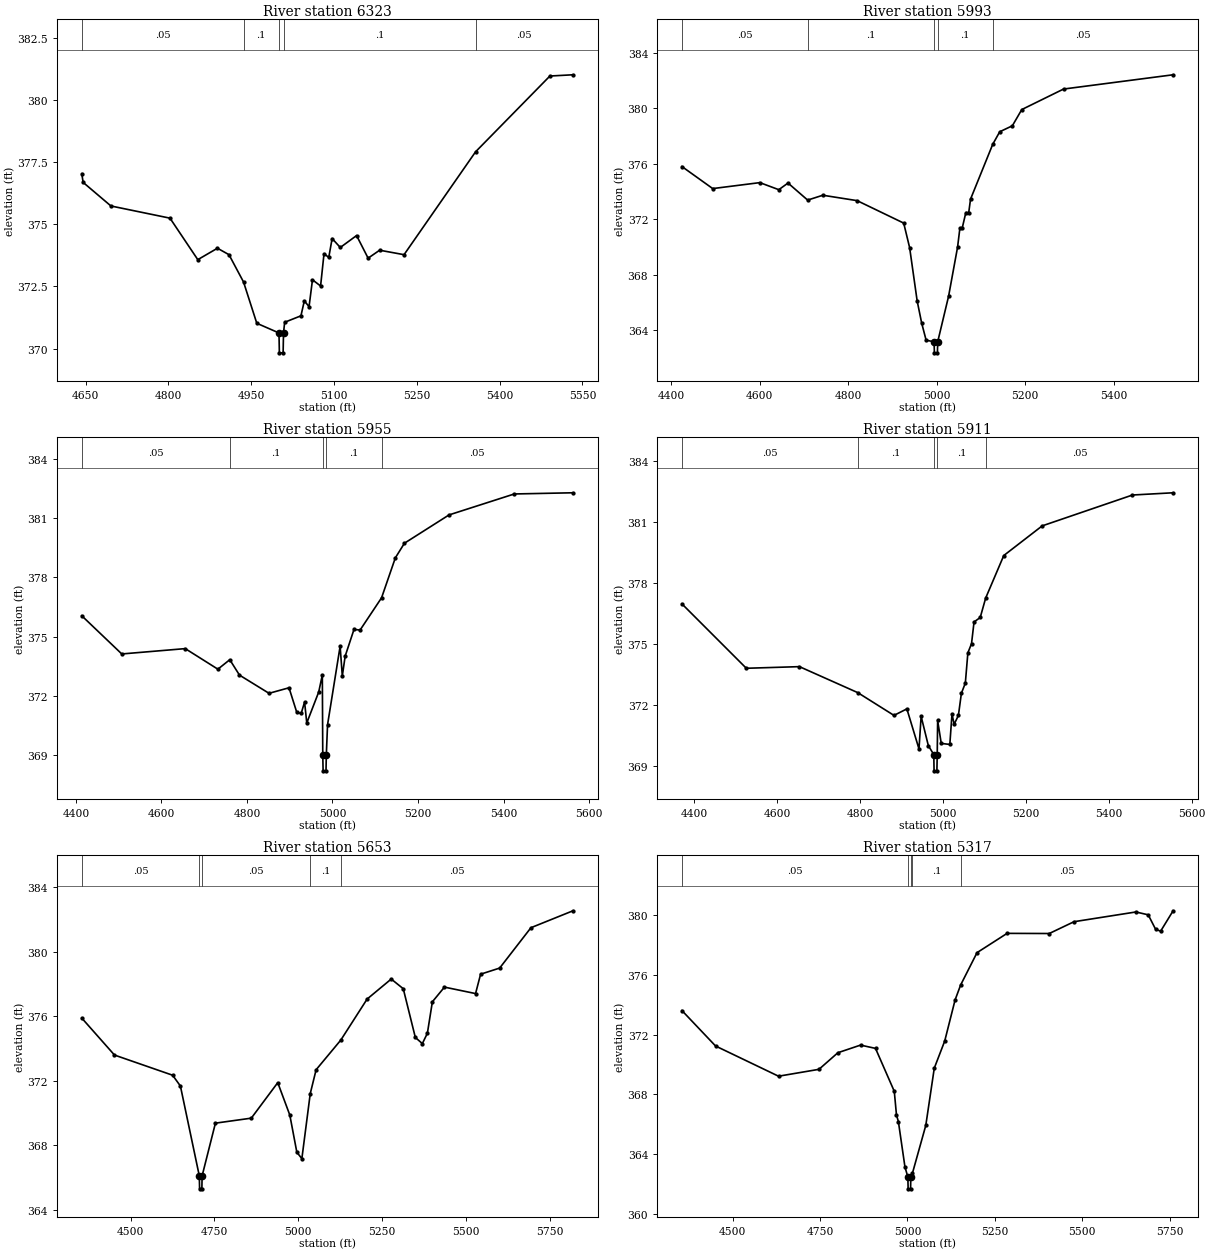
Type RM Length L Ch R = 1,6323,330,330,330
BEGIN DESCRIPTION:
Mapping XS 4fd675b3
END DESCRIPTION:
XS GIS Cut Line= 2
      2046962.42     13434550.56      2046445.94     13433825.76
#Sta/Elev= 30
  4642.9  377.04  4645.3  376.69  4695.7  375.74  4802.7  375.25  4853.1  373.58
  4888.7  374.04  4909.6  373.78  4936.0  372.68  4960.0  371.02  5000.2  370.63
  5000.9  369.83  5007.7  369.83  5008.4  370.63  5010.5  371.06  5040.0  371.32
  5046.1  371.92  5054.7  371.69  5060.9  372.77  5075.6  372.52  5081.8  373.82
  5090.4  373.67  5096.5  374.43  5111.3  374.07  5140.8  374.55  5161.7  373.64
  5182.6  373.96  5226.8  373.78  5356.4  377.92  5491.1  380.97  5532.9  381.02
#Mann=5,-1,0
  4642.9    0.05       0  4936.0     0.1       0  5000.2    0.07       0
  5008.4     0.1       0  5356.4    0.05       0
Bank Sta=5000.2,5008.4
Exp/Cntr=0.3,0.1

Type RM Length L Ch R = 1,5993,38,38,38
BEGIN DESCRIPTION:
Mapping XS df9d1ad9
END DESCRIPTION:
XS GIS Cut Line= 4
      2047064.89     13434413.46      2046850.02     13434231.14
      2046787.08     13433873.06      2046392.09     13433627.82
#Sta/Elev= 30
  4424.2  375.79  4493.8  374.20  4600.3  374.63  4643.2  374.12  4664.0  374.60
  4708.4  373.37  4742.7  373.72  4820.2  373.33  4925.5  371.71  4938.9  369.94
  4955.9  366.10  4966.1  364.50  4976.2  363.26  4994.1  363.15  4994.9  362.35
  5001.7  362.35  5002.4  363.15  5027.0  366.44  5047.3  369.98  5052.5  371.34
  5057.6  371.33  5066.0  372.47  5072.5  372.47  5076.6  373.44  5126.7  377.39
  5142.6  378.30  5171.1  378.73  5192.4  379.90  5286.8  381.38  5534.5  382.41
#Mann=5,-1,0
  4424.2    0.05       0  4708.4     0.1       0  4994.1    0.07       0
  5002.4     0.1       0  5126.7    0.05       0
Bank Sta=4994.1,5002.4
Exp/Cntr=0.3,0.1

Type RM Length L Ch R = 1,5955,44,44,44
BEGIN DESCRIPTION:
Mapping XS c215714f
END DESCRIPTION:
XS GIS Cut Line= 4
      2047085.69     13434416.47      2046901.67     13434225.50
      2046804.44     13433829.66      2046399.40     13433580.41
#Sta/Elev= 30
  4413.9  376.06  4507.4  374.13  4655.8  374.40  4732.1  373.36  4759.9  373.84
  4782.6  373.06  4851.7  372.14  4898.4  372.42  4916.5  371.18  4926.8  371.12
  4934.8  371.70  4939.9  370.64  4967.9  372.21  4976.3  373.07  4977.3  369.02
  4978.1  368.22  4984.9  368.22  4985.6  369.02  4988.5  370.55  5017.9  374.52
  5023.0  373.02  5029.7  374.02  5050.3  375.37  5064.6  375.34  5114.8  376.97
  5147.0  378.99  5168.3  379.73  5272.5  381.16  5425.1  382.22  5562.3  382.28
#Mann=5,-1,0
  4413.9    0.05       0  4759.9     0.1       0  4977.3    0.07       0
  4985.6     0.1       0  5114.8    0.05       0
Bank Sta=4977.3,4985.6
Exp/Cntr=0.3,0.1

Type RM Length L Ch R = 1,5911,258,258,258
BEGIN DESCRIPTION:
Mapping XS f77342c1
END DESCRIPTION:
XS GIS Cut Line= 4
      2047158.14     13434400.38      2046949.84     13434226.80
      2046843.51     13433836.17      2046424.70     13433547.56
#Sta/Elev= 30
  4370.7  376.96  4526.0  373.79  4654.1  373.87  4794.8  372.59  4882.1  371.47
  4913.2  371.79  4942.4  369.82  4947.6  371.42  4965.0  369.98  4978.1  369.54
  4978.8  368.74  4985.6  368.74  4986.4  369.54  4987.4  371.22  4996.1  370.09
  5016.8  370.04  5022.0  371.54  5027.2  371.03  5037.5  371.47  5044.7  372.56
  5054.2  373.06  5060.3  374.55  5069.1  375.00  5075.2  376.07  5090.1  376.29
  5103.3  377.25  5146.9  379.34  5239.5  380.80  5457.3  382.32  5555.3  382.43
#Mann=5,-1,0
  4370.7    0.05       0  4794.8     0.1       0  4978.1    0.07       0
  4986.4     0.1       0  5103.3    0.05       0
Bank Sta=4978.1,4986.4
Exp/Cntr=0.3,0.1

Type RM Length L Ch R = 1,5653,336,336,336
BEGIN DESCRIPTION:
Mapping XS 273bf0a5
END DESCRIPTION:
XS GIS Cut Line= 3
      2047399.92     13434308.80      2047202.01     13433866.12
      2046391.26     13433315.78
#Sta/Elev= 30
  4354.7  375.88  4452.2  373.59  4625.6  372.34  4648.8  371.67  4705.2  366.10
  4706.0  365.30  4712.8  365.30  4713.5  366.10  4753.2  369.37  4860.2  369.68
  4939.1  371.88  4975.1  369.87  4996.0  367.57  5011.0  367.17  5036.0  371.20
  5053.5  372.68  5127.2  374.52  5205.6  377.06  5277.5  378.30  5313.4  377.70
  5349.4  374.68  5370.3  374.30  5385.3  374.94  5400.2  376.89  5436.2  377.80
  5529.0  377.40  5544.0  378.60  5600.9  378.98  5694.1  381.48  5819.5  382.53
#Mann=5,-1,0
  4354.7    0.05       0  4705.2    0.03       0  4713.5    0.05       0
  5036.0     0.1       0  5127.2    0.05       0
Bank Sta=4705.2,4713.5
Exp/Cntr=0.3,0.1

Type RM Length L Ch R = 1,5317,272,272,272
BEGIN DESCRIPTION:
Mapping XS e7784c2c
END DESCRIPTION:
XS GIS Cut Line= 4
      2047462.43     13434241.16      2047472.85     13433933.83
      2047207.22     13433261.95      2046932.88     13433006.71
#Sta/Elev= 30
  4355.0  373.61  4451.2  371.24  4631.3  369.22  4746.9  369.68  4801.0  370.79
  4865.8  371.30  4908.6  371.08  4962.3  368.21  4968.6  366.62  4974.0  366.19
  4992.9  363.14  5001.1  362.49  5001.9  361.69  5008.9  361.69  5009.6  362.49
  5014.3  362.74  5052.4  365.93  5076.7  369.76  5106.5  371.57  5136.2  374.32
  5152.1  375.32  5198.9  377.48  5284.9  378.77  5405.5  378.76  5476.4  379.55
  5653.2  380.20  5688.5  380.01  5709.9  379.03  5724.1  378.92  5759.7  380.28
#Mann=5,-1,0
  4355.0    0.05       0  5001.1    0.03       0  5009.6    0.05       0
  5014.3     0.1       0  5152.1    0.05       0
Bank Sta=5001.1,5009.6
Exp/Cntr=0.3,0.1

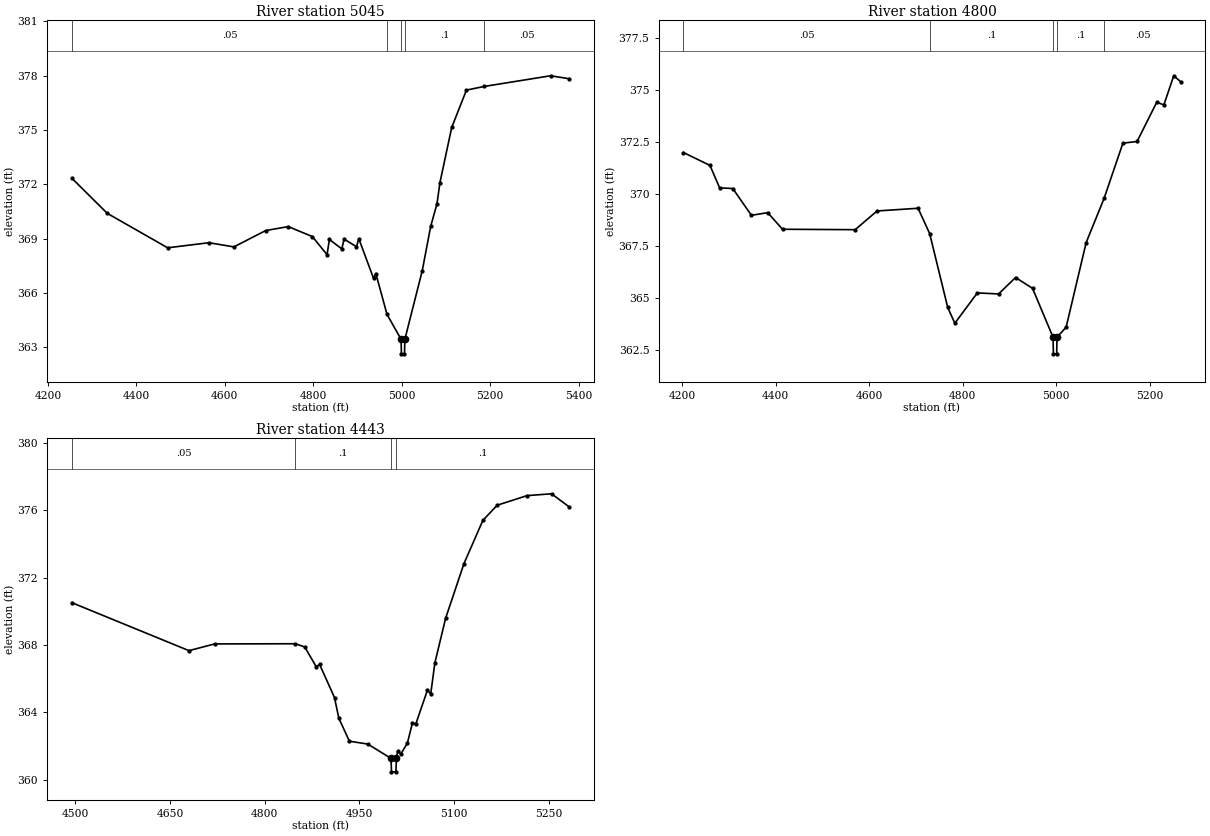
Type RM Length L Ch R = 1,5045,245,245,245
BEGIN DESCRIPTION:
UNT 052 in RCW 9.0
END DESCRIPTION:
XS GIS Cut Line= 3
      2047524.50     13434213.35      2047639.51     13433681.66
      2047475.01     13433125.05
#Sta/Elev= 30
  4254.0  372.34  4334.2  370.40  4470.7  368.50  4564.1  368.78  4620.6  368.55
  4692.3  369.45  4743.4  369.67  4798.0  369.12  4831.3  368.12  4836.5  368.96
  4864.6  368.44  4869.8  368.98  4897.8  368.56  4903.1  369.00  4936.3  366.82
  4941.6  367.08  4966.8  364.83  4998.7  363.45  4999.4  362.65  5006.4  362.65
  5007.2  363.45  5046.6  367.24  5065.6  369.68  5079.9  370.93  5086.5  372.09
  5113.2  375.14  5146.5  377.20  5186.4  377.40  5336.7  377.99  5378.4  377.83
#Mann=5,-1,0
  4254.0    0.05       0  4966.8     0.1       0  4998.7    0.07       0
  5007.2     0.1       0  5186.4    0.05       0
Bank Sta=4998.7,5007.2
Exp/Cntr=0.3,0.1

Type RM Length L Ch R = 1,4800,357,357,357
BEGIN DESCRIPTION:
Mapping XS 57e81f83
END DESCRIPTION:
XS GIS Cut Line= 3
      2047541.87     13434219.81      2047680.75     13433705.53
      2047968.87     13433259.26
#Sta/Elev= 30
  4202.5  371.99  4259.3  371.37  4280.0  370.29  4308.1  370.26  4348.0  368.97
  4382.8  369.10  4414.6  368.30  4570.0  368.28  4616.9  369.18  4704.7  369.31
  4729.5  368.09  4768.1  364.54  4783.3  363.78  4831.5  365.24  4877.0  365.19
  4913.3  365.98  4949.6  365.46  4993.5  363.11  4994.3  362.31  5001.3  362.31
  5002.0  363.11  5021.5  363.59  5064.4  367.66  5103.0  369.80  5143.0  372.44
  5173.3  372.52  5215.5  374.41  5230.7  374.28  5251.8  375.68  5266.4  375.40
#Mann=5,-1,0
  4202.5    0.05       0  4729.5     0.1       0  4993.5    0.07       0
  5002.0     0.1       0  5103.0    0.05       0
Bank Sta=4993.5,5002
Exp/Cntr=0.3,0.1

Type RM Length L Ch R = 1,4443,172,172,172
BEGIN DESCRIPTION:
Mapping XS 5f7e8639
END DESCRIPTION:
XS GIS Cut Line= 3
      2047583.10     13434169.90      2047678.58     13433900.84
      2048140.40     13433703.54
#Sta/Elev= 30
  4494.6  370.52  4680.2  367.67  4720.9  368.07  4848.8  368.08  4863.6  367.89
  4881.8  366.72  4887.2  366.85  4910.8  364.88  4917.6  363.66  4934.4  362.29
  4963.5  362.12  5000.3  361.27  5001.1  360.47  5008.1  360.47  5008.9  361.27
  5010.7  361.68  5016.1  361.54  5026.3  362.18  5034.3  363.38  5039.7  363.32
  5057.9  365.31  5063.3  365.11  5069.8  366.94  5086.9  369.60  5115.9  372.84
  5145.9  375.41  5168.6  376.31  5215.8  376.88  5254.7  376.99  5282.3  376.22
#Mann=4,-1,0
  4494.6    0.05       0  4848.8     0.1       0  5000.3    0.07       0
  5008.9     0.1       0
Bank Sta=5000.3,5008.9
Exp/Cntr=0.3,0.1