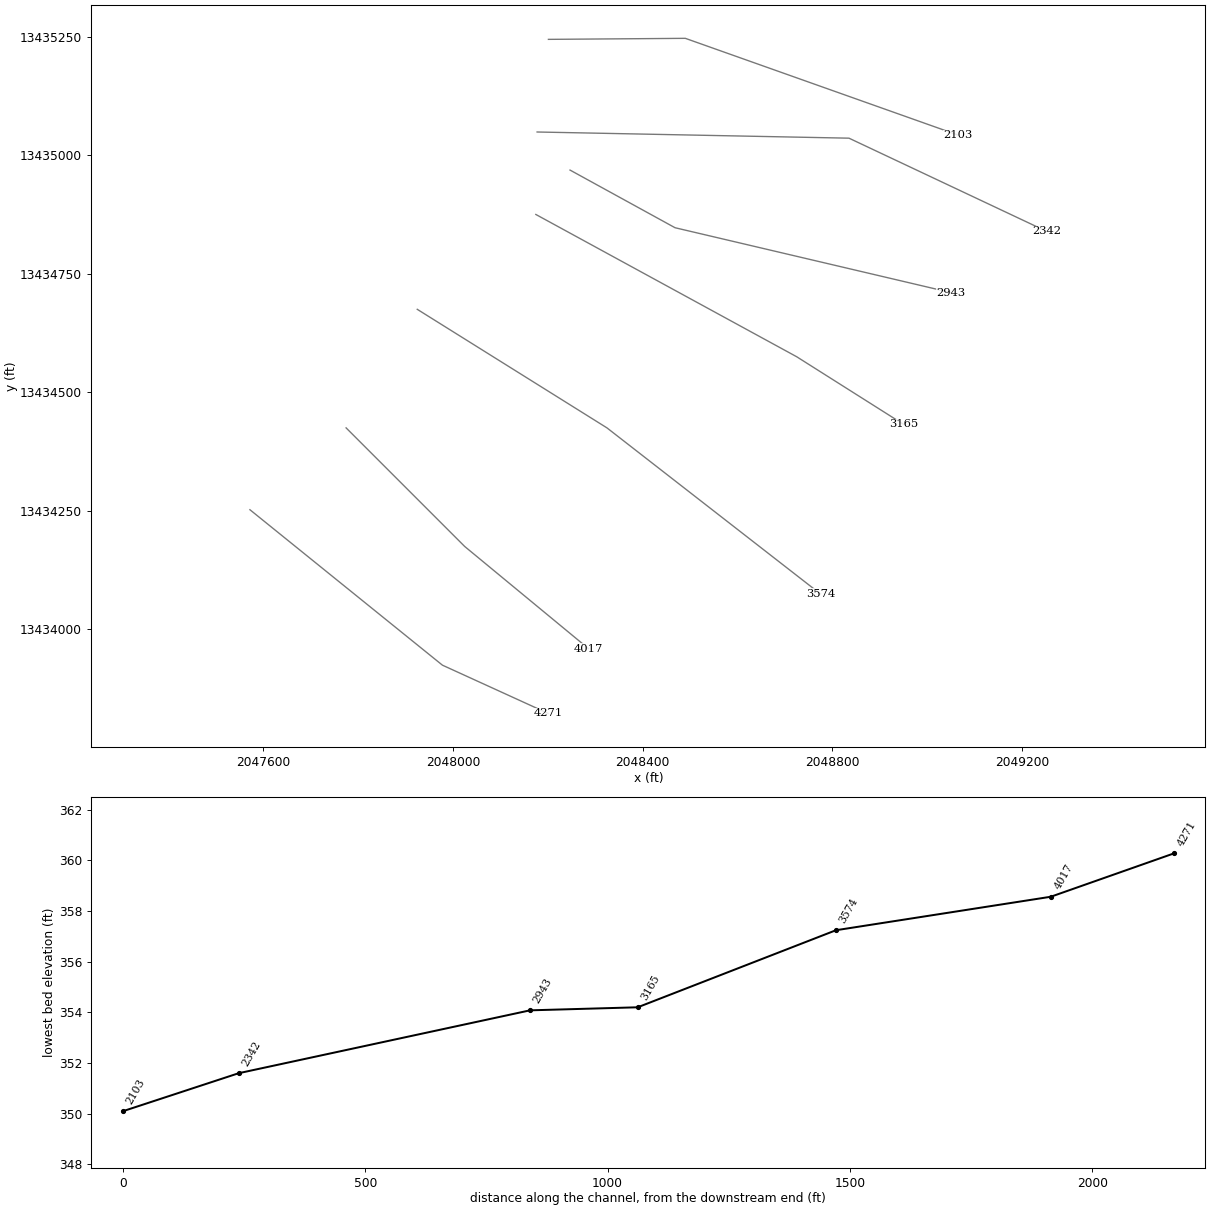
HEC-RAS study UNT 052 in RCW.prj: UNT 052 in RCW Base Level Engineering

--- UNT 052 in RCW.g01 (geometry) --- (continued)

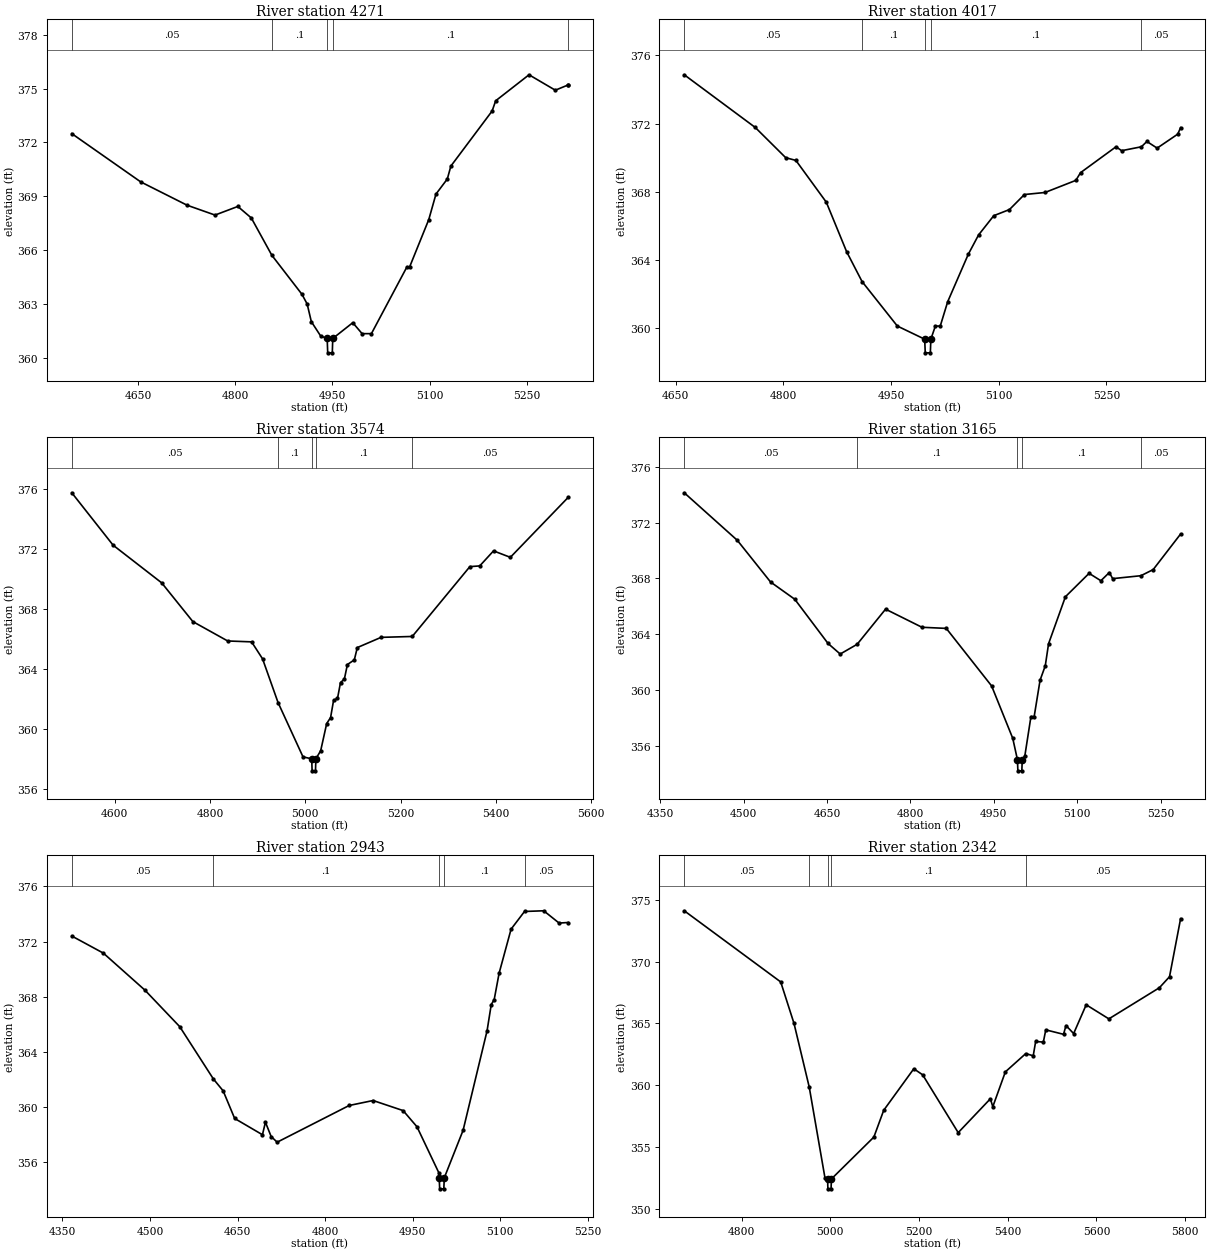
Type RM Length L Ch R = 1,4271,254,254,254
BEGIN DESCRIPTION:
UNT 052 in RCW 8.0
END DESCRIPTION:
XS GIS Cut Line= 3
      2047572.21     13434252.43      2047978.06     13433924.71
      2048200.82     13433823.06
#Sta/Elev= 30
  4547.4  372.49  4653.8  369.80  4725.4  368.50  4768.6  367.95  4803.8  368.43
  4824.6  367.79  4856.3  365.71  4902.9  363.53  4910.9  362.99  4917.3  362.01
  4931.7  361.21  4941.8  361.07  4942.6  360.27  4949.7  360.27  4950.4  361.07
  4981.3  361.95  4995.7  361.34  5010.1  361.34  5064.8  365.05  5069.0  365.05
  5098.7  367.70  5109.8  369.12  5127.3  369.96  5132.8  370.68  5196.5  373.75
  5202.0  374.32  5253.5  375.77  5294.1  374.91  5313.7  375.20  5313.9  375.20
#Mann=5,-1,0
  4547.4    0.05       0  4856.3     0.1       0  4941.8    0.07       0
  4950.4     0.1       0  5313.7    0.05       0
Bank Sta=4941.8,4950.4
Exp/Cntr=0.3,0.1

Type RM Length L Ch R = 1,4017,443,443,443
BEGIN DESCRIPTION:
UNT 052 in RCW 7.0
END DESCRIPTION:
XS GIS Cut Line= 3
      2047774.98     13434425.02      2048025.00     13434175.00
      2048285.86     13433959.73
#Sta/Elev= 30
  4661.7  374.86  4760.7  371.77  4803.1  370.00  4817.3  369.84  4859.7  367.39
  4888.0  364.49  4909.5  362.74  4958.7  360.13  4996.8  359.36  4997.6  358.56
  5004.7  358.56  5005.4  359.36  5011.7  360.13  5018.5  360.13  5028.9  361.56
  5057.6  364.34  5071.9  365.47  5093.1  366.60  5115.0  366.96  5135.8  367.84
  5164.5  367.96  5207.5  368.67  5214.0  369.12  5263.5  370.64  5271.3  370.41
  5298.9  370.64  5306.5  370.95  5320.8  370.56  5349.5  371.38  5353.5  371.76
#Mann=5,-1,0
  4661.7    0.05       0  4909.5     0.1       0  4996.8    0.07       0
  5005.4     0.1       0  5298.9    0.05       0
Bank Sta=4996.8,5005.4
Exp/Cntr=0.3,0.1

Type RM Length L Ch R = 1,3574,409,409,409
BEGIN DESCRIPTION:
UNT 052 in RCW 6.0
END DESCRIPTION:
XS GIS Cut Line= 3
      2047924.99     13434675.00      2048325.00     13434425.00
      2048775.01     13434075.00
#Sta/Elev= 30
  4509.8  375.76  4596.5  372.27  4698.5  369.76  4763.9  367.18  4837.0  365.89
  4887.2  365.83  4910.2  364.70  4942.7  361.79  4995.1  358.17  5013.4  358.04
  5014.2  357.24  5021.3  357.24  5022.1  358.04  5032.2  358.58  5044.8  360.39
  5053.0  360.79  5059.3  361.94  5067.5  362.06  5073.8  363.12  5081.9  363.35
  5088.3  364.32  5102.8  364.63  5109.1  365.45  5158.9  366.13  5224.4  366.19
  5345.3  370.84  5366.1  370.89  5395.0  371.89  5430.3  371.46  5551.6  375.45
#Mann=5,-1,0
  4509.8    0.05       0  4942.7     0.1       0  5013.4    0.07       0
  5022.1     0.1       0  5224.4    0.05       0
Bank Sta=5013.4,5022.1
Exp/Cntr=0.3,0.1

Type RM Length L Ch R = 1,3165,222,222,222
BEGIN DESCRIPTION:
UNT 052 in RCW 5.0
END DESCRIPTION:
XS GIS Cut Line= 3
      2048175.04     13434874.98      2048725.00     13434575.00
      2048950.11     13434432.64
#Sta/Elev= 30
  4393.3  374.15  4488.7  370.74  4548.5  367.75  4592.1  366.51  4651.9  363.34
  4673.8  362.58  4704.3  363.28  4755.4  365.80  4820.9  364.50  4864.6  364.42
  4946.2  360.29  4984.2  356.53  4992.6  355.00  4993.4  354.20  5000.5  354.20
  5001.3  355.00  5006.0  355.29  5016.9  358.09  5022.7  358.09  5033.3  360.70
  5042.7  361.74  5048.6  363.32  5078.9  366.69  5121.5  368.37  5142.7  367.84
  5157.9  368.43  5163.9  367.99  5214.7  368.20  5236.8  368.64  5286.1  371.19
#Mann=5,-1,0
  4393.3    0.05       0  4704.3     0.1       0  4992.6    0.07       0
  5001.3     0.1       0  5214.7    0.05       0
Bank Sta=4992.6,5001.3
Exp/Cntr=0.3,0.1

Type RM Length L Ch R = 1,2943,601,601,601
BEGIN DESCRIPTION:
Mapping XS 8f6c1eeb
END DESCRIPTION:
XS GIS Cut Line= 3
      2048247.12     13434968.57      2048468.51     13434847.02
      2049050.09     13434710.31
#Sta/Elev= 30
  4366.2  372.40  4420.3  371.16  4491.4  368.48  4551.1  365.83  4608.7  362.04
  4625.4  361.18  4645.1  359.18  4692.7  358.00  4697.8  358.91  4707.6  357.87
  4717.9  357.46  4841.2  360.12  4882.2  360.48  4933.6  359.75  4957.3  358.58
  4994.6  355.26  4995.4  354.88  4996.2  354.08  5003.3  354.08  5004.1  354.88
  5036.3  358.32  5077.4  365.54  5084.5  367.43  5089.6  367.80  5098.0  369.71
  5118.5  372.90  5141.5  374.18  5174.4  374.23  5200.7  373.34  5216.2  373.38
#Mann=5,-1,0
  4366.2    0.05       0  4608.7     0.1       0  4995.4    0.07       0
  5004.1     0.1       0  5141.5    0.05       0
Bank Sta=4995.4,5004.1
Exp/Cntr=0.3,0.1

Type RM Length L Ch R = 1,2342,239,239,239
BEGIN DESCRIPTION:
UNT 052 in RCW 4.0
END DESCRIPTION:
XS GIS Cut Line= 3
      2048177.67     13435048.85      2048835.26     13435035.83
      2049252.31     13434839.19
#Sta/Elev= 30
  4670.8  374.11  4888.2  368.35  4918.2  364.99  4952.5  359.84  4988.2  352.44
  4993.8  352.40  4994.6  351.60  5001.7  351.60  5002.5  352.40  5098.2  355.79
  5120.4  357.96  5188.2  361.32  5208.2  360.83  5288.3  356.15  5360.8  358.89
  5366.3  358.25  5394.6  361.07  5440.6  362.55  5457.4  362.37  5462.9  363.53
  5480.2  363.48  5485.7  364.47  5525.7  364.11  5531.3  364.82  5548.5  364.17
  5576.8  366.50  5627.9  365.36  5741.8  367.88  5764.6  368.77  5789.6  373.47
#Mann=5,-1,0
  4670.8    0.05       0  4952.5     0.1       0  4993.8    0.07       0
  5002.5     0.1       0  5440.6    0.05       0
Bank Sta=4993.8,5002.5
Exp/Cntr=0.3,0.1

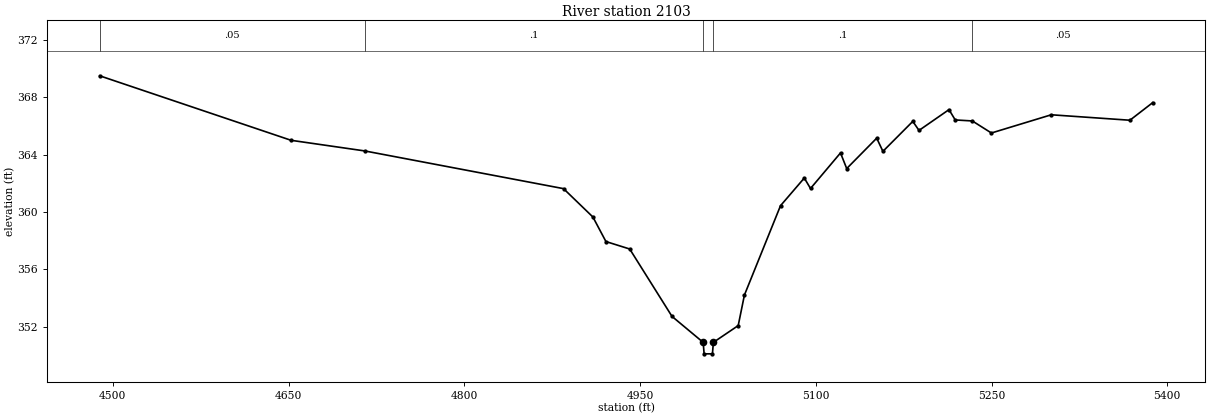
Type RM Length L Ch R = 1,2103,0,0,0
BEGIN DESCRIPTION:
Mapping XS a3f23a0f
END DESCRIPTION:
XS GIS Cut Line= 3
      2048201.58     13435244.16      2048490.21     13435246.33
      2049065.26     13435042.35
#Sta/Elev= 30
  4488.8  369.49  4652.2  364.99  4715.0  364.25  4884.7  361.62  4909.8  359.64
  4920.9  357.93  4941.2  357.41  4977.3  352.71  5003.9  350.90  5004.7  350.10
  5011.8  350.10  5012.6  350.90  5033.8  352.07  5039.1  354.20  5069.9  360.43
  5090.2  362.36  5095.5  361.63  5121.1  364.11  5126.4  363.02  5152.0  365.14
  5157.3  364.22  5182.8  366.31  5188.1  365.68  5213.7  367.13  5219.0  366.41
  5233.6  366.34  5249.9  365.50  5301.0  366.77  5368.1  366.39  5387.6  367.62
#Mann=5,-1,0
  4488.8    0.05       0  4715.0     0.1       0  5003.9    0.07       0
  5012.6     0.1       0  5233.6    0.05       0
Bank Sta=5003.9,5012.6
Exp/Cntr=0.3,0.1

Chan Stop Cuts=-1