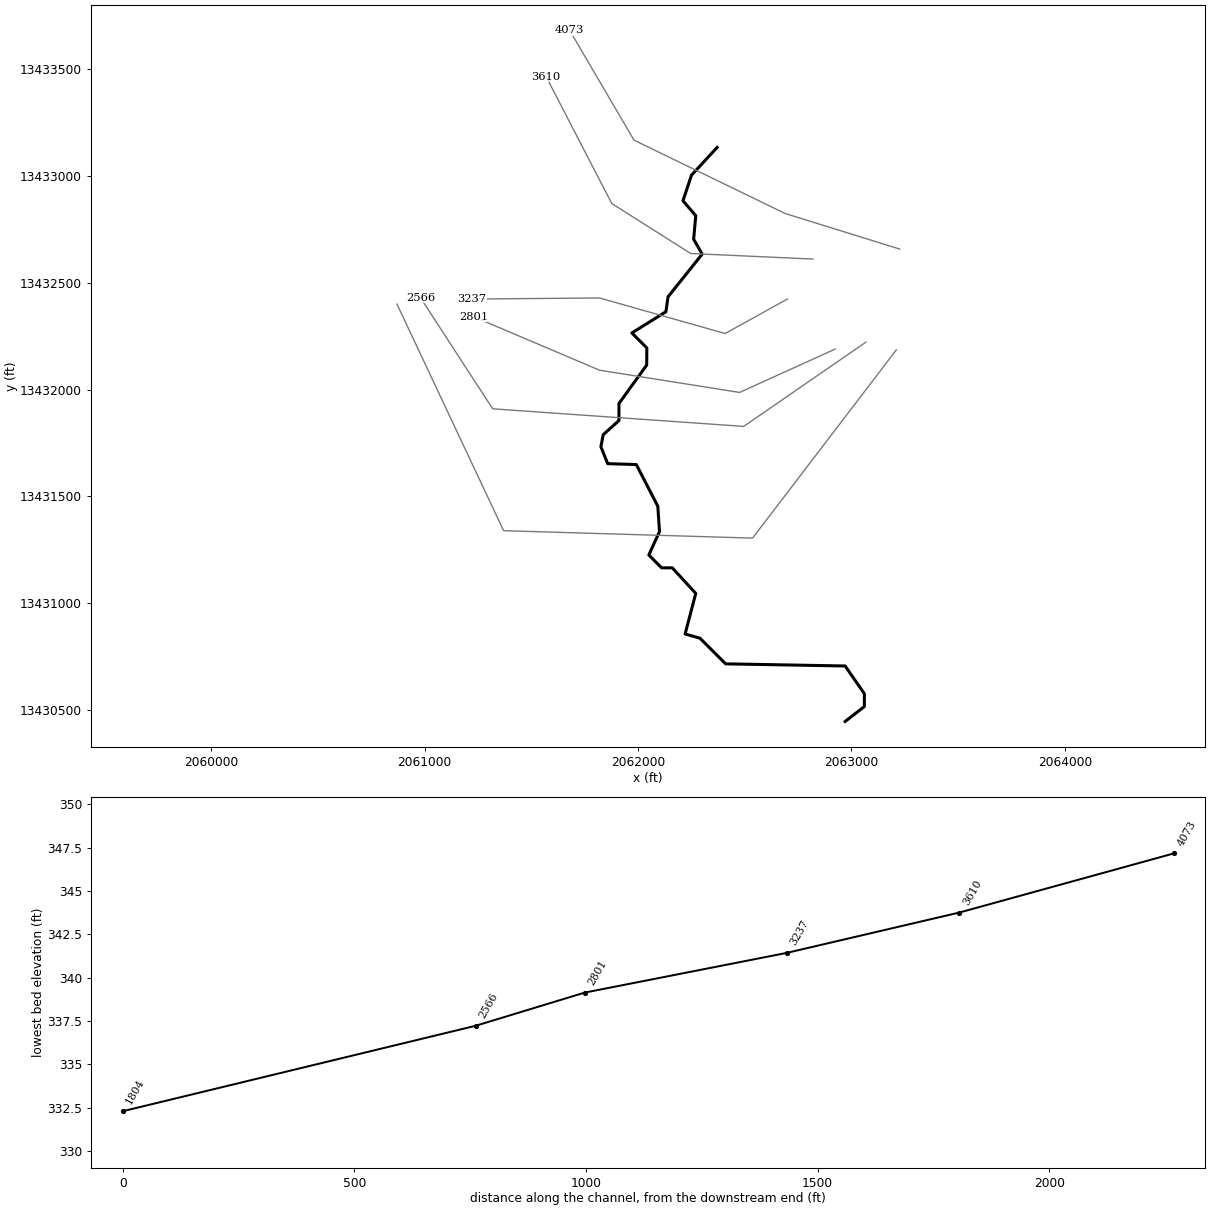
--- UNT 054 in RCW.prj (project) ---

Proj Title=UNT 054 in RCW Base Level Engineering
Current Plan=p01
Default Exp/Contr=0.3,0.1
English Units
Geom File=g01
Flow File=f01
Plan File=p01
BEGIN DESCRIPTION:
UNT 054 in RCW
END DESCRIPTION:

--- UNT 054 in RCW.p01 (plan) ---

Plan Title=Multiple Run
Short Identifier=Multiple
Geom File=g01
Flow File=f01
Subcritical Flow
K Sum by GR= 0
Std Step Tol= 0.01
Critical Tol= 0.01
Num of Std Step Trials= 20
Max Error Tol= 0.3
Flow Tol Ratio= 0.001
Split Flow NTrial= 30
Split Flow Tol= 0.02
Split Flow Ratio= 0.02
Log Output Level= 0
Friction Slope Method= 1
Unsteady Friction Slope Method= 2
Unsteady Bridges Friction Slope Method= 1
Parabolic Critical Depth
Global Vel Dist=  1 , 1 , 1
Global Log Level= 0
CheckData=True
Encroach Param= -1, 0, 0, 0
BEGIN DESCRIPTION:
Multiple Run
END DESCRIPTION:

--- UNT 054 in RCW.f01 (steady flow) ---

Flow Title=Multiple
Number of Profiles=7
Profile Names=10-year,25-year,50-year,1pct_min,100-year,1pct_plu,500-year
River Rch & RM= UNT 054 in RCW,Reach-1,4073
     144     196     238     145     289     577     433
River Rch & RM= UNT 054 in RCW,Reach-1,2566
     214     298     368     227     453     904     697
Boundary for River Rch & Prof#=UNT 054 in RCW,Reach-1,1
Up Type=0
Dn Type=3
Dn Slope=0.005
Boundary for River Rch & Prof#=UNT 054 in RCW,Reach-1,2
Up Type=0
Dn Type=3
Dn Slope=0.005
Boundary for River Rch & Prof#=UNT 054 in RCW,Reach-1,3
Up Type=0
Dn Type=3
Dn Slope=0.005
Boundary for River Rch & Prof#=UNT 054 in RCW,Reach-1,4
Up Type=0
Dn Type=3
Dn Slope=0.005
Boundary for River Rch & Prof#=UNT 054 in RCW,Reach-1,5
Up Type=0
Dn Type=3
Dn Slope=0.005
Boundary for River Rch & Prof#=UNT 054 in RCW,Reach-1,6
Up Type=0
Dn Type=3
Dn Slope=0.005
Boundary for River Rch & Prof#=UNT 054 in RCW,Reach-1,7
Up Type=0
Dn Type=3
Dn Slope=0.005

--- UNT 054 in RCW.g01 (geometry) ---

Geom Title=Existing Conditions

River Reach=UNT 054 in RCW,Reach-1
Reach XY= 30
      2062370.80     13433134.54      2062250.80     13433004.54
      2062210.80     13432884.54      2062270.80     13432814.54
      2062260.80     13432704.54      2062300.80     13432634.54
      2062140.80     13432434.54      2062130.80     13432364.54
      2061971.30     13432265.10      2062041.44     13432194.96
      2062040.80     13432114.54      2061910.80     13431934.54
      2061910.80     13431854.54      2061837.27     13431788.71
      2061826.16     13431731.77      2061858.11     13431652.60
      2061992.13     13431648.43      2062092.83     13431453.29
      2062100.80     13431334.54      2062050.80     13431224.54
      2062110.80     13431164.54      2062160.80     13431164.54
      2062270.80     13431044.54      2062220.80     13430854.54
      2062290.80     13430834.54      2062410.80     13430714.54
      2062970.80     13430704.54      2063060.80     13430574.54
      2063060.80     13430514.54      2062970.80     13430444.54

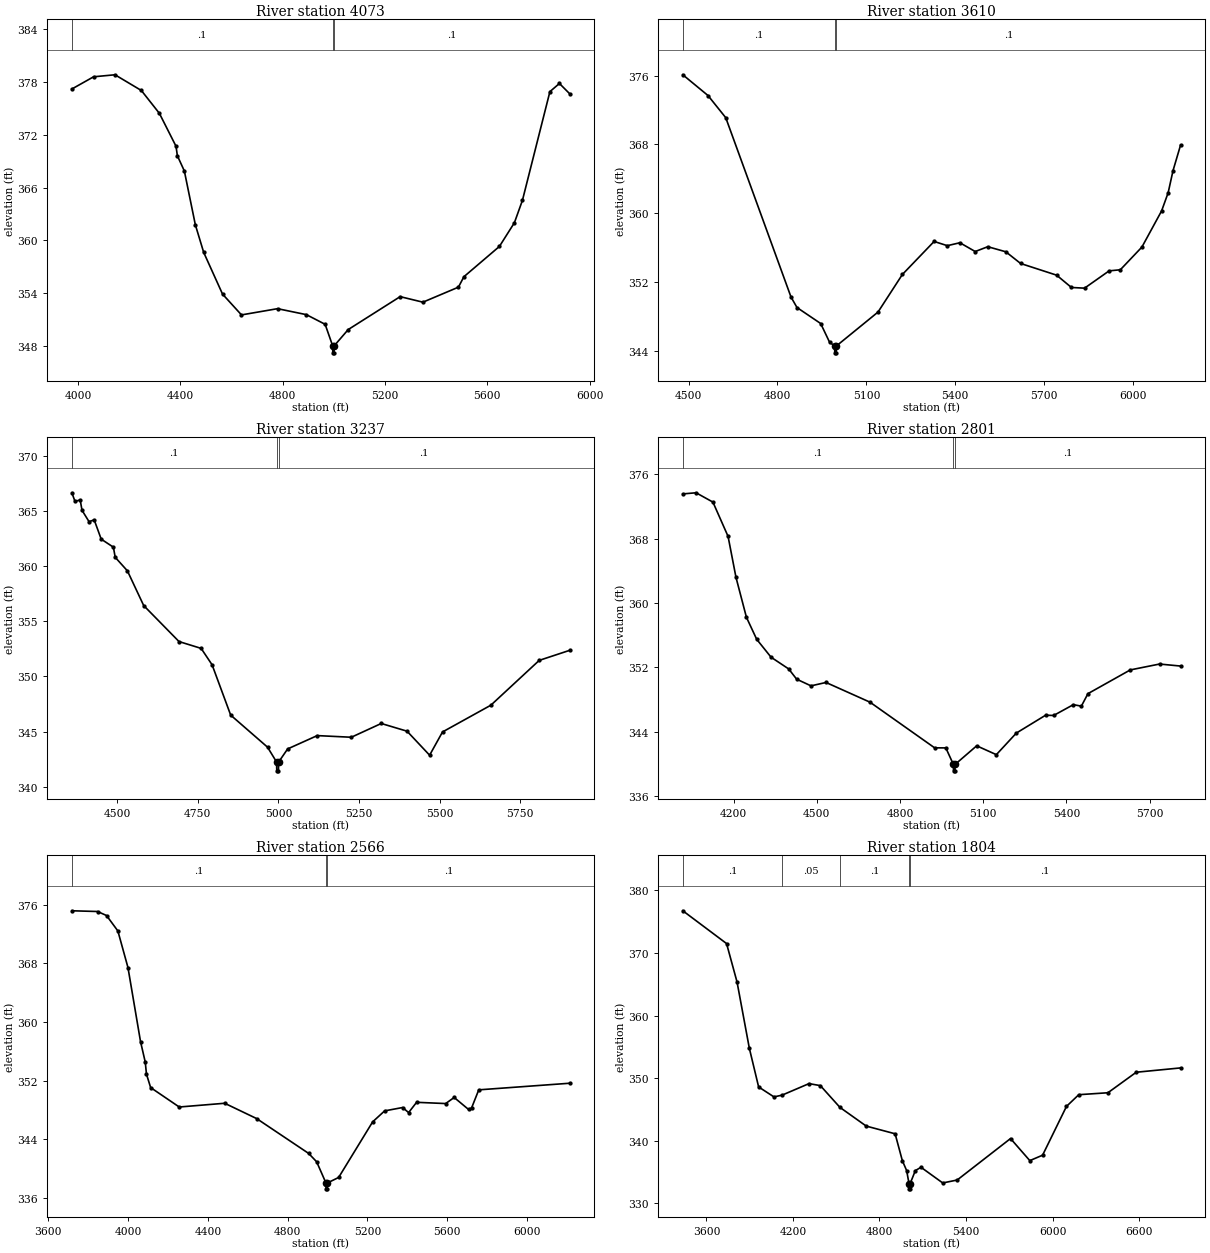
Type RM Length L Ch R = 1,4073,463,463,463
BEGIN DESCRIPTION:
Mapping XS 547f12a3
END DESCRIPTION:
XS GIS Cut Line= 4
      2063226.03     13432658.30      2062689.58     13432824.96
      2061981.25     13433168.71      2061679.56     13433683.66
#Sta/Elev= 30
  3975.5  377.22  4060.4  378.61  4144.1  378.84  4247.2  377.05  4317.6  374.45
  4382.7  370.70  4388.0  369.62  4415.3  367.88  4458.3  361.75  4490.9  358.61
  4564.6  353.86  4638.6  351.49  4779.6  352.20  4892.4  351.52  4965.7  350.42
  4995.1  347.97  4995.6  347.17  5000.6  347.17  5001.1  347.97  5055.9  349.82
  5259.0  353.57  5348.0  352.94  5486.8  354.65  5508.3  355.84  5647.1  359.29
  5705.7  361.99  5737.1  364.54  5844.5  376.92  5881.7  377.85  5921.4  376.69
#Mann=3,-1,0
  3975.5     0.1       0  4995.1    0.07       0  5001.1     0.1       0
Bank Sta=4995.1,5001.1
Exp/Cntr=0.3,0.1

Type RM Length L Ch R = 1,3610,373,373,373
BEGIN DESCRIPTION:
UNT 054 in RCW 16.0
END DESCRIPTION:
XS GIS Cut Line= 4
      2062819.76     13432611.42      2062246.87     13432637.46
      2061877.08     13432871.84      2061569.90     13433465.37
#Sta/Elev= 30
  4480.5  376.09  4565.4  373.68  4625.4  371.10  4845.6  350.25  4865.7  349.03
  4945.7  347.17  4975.8  344.99  4992.8  344.56  4993.3  343.76  4998.3  343.76
  4998.8  344.56  5139.2  348.50  5221.4  352.87  5328.5  356.71  5373.1  356.22
  5415.5  356.56  5467.2  355.54  5509.7  356.10  5570.5  355.51  5620.4  354.15
  5742.0  352.79  5791.9  351.36  5836.2  351.28  5919.1  353.29  5957.0  353.42
  6029.8  356.06  6096.2  360.26  6118.3  362.37  6134.8  364.95  6160.1  367.90
#Mann=3,-1,0
  4480.5     0.1       0  4992.8    0.07       0  4998.8     0.1       0
Bank Sta=4992.8,4998.8
Exp/Cntr=0.3,0.1

Type RM Length L Ch R = 1,3237,436,436,436
BEGIN DESCRIPTION:
UNT 054 in RCW 17.0
END DESCRIPTION:
XS GIS Cut Line= 4
      2062699.96     13432423.90      2062408.33     13432262.46
      2061819.79     13432429.13      2061220.83     13432423.92
#Sta/Elev= 30
  4359.2  366.68  4368.9  365.90  4385.0  366.03  4390.7  365.09  4412.4  364.06
  4428.5  364.22  4450.2  362.47  4488.0  361.74  4493.7  360.82  4531.5  359.59
  4582.0  356.44  4691.6  353.17  4760.2  352.55  4794.2  351.06  4851.9  346.49
  4966.2  343.58  4994.3  342.23  4994.8  341.43  5000.1  341.43  5000.6  342.23
  5028.6  343.42  5120.4  344.63  5226.1  344.48  5319.0  345.73  5399.0  345.03
  5469.0  342.85  5509.0  344.96  5659.0  347.39  5809.0  351.46  5903.2  352.37
#Mann=3,-1,0
  4359.2     0.1       0  4994.3    0.07       0  5000.6     0.1       0
Bank Sta=4994.3,5000.6
Exp/Cntr=0.3,0.1

Type RM Length L Ch R = 1,2801,235,235,235
BEGIN DESCRIPTION:
UNT 054 in RCW 18.0
END DESCRIPTION:
XS GIS Cut Line= 4
      2062923.92     13432189.53      2062476.04     13431986.42
      2061819.79     13432090.59      2061231.97     13432340.28
#Sta/Elev= 30
  4016.9  373.55  4064.7  373.69  4125.5  372.53  4180.1  368.27  4208.7  363.17
  4246.3  358.22  4283.4  355.48  4335.1  353.26  4398.8  351.80  4427.4  350.53
  4479.1  349.70  4533.3  350.12  4692.0  347.67  4924.9  342.00  4965.4  341.99
  4992.6  339.94  4993.1  339.14  4998.4  339.14  4998.9  339.94  5076.7  342.25
  5147.6  341.15  5219.6  343.83  5325.1  346.05  5354.2  346.02  5425.1  347.36
  5454.2  347.18  5477.9  348.73  5630.6  351.68  5736.1  352.41  5811.8  352.16
#Mann=3,-1,0
  4016.9     0.1       0  4992.6    0.07       0  4998.9     0.1       0
Bank Sta=4992.6,4998.9
Exp/Cntr=0.3,0.1

Type RM Length L Ch R = 1,2566,762,762,762
BEGIN DESCRIPTION:
Mapping XS 34ef7223
END DESCRIPTION:
XS GIS Cut Line= 4
      2063068.22     13432222.16      2062495.32     13431827.21
      2061319.11     13431909.67      2060980.75     13432430.23
#Sta/Elev= 30
  3718.2  375.15  3847.5  375.05  3892.1  374.50  3948.9  372.40  3999.6  367.40
  4062.5  357.31  4086.2  354.52  4092.3  352.87  4113.2  351.04  4256.6  348.39
  4484.5  348.90  4644.9  346.81  4905.6  342.06  4945.7  340.92  4992.3  338.03
  4992.8  337.23  4998.7  337.23  4999.2  338.03  5055.9  338.78  5226.4  346.36
  5286.5  347.86  5376.7  348.32  5406.8  347.63  5446.9  349.03  5592.7  348.86
  5635.3  349.69  5707.2  348.06  5722.3  348.24  5758.6  350.73  6214.0  351.63
#Mann=3,-1,0
  3718.2     0.1       0  4992.3    0.07       0  4999.2     0.1       0
Bank Sta=4992.3,4999.2
Exp/Cntr=0.3,0.1

Type RM Length L Ch R = 1,1804,0,0,0
BEGIN DESCRIPTION:
UNT 054 in RCW 6.0
END DESCRIPTION:
XS GIS Cut Line= 4
      2063210.58     13432185.70      2062536.99     13431303.77
      2061370.32     13431338.49      2060870.57     13432400.46
#Sta/Elev= 30
  3436.6  376.75  3739.9  371.51  3812.6  365.36  3897.8  354.77  3962.2  348.59
  4068.3  347.00  4123.9  347.27  4311.4  349.12  4390.3  348.80  4526.0  345.32
  4708.4  342.33  4908.5  341.10  4958.5  336.81  4988.5  335.21  5005.1  333.10
  5005.6  332.30  5011.5  332.30  5012.0  333.10  5048.6  335.21  5087.7  335.75
  5238.6  333.24  5338.7  333.71  5708.7  340.34  5842.3  336.81  5930.9  337.68
  6096.5  345.48  6181.7  347.35  6383.8  347.66  6580.2  350.94  6887.2  351.63
#Mann=5,-1,0
  3436.6     0.1       0  4123.9    0.05       0  4526.0     0.1       0
  5005.1    0.07       0  5012.0     0.1       0
Bank Sta=5005.1,5012
Exp/Cntr=0.3,0.1

Chan Stop Cuts=-1