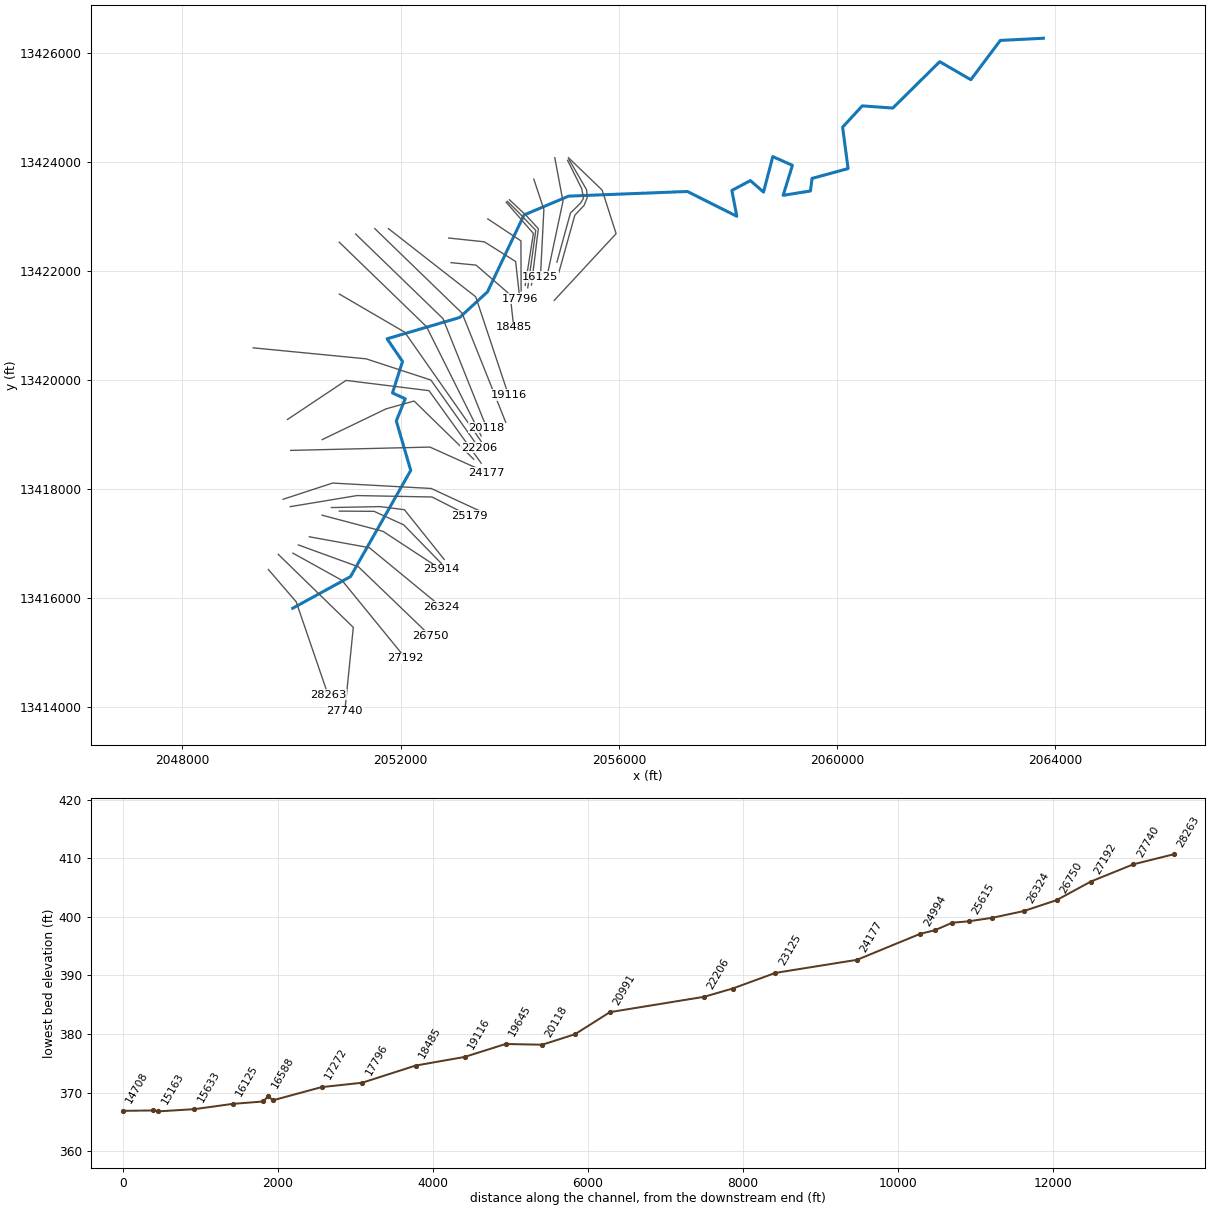
--- UNT 059 in RCW.prj (project) ---

Proj Title=UNT 059 in RCW Base Level Engineering
Current Plan=p01
Default Exp/Contr=0.3,0.1
English Units
Geom File=g01
Flow File=f01
Plan File=p01
Y Axis Title=Elevation
X Axis Title(PF)=Main Channel Distance
X Axis Title(XS)=Station
BEGIN DESCRIPTION:
UNT 059 in RCW
END DESCRIPTION:
DSS Export Rating Curves= 0
DSS Export Rating Curve Sorted= 0
DSS Export Volume Flow Curves= 0
DXF OffsetX= 0
DXF OffsetY= 0
DXF ScaleX= 1
DXF ScaleY= 10

--- UNT 059 in RCW.p01 (plan) ---

Plan Title=Multiple Run
Short Identifier=Multiple
Geom File=g01
Flow File=f01
Subcritical Flow
K Sum by GR= 0
Std Step Tol= 0.01
Critical Tol= 0.01
Num of Std Step Trials= 20
Max Error Tol= 0.3
Flow Tol Ratio= 0.001
Split Flow NTrial= 30
Split Flow Tol= 0.02
Split Flow Ratio= 0.02
Log Output Level= 0
Friction Slope Method= 1
Unsteady Friction Slope Method= 2
Unsteady Bridges Friction Slope Method= 1
Parabolic Critical Depth
Global Vel Dist=  1 , 1 , 1
Global Log Level= 0
CheckData=True
Encroach Param= -1, 0, 0, 0
BEGIN DESCRIPTION:
Multiple Run
END DESCRIPTION:

--- UNT 059 in RCW.f01 (steady flow) ---

Flow Title=Multiple
Program Version=5.05
Number of Profiles= 7
Profile Names=10-year,25-year,50-year,1pct_min,100-year,1pct_plu,500-year
River Rch & RM=UNT 059 in RCW,Reach-1         ,28263
     160     218     264     160     320     638     475
River Rch & RM=UNT 059 in RCW,Reach-1         ,27192
     278     389     481     297     592    1180     909
River Rch & RM=UNT 059 in RCW,Reach-1         ,20991
     339     476     592     366     730    1457    1130
River Rch & RM=UNT 059 in RCW,Reach-1         ,16641
     395     558     695     431     859    1715    1336
River Rch & RM=UNT 059 in RCW,Reach-1         ,13730
     546     780     980     611    1219    2432    1919
River Rch & RM=UNT 059 in RCW,Reach-1         ,12549
     546     780     980     611    1219    2432    1919
Boundary for River Rch & Prof#=UNT 059 in RCW,Reach-1         , 1
Up Type= 0
Dn Type= 3
Dn Slope=0.005
Boundary for River Rch & Prof#=UNT 059 in RCW,Reach-1         , 2
Up Type= 0
Dn Type= 3
Dn Slope=0.005
Boundary for River Rch & Prof#=UNT 059 in RCW,Reach-1         , 3
Up Type= 0
Dn Type= 3
Dn Slope=0.005
Boundary for River Rch & Prof#=UNT 059 in RCW,Reach-1         , 4
Up Type= 0
Dn Type= 3
Dn Slope=0.005
Boundary for River Rch & Prof#=UNT 059 in RCW,Reach-1         , 5
Up Type= 0
Dn Type= 3
Dn Slope=0.005
Boundary for River Rch & Prof#=UNT 059 in RCW,Reach-1         , 6
Up Type= 0
Dn Type= 3
Dn Slope=0.005
Boundary for River Rch & Prof#=UNT 059 in RCW,Reach-1         , 7
Up Type= 0
Dn Type= 3
Dn Slope=0.005
DSS Import GetInterval= 0
DSS Import GetPeak= 0
DSS Import FillOption= 0

--- UNT 059 in RCW.g01 (geometry) ---

Geom Title=Existing Conditions

River Reach=UNT 059 in RCW,Reach-1
Reach XY= 30
      2050020.80     13415814.54      2051080.80     13416394.54
      2052184.57     13418342.20      2051919.81     13419249.31
      2052083.66     13419655.13      2051850.37     13419761.47
      2052033.74     13420339.81      2051750.80     13420754.54
      2053080.80     13421144.54      2053590.80     13421614.54
      2054260.80     13423024.54      2055078.39     13423370.16
      2057255.15     13423454.98      2058161.43     13423000.95
      2058070.80     13423474.54      2058410.80     13423654.54
      2058650.80     13423444.54      2058820.80     13424094.54
      2059180.80     13423934.54      2059010.80     13423384.54
      2059510.80     13423464.54      2059540.80     13423694.54
      2060200.80     13423874.54      2060100.80     13424634.54
      2060460.80     13425024.54      2061020.80     13424984.54
      2061880.80     13425834.54      2062450.80     13425504.54
      2062990.80     13426224.54      2063780.80     13426264.54

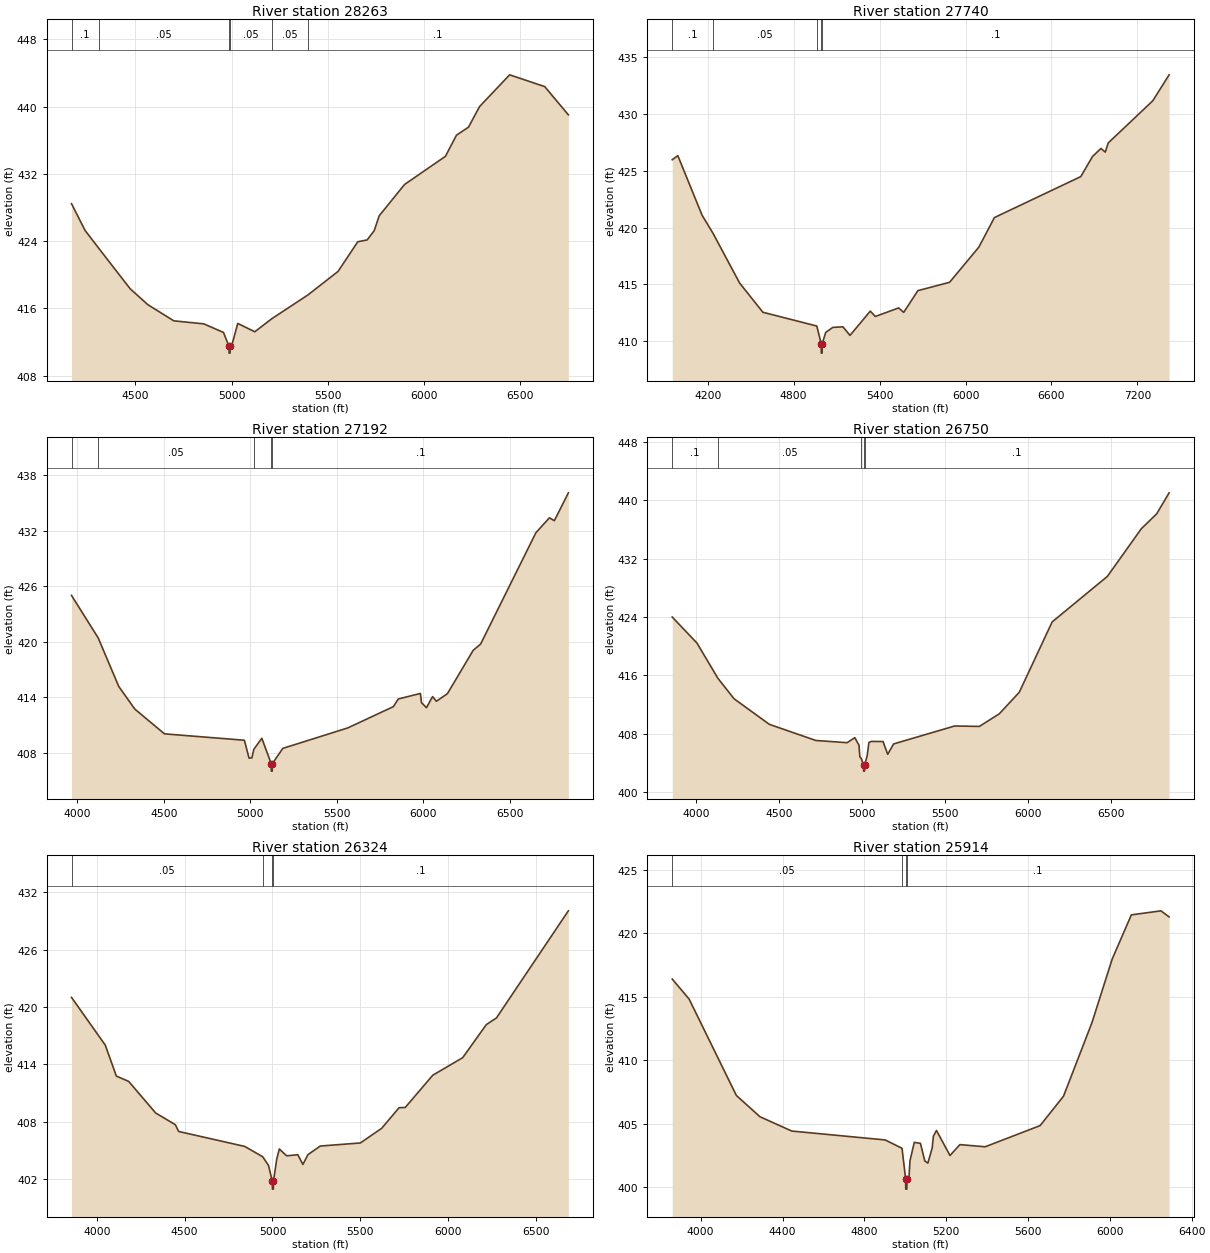
Type RM Length L Ch R = 1,28263,523,523,523
BEGIN DESCRIPTION:
UNT 059 in RCW 30.0
END DESCRIPTION:
XS GIS Cut Line= 3
      2049575.00     13416525.00      2050085.14     13415932.29
      2050668.32     13414229.62
#Sta/Elev= 30
  4167.5  428.46  4238.3  425.27  4309.7  423.14  4472.0  418.35  4564.2  416.45
  4699.1  414.53  4854.9  414.17  4957.2  413.15  4985.9  411.49  4986.4  410.69
  4991.4  410.69  4991.9  411.49  5000.1  411.59  5031.4  414.22  5119.9  413.23
  5207.0  414.76  5395.5  417.60  5552.7  420.41  5654.9  423.93  5703.8  424.15
  5740.4  425.25  5766.4  427.02  5898.0  430.74  6110.5  434.09  6167.8  436.60
  6230.4  437.56  6287.7  440.00  6444.1  443.78  6626.5  442.38  6749.3  439.02
#Mann=6,-1,0
  4167.5     0.1       0  4309.7    0.05       0  4985.9    0.07       0
  4991.9    0.05       0  5207.0    0.05       0  5395.5     0.1       0
Bank Sta=4985.9,4991.9
Exp/Cntr=0.3,0.1

Type RM Length L Ch R = 1,27740,548,548,548
BEGIN DESCRIPTION:
UNT 059 in RCW 29.0
END DESCRIPTION:
XS GIS Cut Line= 3
      2049757.05     13416802.05      2051132.02     13415463.54
      2050975.77     13413921.83
#Sta/Elev= 30
  3952.5  425.96  3991.5  426.32  4161.0  421.08  4237.5  419.49  4422.8  415.13
  4585.4  412.56  4961.7  411.35  4992.7  409.77  4993.2  408.97  4998.2  408.97
  4998.7  409.77  5023.9  410.79  5073.4  411.23  5144.1  411.28  5193.5  410.53
  5335.0  412.66  5370.4  412.19  5533.0  412.94  5568.5  412.55  5667.3  414.46
  5888.2  415.19  6092.9  418.28  6201.6  420.88  6804.7  424.48  6886.6  426.25
  6945.4  426.95  6975.6  426.63  6995.7  427.43  7307.2  431.14  7421.0  433.42
#Mann=5,-1,0
  3952.5     0.1       0  4237.5    0.05       0  4961.7     0.1       0
  4992.7    0.07       0  4998.7     0.1       0
Bank Sta=4992.7,4998.7
Exp/Cntr=0.3,0.1

Type RM Length L Ch R = 1,27192,442,442,442
BEGIN DESCRIPTION:
UNT 059 in RCW 28.0
END DESCRIPTION:
XS GIS Cut Line= 3
      2050025.01     13416824.99      2050925.00     13416325.00
      2052090.15     13414896.07
#Sta/Elev= 30
  3966.0  425.03  4120.4  420.43  4239.4  415.18  4332.1  412.74  4503.6  410.06
  4965.8  409.37  4992.7  407.44  5009.2  407.46  5020.0  408.38  5066.6  409.58
  5121.1  406.83  5121.6  406.03  5126.6  406.03  5127.1  406.83  5188.0  408.49
  5563.5  410.70  5827.1  413.00  5855.8  413.83  5983.6  414.43  5990.0  413.43
  6018.8  412.89  6054.0  414.09  6076.2  413.58  6140.1  414.41  6288.8  419.09
  6331.9  419.77  6651.4  431.80  6729.6  433.42  6758.4  433.11  6839.3  436.12
#Mann=5,-1,0
  3966.0     0.1       0  4120.4    0.05       0  5020.0     0.1       0
  5121.1    0.03       0  5127.1     0.1       0
Bank Sta=5121.1,5127.1
Exp/Cntr=0.3,0.1

Type RM Length L Ch R = 1,26750,426,426,426
BEGIN DESCRIPTION:
UNT 059 in RCW 27.0
END DESCRIPTION:
XS GIS Cut Line= 3
      2050125.04     13416974.99      2051225.00     13416575.00
      2052538.25     13415312.52
#Sta/Elev= 30
  3855.9  423.98  4004.8  420.41  4131.1  415.57  4228.3  412.77  4441.1  409.26
  4721.1  407.05  4909.3  406.75  4955.2  407.44  4980.4  406.41  4985.8  404.80
  4993.9  404.61  5007.9  403.65  5008.4  402.85  5013.7  402.85  5014.2  403.65
  5029.8  404.96  5040.3  406.78  5054.5  406.92  5125.2  406.91  5153.5  405.16
  5189.1  406.58  5556.7  409.04  5705.4  408.98  5825.5  410.71  5945.7  413.66
  6143.8  423.31  6476.2  429.55  6681.2  436.10  6773.3  438.13  6848.0  441.01
#Mann=5,-1,0
  3855.9     0.1       0  4131.1    0.05       0  4993.9     0.1       0
  5007.9    0.07       0  5014.2     0.1       0
Bank Sta=5007.9,5014.2
Exp/Cntr=0.3,0.1

Type RM Length L Ch R = 1,26324,410,410,410
BEGIN DESCRIPTION:
UNT 059 in RCW 26.0
END DESCRIPTION:
XS GIS Cut Line= 3
      2050325.00     13417125.00      2051425.00     13416925.00
      2052745.68     13415839.30
#Sta/Elev= 30
  3856.2  421.00  4048.0  416.03  4111.6  412.78  4181.5  412.23  4335.2  408.93
  4447.0  407.71  4466.0  407.00  4842.1  405.44  4944.4  404.36  4977.5  403.45
  4999.1  401.78  4999.6  400.98  5004.9  400.98  5005.4  401.78  5024.4  404.13
  5038.8  405.17  5080.4  404.46  5144.3  404.57  5173.0  403.56  5201.7  404.58
  5272.0  405.48  5500.1  405.80  5621.4  407.33  5720.4  409.48  5755.6  409.51
  5912.0  412.87  6082.7  414.71  6217.0  418.16  6274.3  418.85  6683.9  430.04
#Mann=4,-1,0
  3856.2    0.05       0  4944.4     0.1       0  4999.1    0.07       0
  5005.4     0.1       0
Bank Sta=4999.1,5005.4
Exp/Cntr=0.3,0.1

Type RM Length L Ch R = 1,25914,299,299,299
BEGIN DESCRIPTION:
UNT 059 in RCW 25.0
END DESCRIPTION:
XS GIS Cut Line= 3
      2050559.10     13417520.83      2051675.00     13417225.00
      2052740.73     13416526.48
#Sta/Elev= 30
  3861.0  416.40  3943.5  414.82  4174.4  407.22  4289.8  405.54  4445.4  404.41
  4901.7  403.71  4984.3  403.05  5001.9  400.63  5002.4  399.83  5007.8  399.83
  5008.3  400.63  5018.4  400.81  5023.0  402.06  5044.1  403.52  5074.3  403.44
  5095.4  402.06  5110.5  401.88  5131.5  403.06  5137.5  404.00  5152.6  404.46
  5218.7  402.48  5267.1  403.34  5390.7  403.17  5659.1  404.84  5773.6  407.16
  5912.2  412.94  6011.7  417.98  6105.2  421.46  6249.9  421.78  6289.7  421.30
#Mann=4,-1,0
  3861.0    0.05       0  4984.3     0.1       0  5001.9    0.07       0
  5008.3     0.1       0
Bank Sta=5001.9,5008.3
Exp/Cntr=0.3,0.1

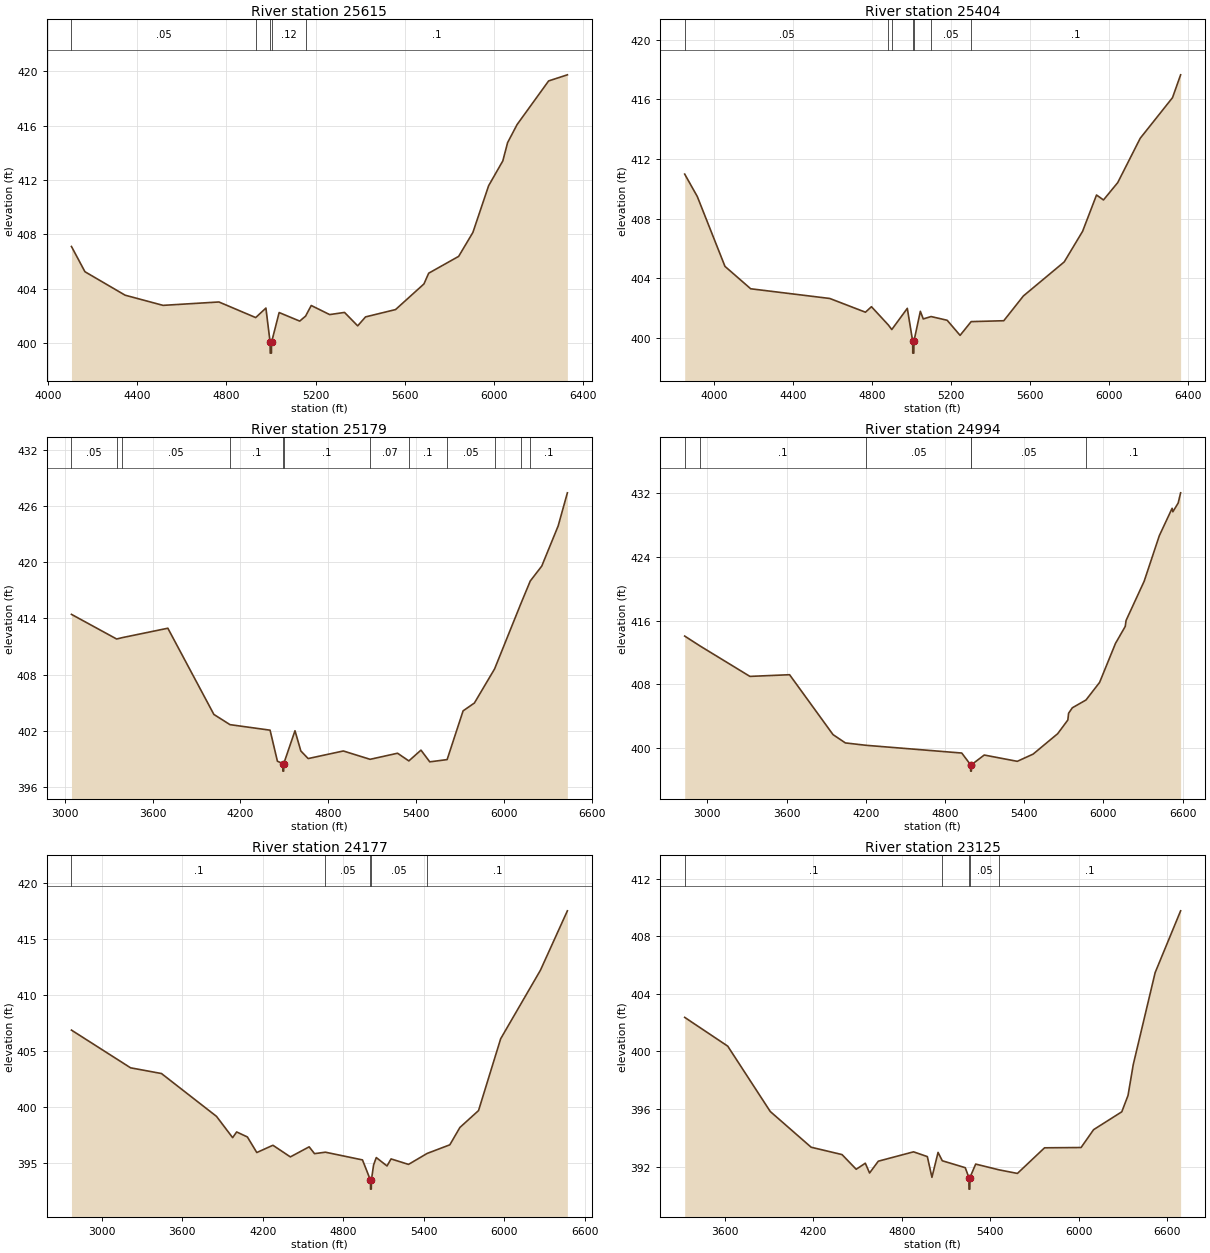
Type RM Length L Ch R = 1,25615,211,211,211
BEGIN DESCRIPTION:
Mapping XS f47b9d48
END DESCRIPTION:
XS GIS Cut Line= 4
      2050874.56     13417595.36      2051512.54     13417591.02
      2052055.08     13417343.63      2052745.19     13416636.15
#Sta/Elev= 30
  4106.1  407.10  4166.5  405.24  4346.5  403.51  4516.6  402.76  4767.0  403.01
  4931.8  401.86  4977.6  402.56  4996.4  400.04  4996.9  399.24  5002.3  399.24
  5002.8  400.04  5036.9  402.23  5129.1  401.60  5155.5  401.97  5180.7  402.75
  5263.4  402.08  5329.9  402.24  5388.9  401.25  5424.1  401.91  5558.6  402.45
  5685.9  404.34  5707.1  405.13  5841.4  406.37  5905.1  408.13  5975.8  411.58
  6039.4  413.41  6060.7  414.75  6103.1  416.08  6244.6  419.30  6328.7  419.75
#Mann=5,-1,0
  4106.1    0.05       0  4931.8    0.12       0  4996.4    0.07       0
  5002.8    0.12       0  5155.5     0.1       0
Bank Sta=4996.4,5002.8
Exp/Cntr=0.3,0.1

Type RM Length L Ch R = 1,25404,225,225,225
BEGIN DESCRIPTION:
Mapping XS 42e81434
END DESCRIPTION:
XS GIS Cut Line= 4
      2050731.30     13417660.47      2051621.05     13417677.83
      2052068.10     13417621.40      2052797.24     13416709.98
#Sta/Elev= 30
  3852.6  410.99  3916.3  409.49  4056.3  404.81  4186.4  403.31  4586.4  402.66
  4766.7  401.74  4796.9  402.11  4882.1  400.89  4899.8  400.58  4978.3  402.00
  5005.4  399.80  5005.9  399.00  5011.3  399.00  5011.8  399.80  5044.2  401.80
  5059.0  401.29  5098.6  401.45  5179.9  401.20  5245.2  400.19  5301.1  401.11
  5466.1  401.17  5565.3  402.83  5771.8  405.11  5864.7  407.16  5935.1  409.59
  5970.3  409.26  6042.3  410.42  6156.0  413.39  6319.3  416.11  6360.3  417.64
#Mann=7,-1,0
  3852.6    0.05       0  4882.1     0.1       0  4899.8    0.12       0
  5005.4    0.07       0  5011.8    0.12       0  5098.6    0.05       0
  5301.1     0.1       0
Bank Sta=5005.4,5011.8
Exp/Cntr=0.3,0.1

Type RM Length L Ch R = 1,25179,185,185,185
BEGIN DESCRIPTION:
Mapping XS 473c4963
END DESCRIPTION:
XS GIS Cut Line= 4
      2049975.82     13417677.09      2051199.73     13417880.20
      2052574.73     13417854.16      2053261.08     13417505.79
#Sta/Elev= 30
  3046.6  414.44  3355.0  411.81  3394.6  411.96  3704.7  412.96  4018.9  403.76
  4129.0  402.67  4402.5  402.08  4452.6  398.77  4489.3  398.51  4489.8  397.71
  4495.4  397.71  4495.9  398.51  4572.6  402.02  4612.6  399.86  4662.6  399.05
  4902.6  399.86  5085.4  398.97  5272.7  399.62  5349.9  398.80  5432.7  399.95
  5492.7  398.70  5611.2  398.94  5720.2  404.14  5797.4  404.98  5935.3  408.62
  6113.0  415.52  6178.8  418.00  6257.2  419.59  6369.3  423.88  6432.2  427.41
#Mann=12,-1,0
  3046.6    0.05       0  3355.0     0.1       0  3394.6    0.05       0
  4129.0     0.1       0  4489.3    0.07       0  4495.9     0.1       0
  5085.4    0.07       0  5349.9     0.1       0  5611.2    0.05       0
  5935.3     0.1       0  6113.0    0.05       0  6178.8     0.1       0
Bank Sta=4489.3,4495.9
Exp/Cntr=0.3,0.1

Type RM Length L Ch R = 1,24994,817,817,817
BEGIN DESCRIPTION:
Mapping XS c176202d
END DESCRIPTION:
XS GIS Cut Line= 4
      2049845.54     13417812.49      2050751.81     13418109.37
      2052559.10     13418010.41      2053460.07     13417593.78
#Sta/Elev= 30
  2828.1  414.07  2945.3  412.82  3322.1  409.01  3622.6  409.22  3951.7  401.70
  4045.3  400.66  4202.8  400.36  4926.7  399.39  4993.5  397.92  4994.0  397.12
  4999.6  397.12  5000.1  397.92  5096.9  399.14  5347.3  398.35  5467.5  399.26
  5653.3  401.82  5730.3  403.54  5735.8  404.38  5764.3  405.07  5867.7  406.05
  5970.6  408.25  6090.8  413.14  6165.1  415.29  6171.2  416.03  6308.2  420.95
  6422.8  426.66  6520.1  430.11  6525.6  429.67  6565.9  430.77  6584.4  432.05
#Mann=6,-1,0
  2828.1    0.05       0  2945.3     0.1       0  4202.8    0.05       0
  4993.5    0.03       0  5000.1    0.05       0  5867.7     0.1       0
Bank Sta=4993.5,5000.1
Exp/Cntr=0.3,0.1

Type RM Length L Ch R = 1,24177,1052,1052,1052
BEGIN DESCRIPTION:
UNT 059 in RCW 22.0
END DESCRIPTION:
XS GIS Cut Line= 3
      2049984.42     13418708.33      2052536.53     13418769.09
      2053578.19     13418300.35
#Sta/Elev= 30
  2774.3  406.88  3215.0  403.51  3445.1  403.00  3855.2  399.17  3975.2  397.27
  4005.2  397.78  4085.2  397.33  4155.3  395.94  4275.3  396.59  4405.3  395.55
  4545.4  396.45  4585.4  395.84  4666.4  395.97  4942.8  395.28  5002.2  393.47
  5002.7  392.67  5008.4  392.67  5008.9  393.47  5025.5  394.83  5045.5  395.49
  5125.5  394.74  5155.6  395.37  5285.6  394.88  5424.5  395.86  5593.5  396.63
  5668.5  398.18  5807.4  399.69  5972.4  406.11  6268.5  412.23  6469.4  417.54
#Mann=5,-1,0
  2774.3     0.1       0  4666.4    0.05       0  5002.2    0.03       0
  5008.9    0.05       0  5424.5     0.1       0
Bank Sta=5002.2,5008.9
Exp/Cntr=0.3,0.1

Type RM Length L Ch R = 1,23125,552,552,552
BEGIN DESCRIPTION:
Mapping XS 73ccbfc1
END DESCRIPTION:
XS GIS Cut Line= 4
      2050562.06     13418906.14      2051733.90     13419470.36
      2052246.05     13419613.59      2053339.81     13418545.87
#Sta/Elev= 30
  3328.4  402.37  3620.2  400.37  3908.4  395.83  4185.4  393.35  4394.6  392.84
  4490.7  391.82  4552.5  392.24  4581.2  391.56  4640.5  392.38  4879.3  393.03
  4972.8  392.70  5004.0  391.26  5045.5  392.99  5074.2  392.41  5229.7  391.93
  5254.6  391.24  5255.1  390.44  5260.8  390.44  5261.3  391.24  5300.4  392.18
  5458.3  391.78  5583.3  391.53  5767.2  393.31  6014.7  393.33  6099.5  394.57
  6290.6  395.81  6333.0  396.95  6368.3  399.09  6516.7  405.48  6689.3  409.77
#Mann=5,-1,0
  3328.4     0.1       0  5074.2    0.05       0  5254.6    0.07       0
  5261.3    0.05       0  5458.3     0.1       0
Bank Sta=5254.6,5261.3
Exp/Cntr=0.3,0.1

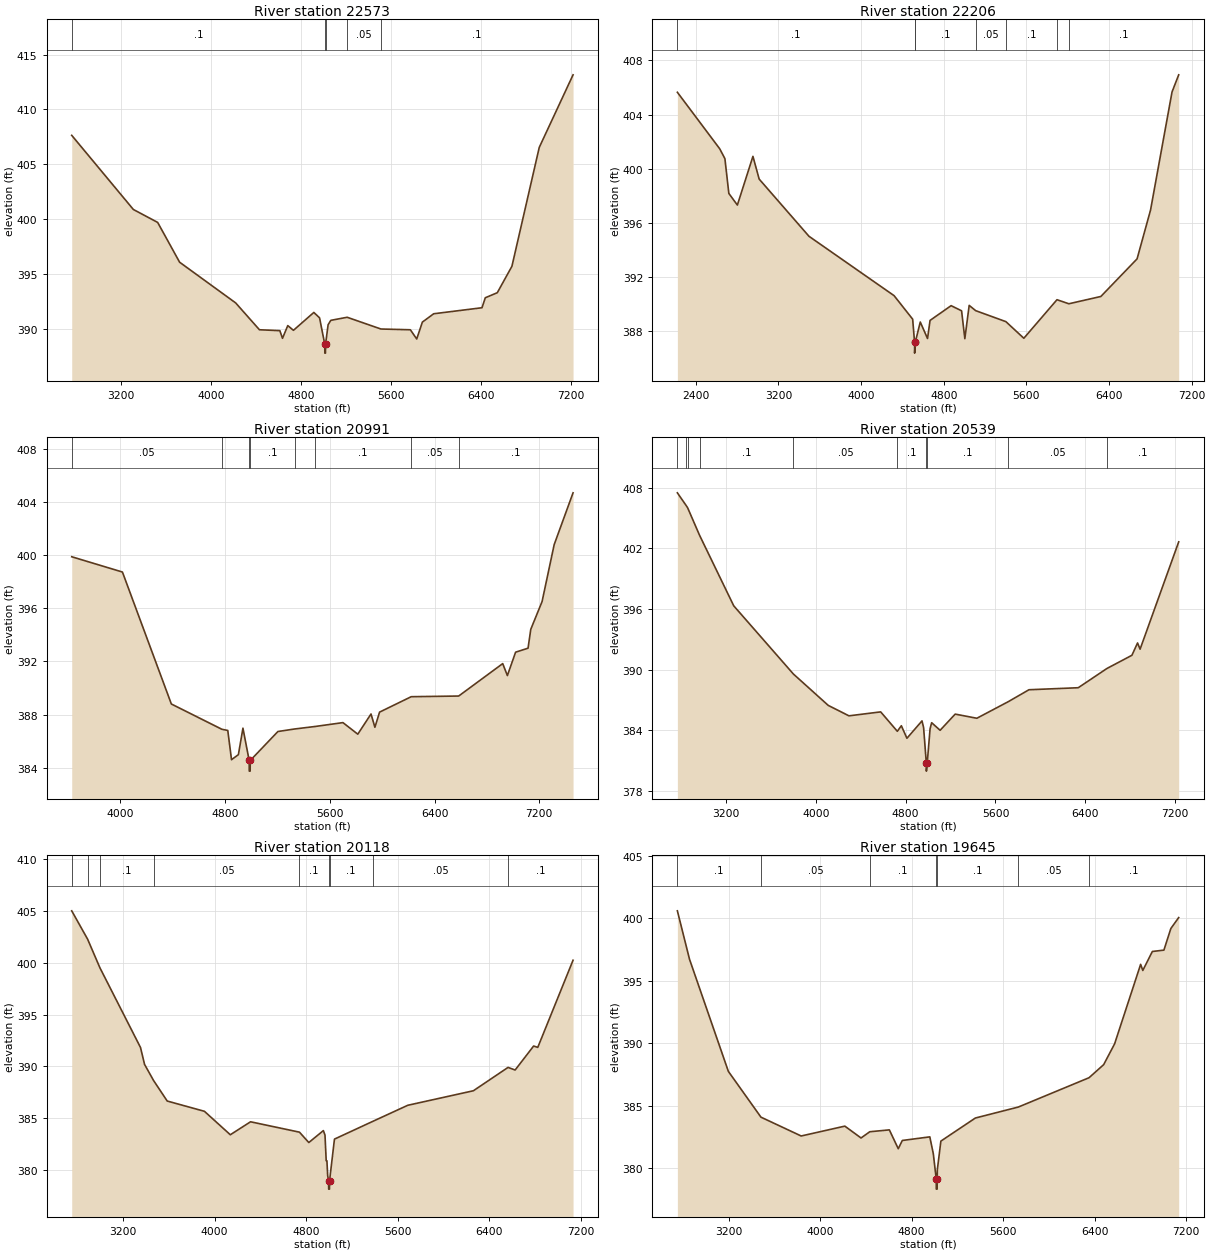
Type RM Length L Ch R = 1,22573,367,367,367
BEGIN DESCRIPTION:
UNT 059 in RCW 21.0
END DESCRIPTION:
XS GIS Cut Line= 4
      2049925.00     13419275.00      2050998.34     13419991.32
      2052519.17     13419803.82      2053474.98     13418475.03
#Sta/Elev= 30
  2762.3  407.63  3310.5  400.87  3526.8  399.69  3722.1  396.06  4220.6  392.35
  4432.2  389.90  4613.6  389.82  4637.2  389.12  4684.1  390.28  4734.5  389.85
  4915.9  391.48  4966.9  390.99  5013.3  388.57  5013.8  387.77  5019.5  387.77
  5020.0  388.57  5043.0  390.36  5067.0  390.76  5212.4  391.04  5512.7  389.97
  5774.7  389.90  5831.2  389.06  5881.5  390.60  5982.2  391.36  6411.8  391.91
  6441.2  392.82  6548.0  393.28  6678.1  395.69  6921.2  406.53  7221.9  413.15
#Mann=5,-1,0
  2762.3     0.1       0  5013.3    0.07       0  5020.0     0.1       0
  5212.4    0.05       0  5512.7     0.1       0
Bank Sta=5013.3,5020
Exp/Cntr=0.3,0.1

Type RM Length L Ch R = 1,22206,1215,1215,1215
BEGIN DESCRIPTION:
Mapping XS db28e155
END DESCRIPTION:
XS GIS Cut Line= 4
      2049296.97     13420588.54      2051366.39     13420387.15
      2052553.89     13419998.26      2053435.84     13418755.21
#Sta/Elev= 30
  2221.3  405.65  2631.3  401.47  2681.5  400.74  2719.5  398.17  2802.1  397.31
  2952.8  400.91  3013.1  399.23  3495.3  395.00  4319.1  390.61  4499.0  388.87
  4517.4  387.16  4517.9  386.36  4524.1  387.16  4572.6  388.66  4642.9  387.44
  4667.3  388.78  4871.1  389.87  4972.5  389.49  5004.0  387.43  5046.1  389.89
  5108.9  389.50  5401.1  388.69  5575.2  387.46  5896.0  390.31  6011.2  390.01
  6320.7  390.55  6671.3  393.33  6801.7  396.94  7009.6  405.67  7074.2  406.94
#Mann=7,-1,0
  2221.3     0.1       0  4517.4    0.07       0  4524.1     0.1       0
  5108.9    0.05       0  5401.1     0.1       0  5896.0    0.05       0
  6011.2     0.1       0
Bank Sta=4517.4,4524.1
Exp/Cntr=0.3,0.1

Type RM Length L Ch R = 1,20991,452,452,452
BEGIN DESCRIPTION:
UNT 059 in RCW 20.0
END DESCRIPTION:
XS GIS Cut Line= 3
      2050875.03     13421574.98      2052075.00     13420875.00
      2053474.99     13418875.01
#Sta/Elev= 30
  3627.4  399.87  4014.8  398.72  4388.6  388.79  4774.4  386.89  4819.8  386.80
  4848.3  384.60  4900.8  384.98  4935.6  386.97  4983.2  384.54  4983.9  383.74
  4990.7  383.74  4991.3  384.54  5202.8  386.72  5330.0  386.91  5487.7  387.10
  5699.7  387.39  5813.1  386.52  5914.2  388.04  5943.9  387.04  5979.6  388.18
  6221.4  389.34  6584.0  389.39  6920.4  391.83  6956.1  390.93  7018.9  392.69
  7114.0  392.99  7134.9  394.41  7221.2  396.50  7313.6  400.78  7457.9  404.68
#Mann=8,-1,0
  3627.4    0.05       0  4774.4     0.1       0  4983.2    0.07       0
  4991.3     0.1       0  5330.0    0.05       0  5487.7     0.1       0
  6221.4    0.05       0  6584.0     0.1       0
Bank Sta=4983.2,4991.3
Exp/Cntr=0.3,0.1

Type RM Length L Ch R = 1,20539,421,421,421
BEGIN DESCRIPTION:
UNT 059 in RCW 19.0
END DESCRIPTION:
XS GIS Cut Line= 3
      2050875.02     13422524.98      2052475.00     13420975.00
      2053475.00     13418975.00
#Sta/Elev= 30
  2767.7  407.49  2841.9  406.30  2858.8  406.02  2964.9  403.30  3269.7  396.31
  3800.4  389.57  4111.3  386.46  4295.3  385.43  4578.0  385.82  4726.2  383.90
  4761.9  384.45  4811.5  383.21  4945.8  384.93  4960.0  384.27  4984.2  380.76
  4984.9  379.96  4992.3  380.76  5017.7  384.15  5031.7  384.75  5107.1  384.00
  5241.3  385.60  5434.2  385.19  5713.9  386.83  5898.1  388.01  6337.0  388.21
  6591.9  390.11  6814.9  391.42  6865.2  392.64  6887.6  392.02  7231.4  402.64
#Mann=10,-1,0
  2767.7    0.08       0  2841.9    0.05       0  2858.8    0.08       0
  2964.9     0.1       0  3800.4    0.05       0  4726.2     0.1       0
  4984.2    0.07       0  4992.3     0.1       0  5713.9    0.05       0
  6591.9     0.1       0
Bank Sta=4984.2,4992.3
Exp/Cntr=0.3,0.1

Type RM Length L Ch R = 1,20118,473,473,473
BEGIN DESCRIPTION:
UNT 059 in RCW 18.0
END DESCRIPTION:
XS GIS Cut Line= 3
      2051174.98     13422675.02      2052775.00     13421125.00
      2053575.01     13419124.97
#Sta/Elev= 30
  2752.1  405.00  2891.3  402.26  2998.5  399.51  3353.2  391.83  3388.7  390.20
  3467.3  388.65  3586.7  386.67  3911.9  385.68  4138.2  383.42  4315.0  384.67
  4742.5  383.67  4824.3  382.67  4951.6  383.82  4965.8  383.38  4976.3  380.91
  4982.5  380.91  4989.2  379.48  4997.2  378.98  4997.9  378.18  5004.7  378.18
  5005.5  378.98  5048.5  383.00  5383.4  384.71  5689.3  386.26  6262.8  387.66
  6565.7  389.91  6627.7  389.66  6789.2  391.97  6825.6  391.84  7133.9  400.24
#Mann=9,-1,0
  2752.1    0.08       0  2891.3    0.05       0  2998.5     0.1       0
  3467.3    0.05       0  4742.5     0.1       0  4997.2    0.07       0
  5005.5     0.1       0  5383.4    0.05       0  6565.7     0.1       0
Bank Sta=4997.2,5005.5
Exp/Cntr=0.3,0.1

Type RM Length L Ch R = 1,19645,529,529,529
BEGIN DESCRIPTION:
UNT 059 in RCW 17.0
END DESCRIPTION:
XS GIS Cut Line= 3
      2051524.98     13422775.02      2053125.00     13421225.00
      2053925.01     13419224.97
#Sta/Elev= 30
  2752.1  400.61  2858.2  396.73  3197.7  387.74  3482.6  384.07  3834.2  382.56
  4215.9  383.35  4357.4  382.40  4433.9  382.90  4604.9  383.05  4682.8  381.54
  4718.1  382.20  4958.6  382.49  4989.2  381.13  5014.7  379.10  5015.4  378.30
  5022.3  378.30  5023.0  379.10  5024.2  379.85  5055.2  382.15  5356.8  384.00
  5732.1  384.88  6350.1  387.23  6478.2  388.28  6573.8  389.95  6801.3  396.32
  6820.2  395.83  6903.6  397.35  7004.6  397.46  7065.2  399.19  7133.9  400.07
#Mann=7,-1,0
  2752.1     0.1       0  3482.6    0.05       0  4433.9     0.1       0
  5014.7    0.07       0  5023.0     0.1       0  5732.1    0.05       0
  6350.1     0.1       0
Bank Sta=5014.7,5023
Exp/Cntr=0.3,0.1

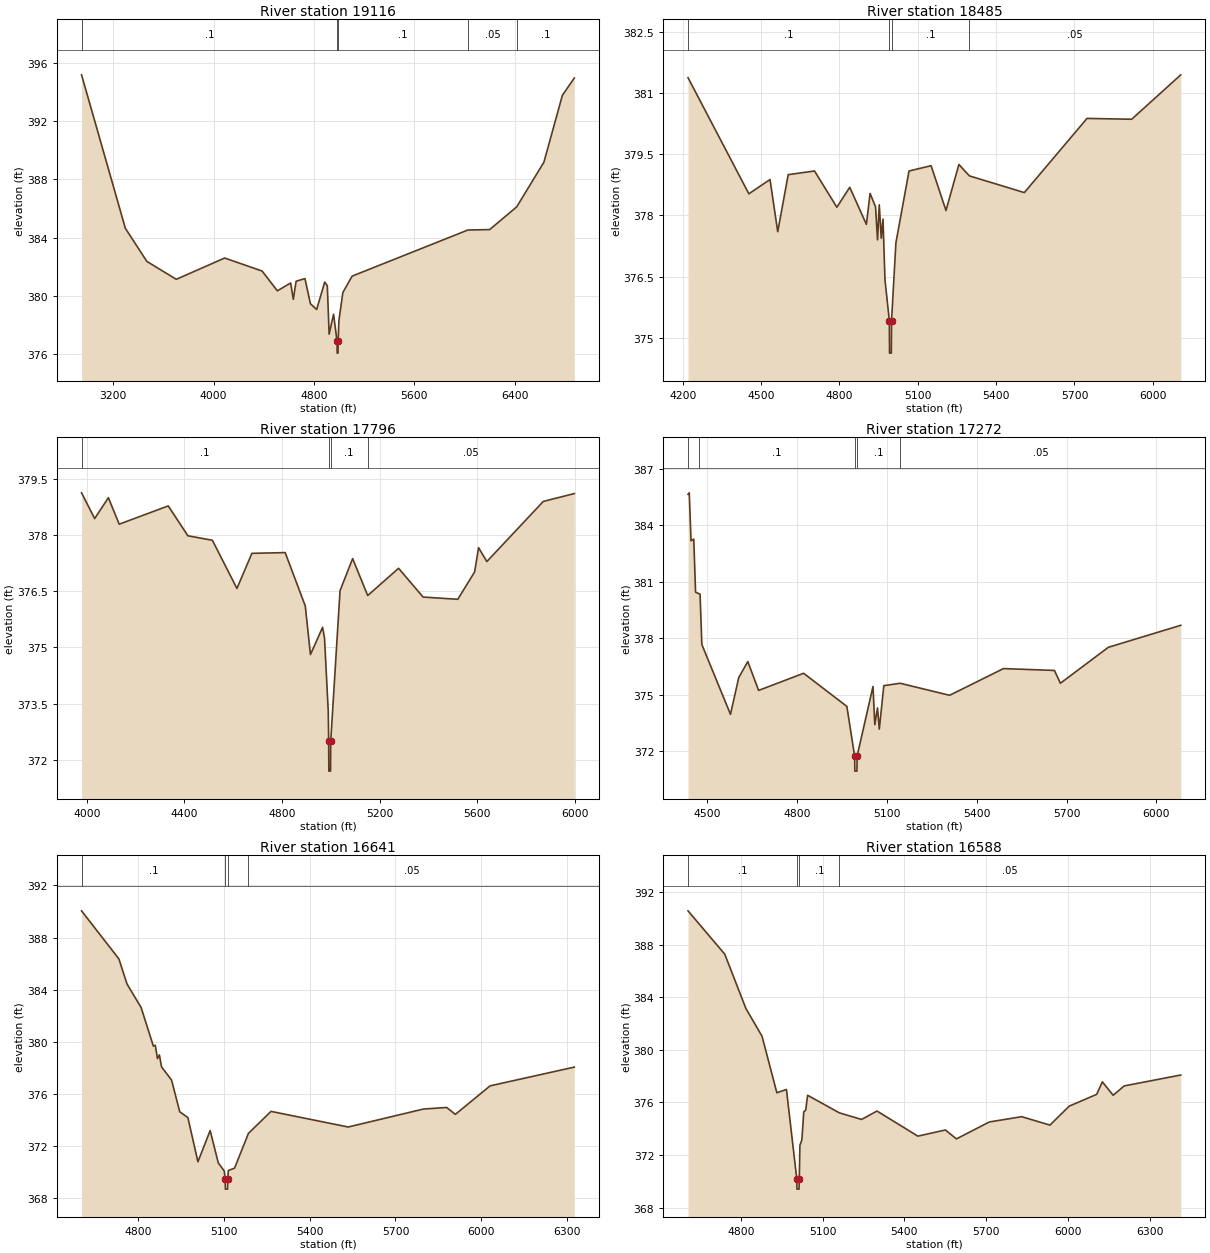
Type RM Length L Ch R = 1,19116,631,631,631
BEGIN DESCRIPTION:
UNT 059 in RCW 16.0
END DESCRIPTION:
XS GIS Cut Line= 3
      2051774.97     13422775.02      2053375.00     13421525.00
      2053975.00     13419725.00
#Sta/Elev= 30
  2948.0  395.17  3297.1  384.65  3468.3  382.38  3703.2  381.15  4088.5  382.61
  4387.0  381.72  4508.9  380.36  4614.9  380.90  4635.8  379.78  4658.3  381.02
  4728.8  381.20  4772.2  379.48  4822.0  379.08  4886.2  380.96  4907.0  380.71
  4921.5  377.39  4956.7  378.76  4984.8  376.89  4985.5  376.09  4992.4  376.09
  4993.1  376.89  4999.5  378.33  5031.1  380.25  5104.9  381.37  6027.5  384.53
  6201.2  384.56  6416.9  386.12  6633.4  389.18  6780.9  393.77  6875.8  394.95
#Mann=5,-1,0
  2948.0     0.1       0  4984.8    0.07       0  4993.1     0.1       0
  6027.5    0.05       0  6416.9     0.1       0
Bank Sta=4984.8,4993.1
Exp/Cntr=0.3,0.1

Type RM Length L Ch R = 1,18485,689,689,689
BEGIN DESCRIPTION:
Mapping XS 7d6f5338
END DESCRIPTION:
XS GIS Cut Line= 4
      2052923.20     13422150.34      2053381.50     13422105.20
      2054006.50     13421563.54      2054072.27     13420968.13
#Sta/Elev= 30
  4220.5  381.38  4453.4  378.53  4534.4  378.88  4564.0  377.60  4604.1  379.00
  4704.9  379.09  4790.4  378.20  4839.7  378.69  4903.4  377.78  4917.6  378.54
  4938.5  378.21  4946.1  377.40  4952.7  378.26  4960.4  377.44  4967.0  377.91
  4974.6  376.42  4991.3  375.42  4992.0  374.62  4998.9  374.62  4999.7  375.42
  5016.5  377.33  5066.7  379.09  5151.2  379.22  5208.2  378.12  5257.6  379.25
  5297.8  378.97  5508.1  378.56  5748.1  380.38  5919.1  380.36  6107.1  381.45
#Mann=4,-1,0
  4220.5     0.1       0  4991.3    0.07       0  4999.7     0.1       0
  5297.8    0.05       0
Bank Sta=4991.3,4999.7
Exp/Cntr=0.3,0.1

Type RM Length L Ch R = 1,17796,524,524,524
BEGIN DESCRIPTION:
Mapping XS ee61b31c
END DESCRIPTION:
XS GIS Cut Line= 4
      2052881.49     13422601.73      2053534.28     13422532.29
      2054107.19     13422171.18      2054183.42     13421488.62
#Sta/Elev= 30
  3977.9  379.14  4031.7  378.45  4087.9  379.01  4132.3  378.30  4333.4  378.79
  4413.9  377.99  4514.4  377.87  4615.0  376.58  4676.4  377.52  4812.9  377.54
  4895.3  376.11  4916.5  374.81  4966.2  375.54  4974.2  375.25  4989.5  373.29
  4991.2  372.49  4991.9  371.69  4998.8  371.69  4999.6  372.49  5037.8  376.52
  5089.5  377.38  5151.2  376.39  5277.9  377.12  5378.2  376.35  5520.6  376.29
  5589.5  377.02  5605.9  377.67  5639.8  377.30  5871.2  378.91  5998.4  379.12
#Mann=4,-1,0
  3977.9     0.1       0  4991.2    0.07       0  4999.6     0.1       0
  5151.2    0.05       0
Bank Sta=4991.2,4999.6
Exp/Cntr=0.3,0.1

Type RM Length L Ch R = 1,17272,631,631,631
BEGIN DESCRIPTION:
Mapping XS fa017a76
END DESCRIPTION:
XS GIS Cut Line= 3
      2053596.77     13422952.43      2054204.42     13422549.65
      2054207.89     13421632.97
#Sta/Elev= 30
  4435.5  385.65  4439.6  385.73  4445.6  383.18  4454.7  383.27  4460.7  380.45
  4473.6  380.36  4475.7  380.34  4481.7  377.67  4577.3  373.96  4605.1  375.92
  4635.2  376.76  4671.3  375.23  4821.6  376.14  4966.0  374.38  4991.9  371.74
  4992.7  370.94  4999.6  370.94  5000.3  371.74  5053.3  375.44  5059.3  373.41
  5068.3  374.30  5074.3  373.17  5089.4  375.48  5143.7  375.61  5309.2  374.97
  5489.2  376.39  5659.2  376.29  5679.2  375.61  5839.2  377.52  6081.2  378.69
#Mann=5,-1,0
  4435.5    0.05       0  4473.6     0.1       0  4991.9    0.07       0
  5000.3     0.1       0  5143.7    0.05       0
Bank Sta=4991.9,5000.3
Exp/Cntr=0.3,0.1

Type RM Length L Ch R = 1,16641,53,53,53
BEGIN DESCRIPTION:
Mapping XS 9c3fb150
END DESCRIPTION:
XS GIS Cut Line= 3
      2053934.43     13423258.54      2054432.68     13422685.64
      2054282.51     13421734.27
#Sta/Elev= 30
  4602.8  390.05  4733.3  386.36  4761.8  384.43  4811.1  382.62  4853.9  379.66
  4860.5  379.73  4868.1  378.70  4874.8  378.99  4882.4  378.07  4917.5  377.05
  4946.0  374.62  4974.5  374.17  5009.6  370.78  5052.3  373.18  5080.8  370.69
  5101.7  370.07  5104.7  369.48  5105.5  368.68  5113.1  368.68  5114.0  369.48
  5115.9  370.11  5137.6  370.29  5186.1  372.96  5265.0  374.65  5534.8  373.45
  5798.0  374.83  5879.0  374.95  5909.4  374.42  6030.9  376.61  6325.2  378.05
#Mann=4,-1,0
  4602.8     0.1       0  5104.7    0.07       0  5114.0     0.1       0
  5186.1    0.05       0
Bank Sta=5104.7,5114
Exp/Cntr=0.3,0.1

Type RM Length L Ch R = 1,16588,70,70,70
BEGIN DESCRIPTION:
Mapping XS 8bb791d7
END DESCRIPTION:
XS GIS Cut Line= 5
      2053954.44     13423275.32      2054148.11     13423084.80
      2054475.80     13422741.92      2054464.83     13422657.29
      2054329.52     13421689.30
#Sta/Elev= 30
  4606.0  390.58  4741.0  387.28  4818.7  383.14  4877.7  381.04  4932.1  376.74
  4967.3  376.99  5005.1  370.21  5005.9  369.41  5013.5  369.41  5014.4  370.21
  5016.7  372.75  5023.9  373.15  5030.8  375.29  5038.0  375.41  5045.0  376.55
  5161.8  375.21  5243.1  374.71  5299.7  375.35  5449.7  373.44  5550.7  373.91
  5591.1  373.23  5712.2  374.52  5830.9  374.92  5934.4  374.28  6005.1  375.72
  6106.0  376.62  6126.8  377.57  6166.6  376.55  6207.0  377.26  6414.7  378.09
#Mann=4,-1,0
  4606.0     0.1       0  5005.1    0.07       0  5014.4     0.1       0
  5161.8    0.05       0
Bank Sta=5005.1,5014.4
Exp/Cntr=0.3,0.1

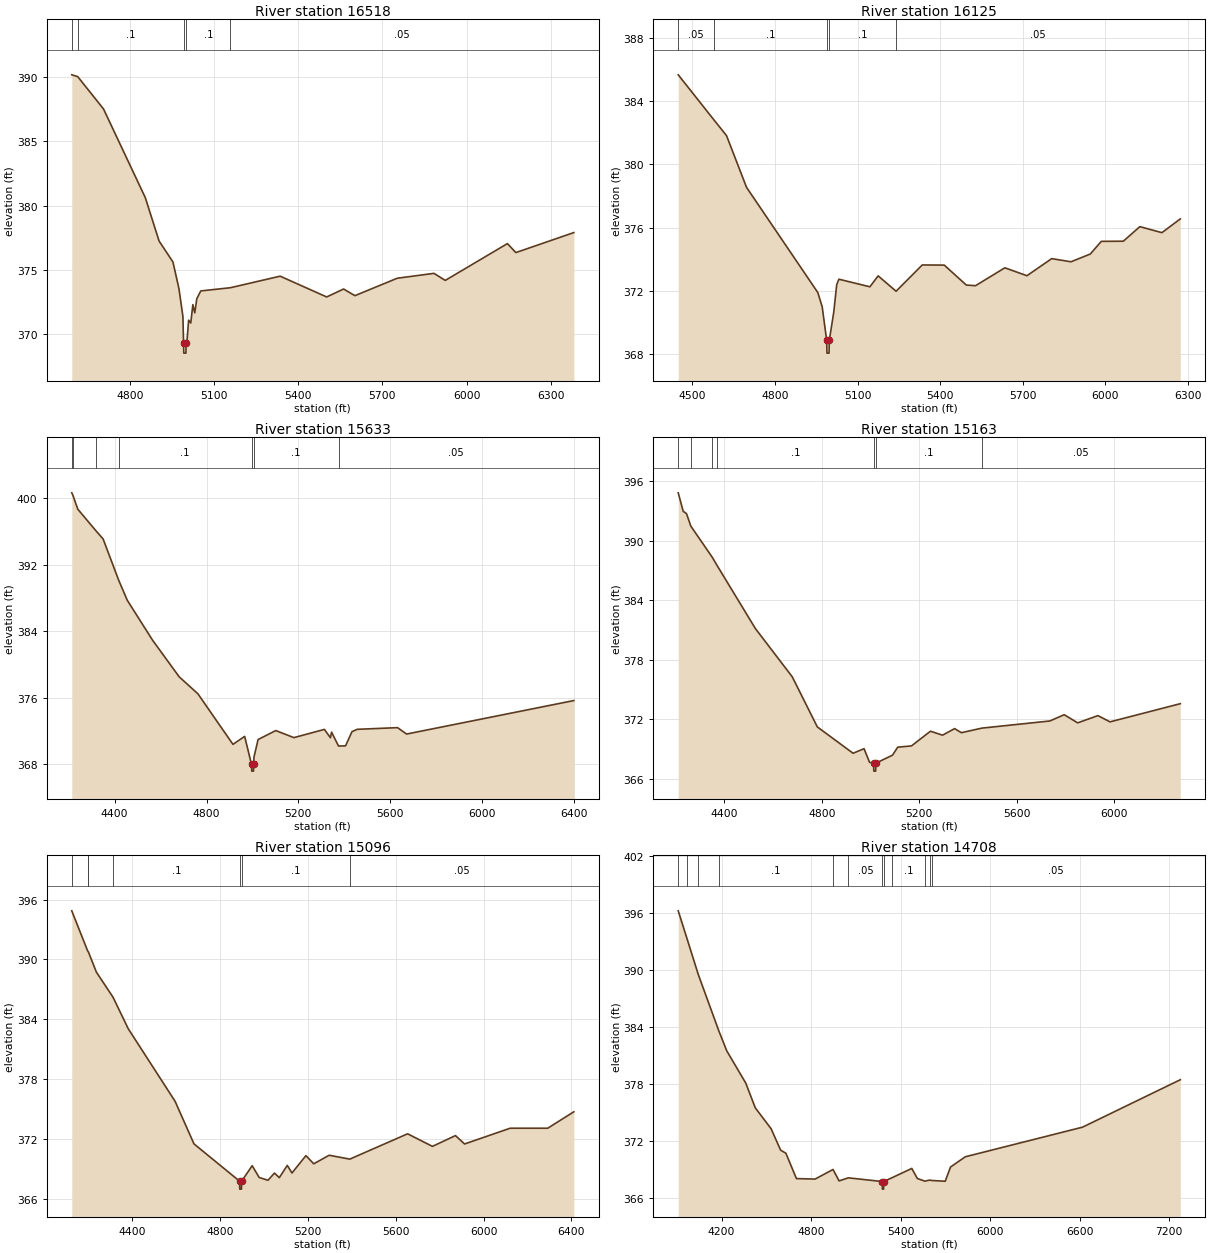
Type RM Length L Ch R = 1,16518,393,393,393
BEGIN DESCRIPTION:
Mapping XS b709b775
END DESCRIPTION:
XS GIS Cut Line= 4
      2053993.42     13423303.72      2054299.00     13423017.24
      2054522.96     13422772.44      2054397.13     13421739.74
#Sta/Elev= 30
  4591.8  390.19  4613.0  390.05  4705.0  387.53  4854.0  380.62  4903.3  377.23
  4952.7  375.60  4974.2  373.51  4988.3  371.35  4990.5  369.29  4991.4  368.49
  4999.0  368.49  4999.8  369.29  5002.5  369.35  5008.7  371.06  5016.3  370.84
  5023.7  372.27  5030.5  371.63  5037.9  372.74  5052.1  373.34  5157.7  373.59
  5335.1  374.49  5501.1  372.87  5561.5  373.49  5601.8  372.97  5752.9  374.33
  5883.9  374.71  5924.2  374.16  6145.8  377.03  6176.0  376.33  6382.8  377.89
#Mann=5,-1,0
  4591.8    0.05       0  4613.0     0.1       0  4990.5    0.07       0
  4999.8     0.1       0  5157.7    0.05       0
Bank Sta=4990.5,4999.8
Exp/Cntr=0.3,0.1

Type RM Length L Ch R = 1,16125,492,492,492
BEGIN DESCRIPTION:
UNT 059 in RCW 15.0
END DESCRIPTION:
XS GIS Cut Line= 3
      2054440.51     13423681.63      2054625.00     13423125.00
      2054562.14     13421888.20
#Sta/Elev= 30
  4448.2  385.66  4578.1  382.81  4623.7  381.82  4696.5  378.55  4955.4  371.91
  4971.4  371.01  4987.8  368.88  4988.7  368.08  4996.3  368.08  4997.2  368.88
  5013.5  370.67  5024.1  372.40  5032.0  372.75  5144.8  372.27  5174.8  372.96
  5240.0  371.99  5335.1  373.65  5415.1  373.64  5495.2  372.38  5528.7  372.34
  5635.4  373.47  5715.5  372.97  5805.6  374.05  5875.7  373.85  5945.8  374.34
  5985.8  375.14  6065.9  375.15  6126.0  376.07  6206.1  375.69  6273.0  376.56
#Mann=5,-1,0
  4448.2    0.05       0  4578.1     0.1       0  4987.8    0.07       0
  4997.2     0.1       0  5240.0    0.05       0
Bank Sta=4987.8,4997.2
Exp/Cntr=0.3,0.1

Type RM Length L Ch R = 1,15633,470,470,470
BEGIN DESCRIPTION:
UNT 059 in RCW 14.0
END DESCRIPTION:
XS GIS Cut Line= 3
      2054825.00     13424074.99      2054975.00     13423275.00
      2054689.83     13421932.38
#Sta/Elev= 30
  4213.2  400.66  4218.2  400.36  4239.5  398.69  4318.0  396.11  4349.7  395.11
  4417.8  390.13  4454.8  387.74  4565.1  382.93  4681.2  378.52  4762.6  376.48
  4915.2  370.40  4966.1  371.36  4996.1  367.98  4997.0  367.18  5004.6  367.18
  5005.5  367.98  5006.8  368.88  5024.6  370.98  5101.6  372.06  5180.5  371.21
  5313.4  372.20  5339.5  371.20  5344.6  371.87  5374.9  370.20  5405.4  370.22
  5433.6  371.93  5456.5  372.21  5632.1  372.41  5671.2  371.64  6399.7  375.67
#Mann=7,-1,0
  4213.2     0.1       0  4218.2    0.08       0  4318.0    0.05       0
  4417.8     0.1       0  4996.1    0.07       0  5005.5     0.1       0
  5374.9    0.05       0
Bank Sta=4996.1,5005.5
Exp/Cntr=0.3,0.1

Type RM Length L Ch R = 1,15163,67,67,67
BEGIN DESCRIPTION:
Mapping XS 563f4eba
END DESCRIPTION:
XS GIS Cut Line= 6
      2055059.46     13424025.33      2055319.87     13423504.51
      2055351.12     13423330.03      2055299.03     13423244.09
      2055111.53     13423059.20      2054864.40     13422159.11
#Sta/Elev= 30
  4211.2  394.82  4231.6  392.96  4245.1  392.73  4262.6  391.48  4350.5  388.34
  4371.2  387.48  4527.8  381.15  4678.8  376.30  4781.8  371.25  4928.4  368.60
  4973.4  369.06  4995.8  367.69  5012.5  367.60  5013.4  366.80  5021.0  366.80
  5021.9  367.60  5090.2  368.41  5111.4  369.21  5168.0  369.34  5245.8  370.82
  5295.3  370.42  5344.9  371.08  5372.7  370.67  5456.7  371.13  5735.6  371.85
  5794.4  372.48  5849.7  371.66  5932.6  372.39  5982.2  371.76  6270.6  373.59
#Mann=7,-1,0
  4211.2    0.08       0  4262.6    0.05       0  4350.5    0.08       0
  4371.2     0.1       0  5012.5    0.07       0  5021.9     0.1       0
  5456.7    0.05       0
Bank Sta=5012.5,5021.9
Exp/Cntr=0.3,0.1

Type RM Length L Ch R = 1,15096,388,388,388
BEGIN DESCRIPTION:
UNT 059 in RCW 13.0
END DESCRIPTION:
XS GIS Cut Line= 6
      2055082.89     13424046.17      2055408.41     13423486.28
      2055418.83     13423340.45      2055361.53     13423199.82
      2055192.26     13423020.13      2054898.00     13421965.47
#Sta/Elev= 30
  4123.5  394.88  4195.7  390.87  4199.4  390.75  4235.9  388.72  4311.4  386.22
  4380.8  383.05  4594.3  375.77  4680.3  371.50  4888.0  367.76  4888.9  366.96
  4896.6  366.96  4897.5  367.76  4945.5  369.31  4977.2  368.13  5017.6  367.85
  5047.1  368.57  5069.1  368.11  5105.4  369.34  5126.8  368.58  5190.3  370.32
  5226.0  369.50  5296.3  370.36  5390.2  369.97  5653.6  372.51  5766.8  371.25
  5871.6  372.33  5913.2  371.49  6120.8  373.07  6292.0  373.07  6411.0  374.72
#Mann=7,-1,0
  4123.5    0.08       0  4195.7     0.1       0  4199.4    0.08       0
  4311.4     0.1       0  4888.0    0.07       0  4897.5     0.1       0
  5390.2    0.05       0
Bank Sta=4888,4897.5
Exp/Cntr=0.3,0.1

Type RM Length L Ch R = 1,14708,978,978,978
BEGIN DESCRIPTION:
UNT 059 in RCW 12.0
END DESCRIPTION:
XS GIS Cut Line= 4
      2055074.97     13424075.02      2055693.13     13423480.20
      2055949.21     13422681.59      2054815.18     13421458.84
#Sta/Elev= 30
  3910.0  396.22  3969.2  393.27  4043.9  389.53  4181.7  383.58  4235.3  381.46
  4362.7  378.06  4426.2  375.46  4532.5  373.25  4596.0  371.00  4631.5  370.67
  4702.0  368.00  4827.1  367.95  4947.1  368.96  4987.7  367.76  5049.7  368.08
  5277.4  367.69  5278.3  366.89  5286.0  366.89  5286.9  367.69  5342.3  368.09
  5474.9  369.07  5512.3  368.01  5562.6  367.73  5593.7  367.84  5611.6  367.80
  5698.9  367.72  5734.6  369.22  5833.7  370.30  6619.0  373.42  7274.2  378.42
#Mann=12,-1,0
  3910.0    0.08       0  3969.2     0.1       0  4043.9    0.08       0
  4181.7     0.1       0  4947.1    0.07       0  5049.7    0.05       0
  5277.4    0.07       0  5286.9    0.05       0  5342.3     0.1       0
  5562.6    0.05       0  5593.7     0.1       0  5611.6    0.05       0
Bank Sta=5277.4,5286.9
Exp/Cntr=0.3,0.1