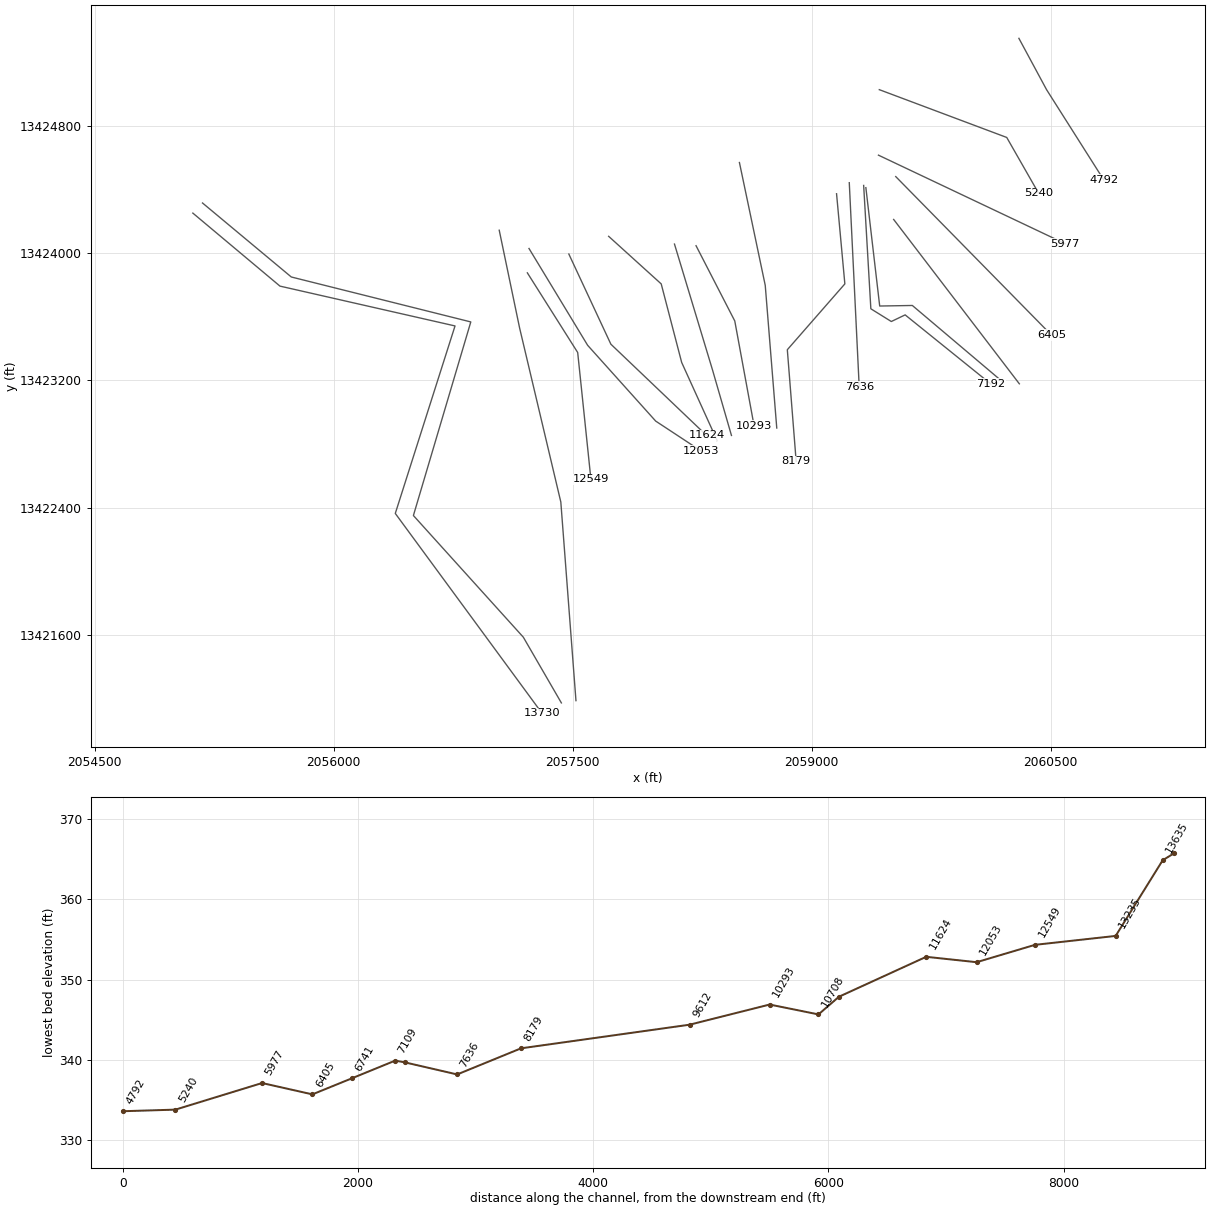
HEC-RAS study UNT 059 in RCW.prj: UNT 059 in RCW Base Level Engineering

--- UNT 059 in RCW.g01 (geometry) --- (continued)

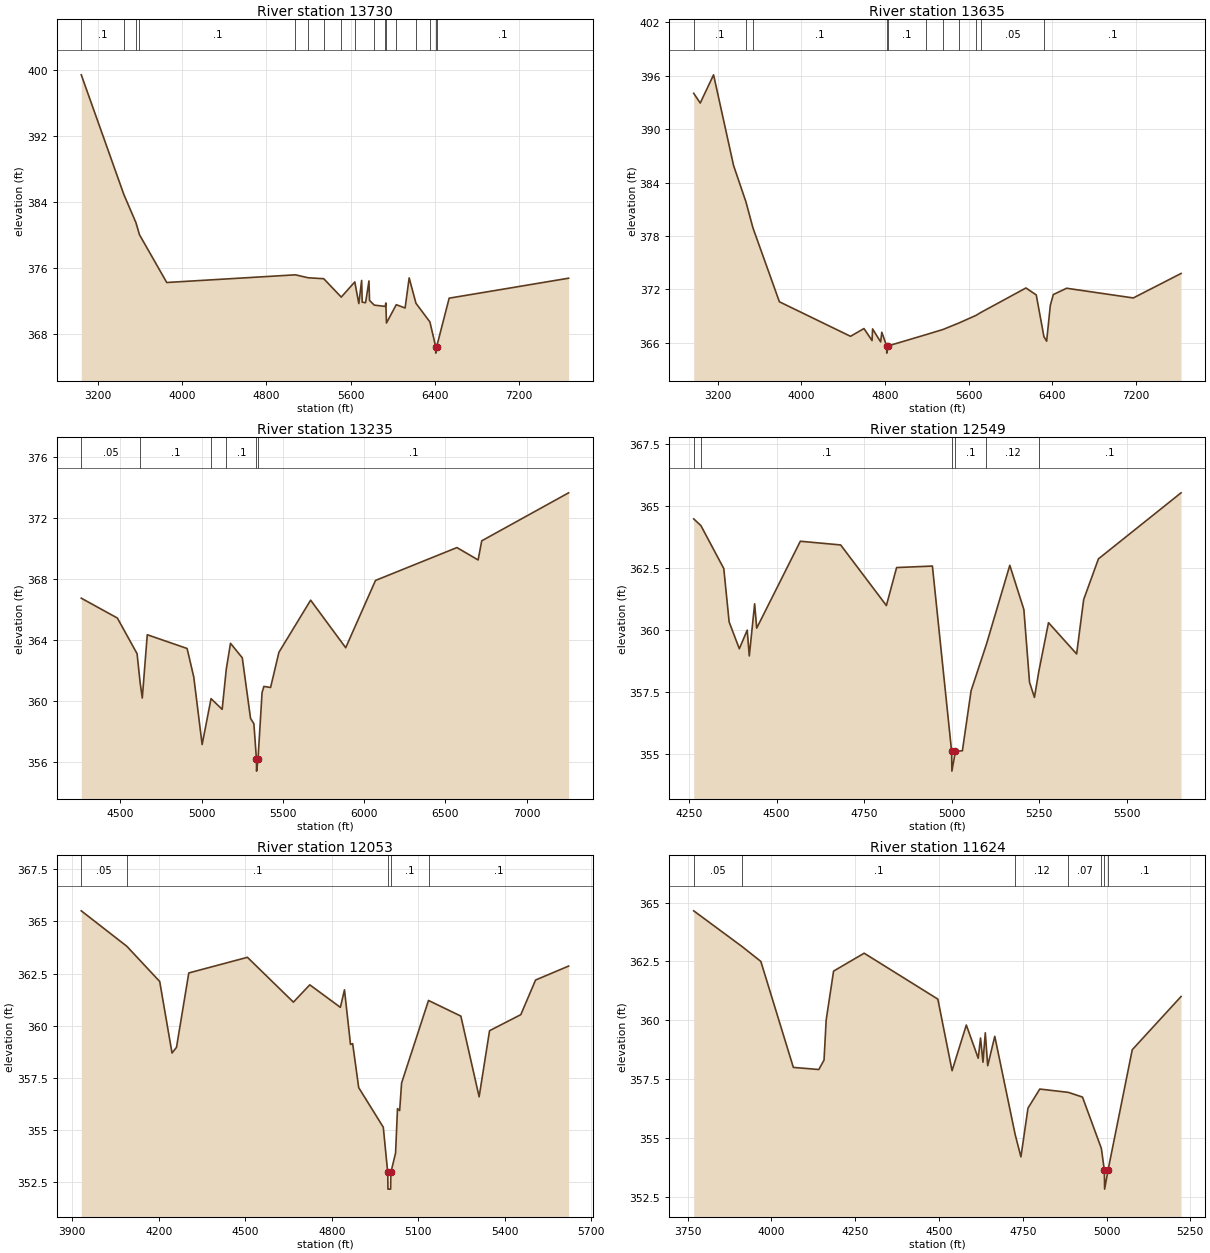
Type RM Length L Ch R = 1,13730,95,95,95
BEGIN DESCRIPTION:
UNT 059 in RCW 11.0
END DESCRIPTION:
XS GIS Cut Line= 5
      2055115.89     13424250.15      2055662.75     13423791.84
      2056761.71     13423541.84      2056386.71     13422364.75
      2057308.41     13421109.78
#Sta/Elev= 30
  3039.6  399.43  3444.5  384.92  3559.5  381.51  3592.5  380.06  3852.2  374.26
  5075.1  375.19  5197.5  374.83  5344.7  374.72  5511.2  372.49  5639.9  374.33
  5678.1  371.70  5705.0  374.51  5710.3  371.88  5742.5  371.81  5774.7  374.45
  5780.0  372.09  5825.0  371.52  5929.6  371.36  5935.0  371.78  5941.0  369.35
  6034.2  371.57  6118.3  371.17  6156.8  374.82  6221.6  371.74  6353.9  369.48
  6408.8  366.50  6409.8  365.70  6418.6  366.50  6537.1  372.36  7672.6  374.78
#Mann=17,-1,0
  3039.6     0.1       0  3444.5    0.08       0  3559.5    0.05       0
  3592.5     0.1       0  5075.1    0.05       0  5197.5     0.1       0
  5344.7    0.05       0  5511.2     0.1       0  5639.9    0.05       0
  5825.0     0.1       0  5929.6    0.05       0  5935.0    0.07       0
  6034.2     0.1       0  6221.6    0.05       0  6353.9     0.1       0
  6408.8    0.07       0  6418.6     0.1       0
Bank Sta=6408.8,6418.6
Exp/Cntr=0.3,0.1

Type RM Length L Ch R = 1,13635,400,400,400
BEGIN DESCRIPTION:
UNT 059 in RCW 10.0
END DESCRIPTION:
XS GIS Cut Line= 6
      2055176.64     13424313.54      2055733.93     13423849.13
      2056860.67     13423567.01      2056500.42     13422351.73
      2057190.53     13421587.84      2057429.25     13421175.51
#Sta/Elev= 30
  2971.7  394.04  3033.9  392.95  3161.5  396.12  3352.8  385.93  3470.4  381.87
  3537.9  378.93  3791.0  370.62  4471.0  366.74  4599.8  367.61  4677.0  366.26
  4682.2  367.57  4759.4  366.11  4770.3  367.20  4817.0  365.65  4817.9  364.85
  4826.8  365.65  5197.1  366.94  5356.3  367.51  5508.7  368.24  5669.4  369.08
  5716.4  369.41  6148.7  372.17  6247.4  371.39  6320.8  366.70  6346.7  366.19
  6381.9  370.21  6410.3  371.43  6538.0  372.14  7175.4  371.05  7632.1  373.80
#Mann=11,-1,0
  2971.7     0.1       0  3470.4    0.05       0  3537.9     0.1       0
  4817.0    0.07       0  4826.8     0.1       0  5197.1    0.05       0
  5356.3     0.1       0  5508.7    0.05       0  5669.4     0.1       0
  5716.4    0.05       0  6320.8     0.1       0
Bank Sta=4817,4826.8
Exp/Cntr=0.3,0.1

Type RM Length L Ch R = 1,13235,686,686,686
BEGIN DESCRIPTION:
Mapping XS 98c47a65
END DESCRIPTION:
XS GIS Cut Line= 4
      2057039.14     13424142.66      2057167.18     13423528.54
      2057425.83     13422436.42      2057520.88     13421189.59
#Sta/Elev= 30
  4258.7  366.74  4481.0  365.44  4602.2  363.11  4621.2  361.20  4634.3  360.21
  4664.9  364.35  4910.2  363.45  4951.3  361.58  5002.7  357.17  5057.6  360.17
  5126.0  359.47  5151.5  362.11  5177.4  363.79  5249.9  362.84  5300.7  358.88
  5321.3  358.53  5336.9  356.23  5337.9  355.43  5346.8  356.23  5371.6  360.56
  5382.9  360.97  5424.1  360.90  5475.4  363.20  5670.7  366.61  5886.5  363.50
  6070.0  367.90  6571.4  370.05  6701.8  369.24  6723.9  370.49  7258.8  373.63
#Mann=6,-1,0
  4258.7    0.05       0  4621.2     0.1       0  5057.6    0.07       0
  5151.5     0.1       0  5336.9    0.07       0  5346.8     0.1       0
Bank Sta=5336.9,5346.8
Exp/Cntr=0.3,0.1

Type RM Length L Ch R = 1,12549,496,496,496
BEGIN DESCRIPTION:
Mapping XS 2ca16296
END DESCRIPTION:
XS GIS Cut Line= 3
      2057215.71     13423875.15      2057531.67     13423375.17
      2057614.83     13422578.25
#Sta/Elev= 30
  4263.1  364.48  4283.6  364.21  4349.0  362.48  4364.3  360.33  4393.4  359.25
  4416.0  360.00  4421.9  358.96  4437.2  361.06  4443.1  360.08  4567.8  363.58
  4683.1  363.43  4813.7  360.99  4842.9  362.52  4945.2  362.58  5000.1  355.12
  5000.9  354.32  5011.0  355.12  5030.9  355.14  5055.8  357.56  5099.8  359.44
  5166.4  362.61  5206.6  360.83  5222.8  357.90  5236.8  357.29  5249.4  358.34
  5277.0  360.30  5357.4  359.04  5377.5  361.23  5419.7  362.87  5655.8  365.53
#Mann=6,-1,0
  4263.1    0.05       0  4283.6     0.1       0  5000.1    0.07       0
  5011.0     0.1       0  5099.8    0.12       0  5249.4     0.1       0
Bank Sta=5000.1,5011
Exp/Cntr=0.3,0.1

Type RM Length L Ch R = 1,12053,429,429,429
BEGIN DESCRIPTION:
Mapping XS 5c7f0abb
END DESCRIPTION:
XS GIS Cut Line= 4
      2057226.10     13424027.97      2057594.17     13423420.31
      2058021.26     13422944.61      2058305.94     13422757.14
#Sta/Elev= 30
  3931.1  365.51  4089.1  363.81  4203.2  362.12  4245.9  358.69  4261.4  358.96
  4304.1  362.53  4507.5  363.28  4667.0  361.13  4723.8  361.96  4830.0  360.88
  4844.2  361.72  4865.1  359.10  4872.6  359.14  4893.5  357.03  4978.8  355.13
  4994.2  352.96  4995.0  352.16  5004.3  352.16  5005.1  352.96  5021.4  353.89
  5028.1  356.02  5035.6  355.93  5042.3  357.25  5135.7  361.21  5247.9  360.46
  5311.3  356.59  5347.5  359.76  5455.9  360.53  5507.1  362.19  5621.7  362.86
#Mann=5,-1,0
  3931.1    0.05       0  4089.1     0.1       0  4994.2    0.07       0
  5005.1     0.1       0  5135.7     0.1       0
Bank Sta=4994.2,5005.1
Exp/Cntr=0.3,0.1

Type RM Length L Ch R = 1,11624,742,742,742
BEGIN DESCRIPTION:
Mapping XS caec6862
END DESCRIPTION:
XS GIS Cut Line= 3
      2057476.13     13423993.21      2057740.01     13423427.25
      2058340.37     13422854.65
#Sta/Elev= 30
  3768.1  364.65  3912.6  363.13  3968.4  362.50  4065.4  358.00  4141.3  357.91
  4156.9  358.31  4163.3  360.01  4185.4  362.09  4276.7  362.85  4496.5  360.90
  4539.0  357.86  4581.5  359.80  4617.0  358.39  4623.9  359.25  4631.2  358.22
  4638.1  359.47  4645.3  358.07  4666.4  359.32  4727.2  355.15  4744.4  354.20
  4765.5  356.27  4800.7  357.08  4885.9  356.94  4928.1  356.74  4984.4  354.56
  4993.4  353.63  4994.1  352.83  5004.3  353.63  5076.6  358.75  5222.2  361.01
#Mann=7,-1,0
  3768.1    0.05       0  3912.6     0.1       0  4727.2    0.12       0
  4885.9    0.07       0  4984.4     0.1       0  4993.4    0.07       0
  5004.3     0.1       0
Bank Sta=4993.4,5004.3
Exp/Cntr=0.3,0.1

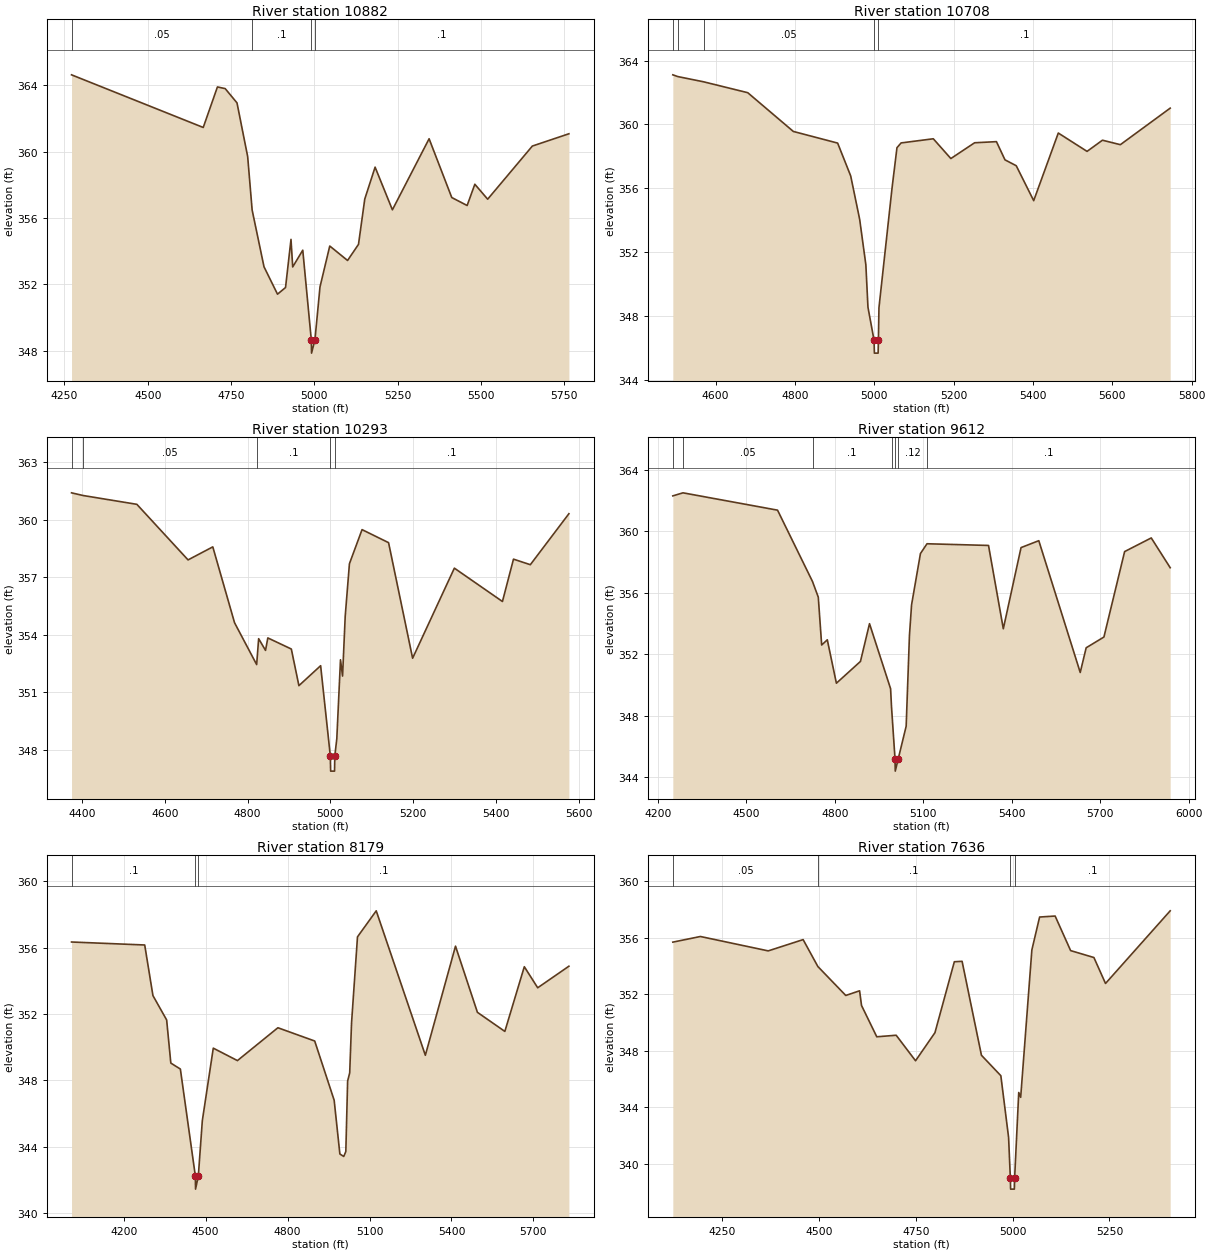
Type RM Length L Ch R = 1,10882,174,174,174
BEGIN DESCRIPTION:
Mapping XS fa8e5524
END DESCRIPTION:
XS GIS Cut Line= 4
      2057726.12     13424104.34      2058055.98     13423805.73
      2058184.45     13423312.67      2058406.66     13422823.11
#Sta/Elev= 30
  4271.4  364.62  4666.5  361.45  4709.1  363.89  4732.4  363.79  4767.8  362.93
  4799.8  359.70  4813.2  356.48  4848.8  353.06  4889.3  351.41  4913.4  351.81
  4929.8  354.71  4934.9  353.05  4965.1  354.06  4990.7  348.66  4991.4  347.86
  5001.6  348.66  5016.8  351.85  5046.1  354.31  5099.5  353.44  5132.3  354.41
  5151.1  357.14  5182.1  359.06  5234.0  356.49  5344.1  360.77  5412.1  357.23
  5458.2  356.75  5481.3  358.03  5519.8  357.13  5653.8  360.33  5763.5  361.07
#Mann=4,-1,0
  4271.4    0.05       0  4813.2     0.1       0  4990.7    0.07       0
  5001.6     0.1       0
Bank Sta=4990.7,5001.6
Exp/Cntr=0.3,0.1

Type RM Length L Ch R = 1,10708,415,415,415
BEGIN DESCRIPTION:
UNT 059 in RCW 9.0
END DESCRIPTION:
XS GIS Cut Line= 3
      2058139.30     13424055.76      2058378.57     13423263.84
      2058496.94     13422854.38
#Sta/Elev= 30
  4492.4  363.11  4505.0  363.00  4570.4  362.67  4681.2  361.99  4796.1  359.56
  4907.8  358.83  4940.7  356.77  4963.3  354.05  4978.9  351.20  4984.2  348.54
  4999.6  346.46  5000.4  345.66  5009.8  345.66  5010.5  346.46  5011.9  348.50
  5044.8  355.99  5057.3  358.54  5067.7  358.84  5148.9  359.10  5193.1  357.86
  5253.0  358.85  5308.0  358.92  5329.5  357.78  5357.9  357.41  5401.9  355.22
  5463.9  359.46  5536.4  358.31  5575.2  359.01  5620.3  358.73  5745.9  361.02
#Mann=5,-1,0
  4492.4    0.05       0  4505.0     0.1       0  4570.4    0.05       0
  4999.6    0.03       0  5010.5     0.1       0
Bank Sta=4999.6,5010.5
Exp/Cntr=0.3,0.1

Type RM Length L Ch R = 1,10293,681,681,681
BEGIN DESCRIPTION:
Mapping XS dfdd4414
END DESCRIPTION:
XS GIS Cut Line= 3
      2058274.71     13424045.35      2058517.78     13423573.09
      2058639.32     13422913.34
#Sta/Elev= 30
  4374.7  361.41  4402.6  361.27  4532.6  360.81  4656.3  357.91  4716.1  358.59
  4768.7  354.63  4822.1  352.45  4826.9  353.80  4843.5  353.19  4849.1  353.84
  4905.9  353.26  4924.2  351.35  4976.7  352.39  5000.1  347.69  5000.9  346.89
  5010.3  346.89  5011.0  347.69  5015.8  348.58  5024.7  352.70  5029.7  351.85
  5036.1  354.97  5046.3  357.71  5076.8  359.49  5140.9  358.81  5199.0  352.78
  5299.9  357.48  5416.1  355.74  5442.8  357.95  5483.5  357.66  5576.7  360.32
#Mann=5,-1,0
  4374.7     0.1       0  4402.6    0.05       0  4822.1     0.1       0
  5000.1    0.07       0  5011.0     0.1       0
Bank Sta=5000.1,5011
Exp/Cntr=0.3,0.1

Type RM Length L Ch R = 1,9612,1433,1433,1433
BEGIN DESCRIPTION:
UNT 059 in RCW 8.0
END DESCRIPTION:
XS GIS Cut Line= 3
      2058546.98     13424567.63      2058709.03     13423796.53
      2058781.35     13422900.99
#Sta/Elev= 30
  4251.1  362.32  4285.6  362.52  4606.2  361.39  4724.7  356.74  4744.3  355.72
  4755.8  352.60  4774.9  352.94  4805.7  350.11  4887.3  351.53  4918.0  353.99
  4989.5  349.75  4992.6  348.57  5004.5  345.18  5005.3  344.38  5015.4  345.18
  5042.3  347.31  5053.4  353.21  5060.6  355.22  5090.7  358.56  5112.9  359.20
  5321.5  359.09  5371.7  353.66  5431.8  358.95  5492.0  359.40  5632.5  350.81
  5652.6  352.42  5712.8  353.12  5783.0  358.69  5873.3  359.58  5937.5  357.64
#Mann=7,-1,0
  4251.1     0.1       0  4285.6    0.05       0  4724.7     0.1       0
  4992.6    0.12       0  5004.5    0.07       0  5015.4    0.12       0
  5112.9     0.1       0
Bank Sta=5004.5,5015.4
Exp/Cntr=0.3,0.1

Type RM Length L Ch R = 1,8179,543,543,543
BEGIN DESCRIPTION:
Mapping XS 2013079d
END DESCRIPTION:
XS GIS Cut Line= 4
      2059156.67     13424371.74      2059208.76     13423805.73
      2058847.64     13423392.53      2058903.20     13422691.19
#Sta/Elev= 30
  4009.2  356.34  4277.1  356.16  4307.2  353.11  4357.4  351.64  4372.7  349.04
  4407.6  348.68  4462.4  342.24  4463.2  341.44  4473.4  342.24  4488.0  345.57
  4528.1  349.94  4616.5  349.19  4764.6  351.17  4899.4  350.37  4970.6  346.80
  4991.5  343.56  5005.7  343.41  5013.3  343.71  5019.9  347.96  5027.5  348.45
  5034.2  351.45  5056.0  356.65  5124.6  358.22  5304.4  349.51  5414.8  356.09
  5495.0  352.10  5595.4  350.95  5666.7  354.85  5715.7  353.58  5829.9  354.88
#Mann=3,-1,0
  4009.2     0.1       0  4462.4    0.07       0  4473.4     0.1       0
Bank Sta=4462.4,4473.4
Exp/Cntr=0.3,0.1

Type RM Length L Ch R = 1,7636,444,444,444
BEGIN DESCRIPTION:
Mapping XS dbd209d6
END DESCRIPTION:
XS GIS Cut Line= 2
      2059236.54     13424441.10      2059298.95     13423158.22
#Sta/Elev= 30
  4122.4  355.70  4193.6  356.10  4368.8  355.08  4458.9  355.88  4497.0  353.97
  4569.0  351.92  4604.7  352.25  4609.7  351.21  4649.1  348.99  4699.2  349.10
  4749.2  347.29  4799.3  349.28  4849.4  354.31  4869.4  354.34  4919.4  347.68
  4969.5  346.23  4989.5  341.85  4994.0  338.99  4994.7  338.19  5004.4  338.19
  5005.1  338.99  5015.7  345.04  5020.7  344.70  5049.6  355.15  5069.6  357.48
  5109.7  357.55  5149.7  355.10  5209.8  354.61  5239.8  352.77  5406.8  357.92
#Mann=4,-1,0
  4122.4    0.05       0  4497.0     0.1       0  4994.0    0.07       0
  5005.1     0.1       0
Bank Sta=4994,5005.1
Exp/Cntr=0.3,0.1

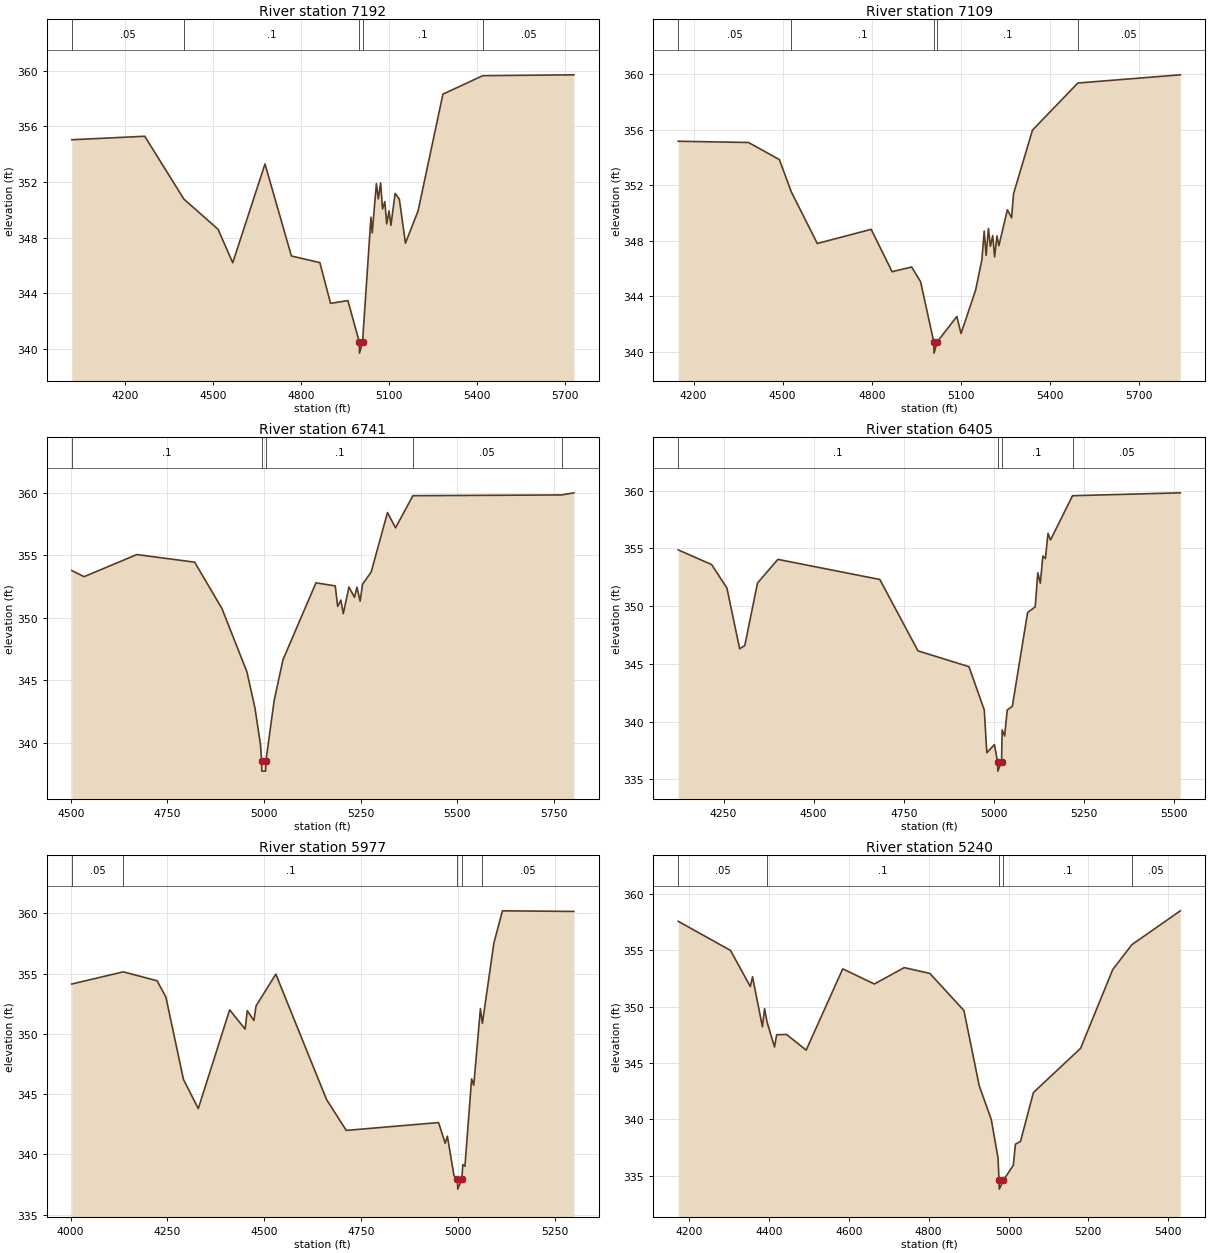
Type RM Length L Ch R = 1,7192,83,83,83
BEGIN DESCRIPTION:
Mapping XS ffb7f35b
END DESCRIPTION:
XS GIS Cut Line= 5
      2059326.81     13424423.75      2059371.95     13423649.48
      2059500.42     13423569.61      2059587.23     13423611.28
      2060125.46     13423177.22
#Sta/Elev= 30
  4016.7  355.04  4265.9  355.29  4399.6  350.77  4516.3  348.60  4566.4  346.19
  4676.6  353.30  4766.7  346.68  4863.9  346.20  4900.5  343.27  4959.7  343.47
  4998.6  340.49  4999.3  339.69  5009.7  340.49  5038.4  349.47  5042.7  348.34
  5057.0  351.88  5063.5  350.78  5071.4  351.94  5077.9  350.06  5085.8  350.59
  5092.2  348.98  5100.2  349.92  5106.6  348.88  5121.0  351.18  5135.4  350.76
  5156.2  347.60  5199.4  349.92  5284.2  358.32  5420.4  359.65  5731.3  359.71
#Mann=5,-1,0
  4016.7    0.05       0  4399.6     0.1       0  4998.6    0.07       0
  5009.7     0.1       0  5420.4    0.05       0
Bank Sta=4998.6,5009.7
Exp/Cntr=0.3,0.1

Type RM Length L Ch R = 1,7109,368,368,368
BEGIN DESCRIPTION:
Mapping XS f253418c
END DESCRIPTION:
XS GIS Cut Line= 4
      2059340.70     13424409.88      2059427.51     13423666.84
      2059632.37     13423670.31      2060194.90     13423194.59
#Sta/Elev= 30
  4148.6  355.16  4385.1  355.07  4489.0  353.84  4529.1  351.52  4616.6  347.80
  4797.9  348.82  4868.3  345.77  4934.2  346.11  4964.2  345.05  5008.7  340.71
  5009.4  339.91  5019.8  340.71  5086.3  342.55  5100.4  341.32  5149.7  344.47
  5170.5  346.63  5178.3  348.69  5184.8  346.95  5192.6  348.88  5199.1  347.59
  5206.9  348.37  5213.4  346.84  5221.2  348.34  5227.7  347.64  5256.3  350.22
  5270.6  349.65  5277.1  351.38  5340.8  355.96  5493.4  359.35  5838.3  359.94
#Mann=5,-1,0
  4148.6    0.05       0  4529.1     0.1       0  5008.7    0.07       0
  5019.8     0.1       0  5493.4    0.05       0
Bank Sta=5008.7,5019.8
Exp/Cntr=0.3,0.1

Type RM Length L Ch R = 1,6741,336,336,336
BEGIN DESCRIPTION:
Mapping XS 919ead23
END DESCRIPTION:
XS GIS Cut Line= 2
      2059515.16     13424210.27      2060304.05     13423178.63
#Sta/Elev= 30
  4502.7  353.76  4534.5  353.27  4671.0  355.04  4820.6  354.43  4891.3  350.71
  4955.7  345.66  4976.5  342.77  4991.0  339.80  4993.7  338.51  4994.4  337.71
  5004.1  337.71  5004.8  338.51  5026.4  343.39  5049.1  346.63  5134.4  352.78
  5184.2  352.53  5190.5  350.89  5198.8  351.40  5205.0  350.31  5219.6  352.44
  5234.1  351.62  5240.4  352.43  5248.6  351.31  5254.9  352.66  5277.2  353.64
  5319.3  358.40  5340.2  357.18  5385.1  359.75  5769.7  359.81  5801.4  359.98
#Mann=5,-1,0
  4502.7     0.1       0  4993.7    0.07       0  5004.8     0.1       0
  5385.1    0.05       0  5769.7     0.1       0
Bank Sta=4993.7,5004.8
Exp/Cntr=0.3,0.1

Type RM Length L Ch R = 1,6405,428,428,428
BEGIN DESCRIPTION:
Mapping XS fd501f1b
END DESCRIPTION:
XS GIS Cut Line= 2
      2059528.21     13424479.33      2060504.78     13423485.40
#Sta/Elev= 30
  4124.1  354.86  4216.8  353.59  4259.2  351.56  4294.6  346.30  4308.8  346.58
  4344.1  351.99  4400.6  354.04  4683.5  352.30  4789.5  346.12  4931.0  344.75
  4973.4  341.01  4980.5  337.30  5001.7  338.01  5010.3  336.51  5011.0  335.71
  5021.4  336.51  5023.0  339.28  5030.0  338.75  5037.1  341.00  5051.3  341.32
  5093.7  349.44  5114.8  349.93  5122.0  352.87  5129.0  351.98  5136.1  354.33
  5143.1  354.11  5150.3  356.29  5157.3  355.72  5218.4  359.55  5517.5  359.80
#Mann=4,-1,0
  4124.1     0.1       0  5010.3    0.07       0  5021.4     0.1       0
  5218.4    0.05       0
Bank Sta=5010.3,5021.4
Exp/Cntr=0.3,0.1

Type RM Length L Ch R = 1,5977,737,737,737
BEGIN DESCRIPTION:
Mapping XS 15a67380
END DESCRIPTION:
XS GIS Cut Line= 2
      2059419.73     13424613.87      2060591.61     13424058.31
#Sta/Elev= 30
  4002.8  354.13  4135.9  355.14  4223.2  354.40  4245.9  353.05  4291.4  346.21
  4329.6  343.80  4410.6  351.99  4450.6  350.39  4456.1  351.92  4473.3  351.10
  4478.8  352.31  4529.9  354.95  4660.8  344.56  4711.8  341.99  4950.2  342.64
  4967.4  340.92  4973.0  341.51  4990.2  338.23  4999.1  337.92  4999.8  337.12
  5010.2  337.92  5012.9  339.15  5018.4  339.02  5035.6  346.26  5041.2  345.74
  5058.4  352.09  5063.5  350.87  5093.2  357.54  5115.3  360.20  5299.7  360.15
#Mann=5,-1,0
  4002.8    0.05       0  4135.9     0.1       0  4999.1    0.07       0
  5010.2     0.1       0  5063.5    0.05       0
Bank Sta=4999.1,5010.2
Exp/Cntr=0.3,0.1

Type RM Length L Ch R = 1,5240,448,448,448
BEGIN DESCRIPTION:
UNT 059 in RCW 6.0
END DESCRIPTION:
XS GIS Cut Line= 3
      2059425.04     13425024.99      2060225.00     13424725.00
      2060425.01     13424374.98
#Sta/Elev= 30
  4172.8  357.57  4303.6  354.99  4353.4  351.78  4358.8  352.65  4383.7  348.21
  4389.0  349.83  4395.4  348.61  4414.0  346.42  4419.3  347.51  4444.2  347.53
  4493.2  346.14  4584.8  353.35  4664.0  352.01  4738.8  353.46  4802.9  352.95
  4888.3  349.66  4926.6  342.99  4956.9  339.98  4973.8  336.57  4976.2  334.61
  4976.9  333.81  4987.4  334.61  5012.0  335.93  5017.4  337.80  5030.0  338.04
  5062.4  342.38  5180.5  346.30  5261.1  353.29  5309.0  355.50  5430.3  358.50
#Mann=5,-1,0
  4172.8    0.05       0  4395.4     0.1       0  4976.2    0.07       0
  4987.4     0.1       0  5309.0    0.05       0
Bank Sta=4976.2,4987.4
Exp/Cntr=0.3,0.1

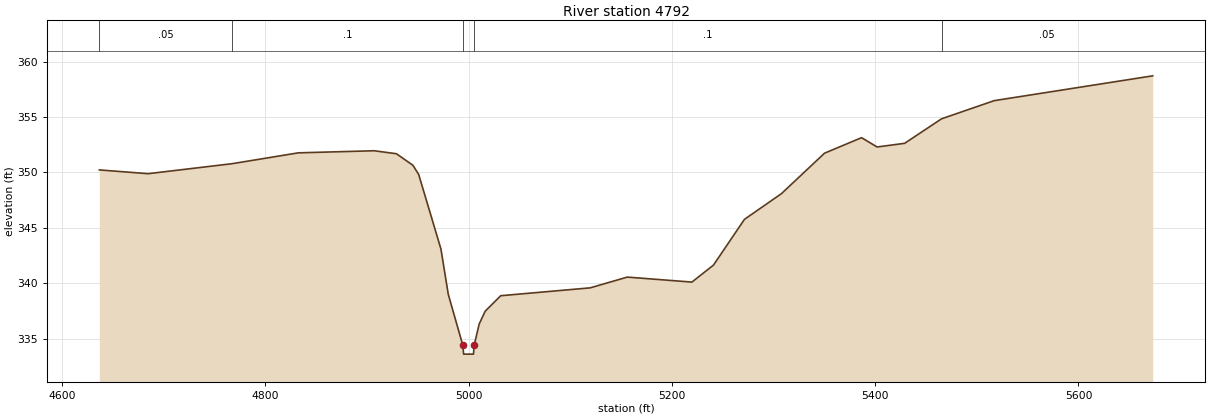
Type RM Length L Ch R = 1,4792,800,800,800
BEGIN DESCRIPTION:
UNT 059 in RCW 5.0
END DESCRIPTION:
XS GIS Cut Line= 3
      2060301.29     13425347.22      2060475.00     13425025.00
      2060833.88     13424458.82
#Sta/Elev= 30
  4636.7  350.23  4684.7  349.89  4767.2  350.79  4832.4  351.77  4907.1  351.96
  4929.0  351.69  4945.2  350.65  4950.9  349.82  4972.8  343.09  4980.0  339.01
  4994.3  334.41  4995.1  333.61  5004.8  333.61  5005.5  334.41  5010.4  336.32
  5016.3  337.48  5031.6  338.88  5119.7  339.59  5156.1  340.56  5219.7  340.11
  5240.9  341.64  5271.4  345.77  5307.8  348.09  5350.2  351.74  5386.6  353.14
  5401.9  352.30  5429.0  352.63  5465.3  354.84  5517.1  356.48  5673.1  358.72
#Mann=5,-1,0
  4636.7    0.05       0  4767.2     0.1       0  4994.3    0.07       0
  5005.5     0.1       0  5465.3    0.05       0
Bank Sta=4994.3,5005.5
Exp/Cntr=0.3,0.1