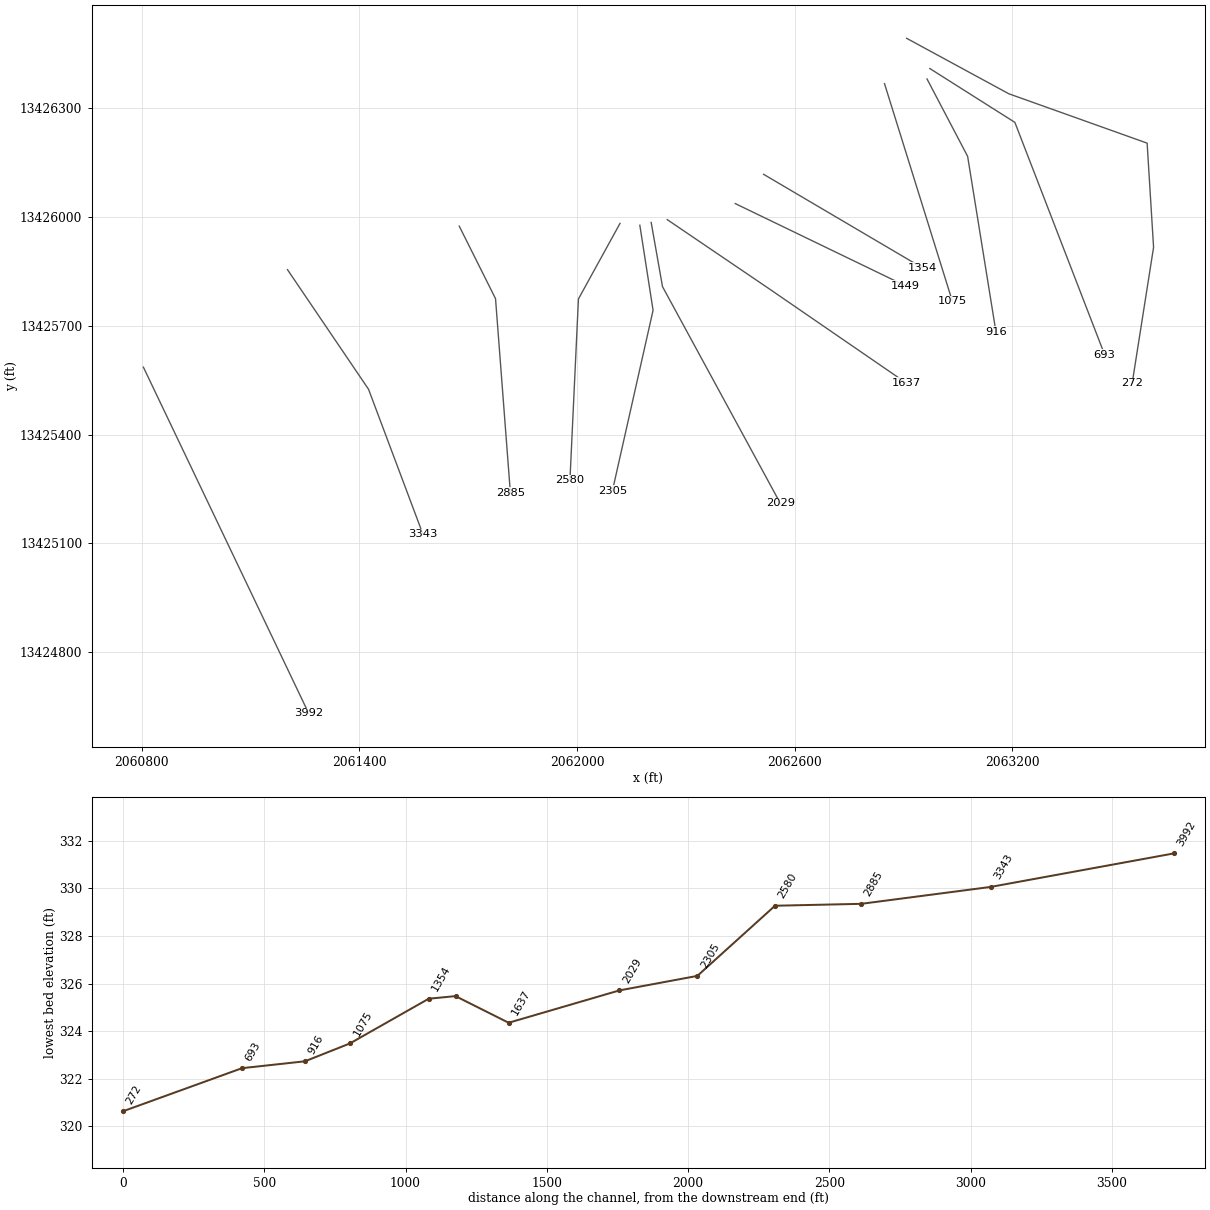
HEC-RAS study UNT 059 in RCW.prj: UNT 059 in RCW Base Level Engineering

--- UNT 059 in RCW.g01 (geometry) --- (continued)

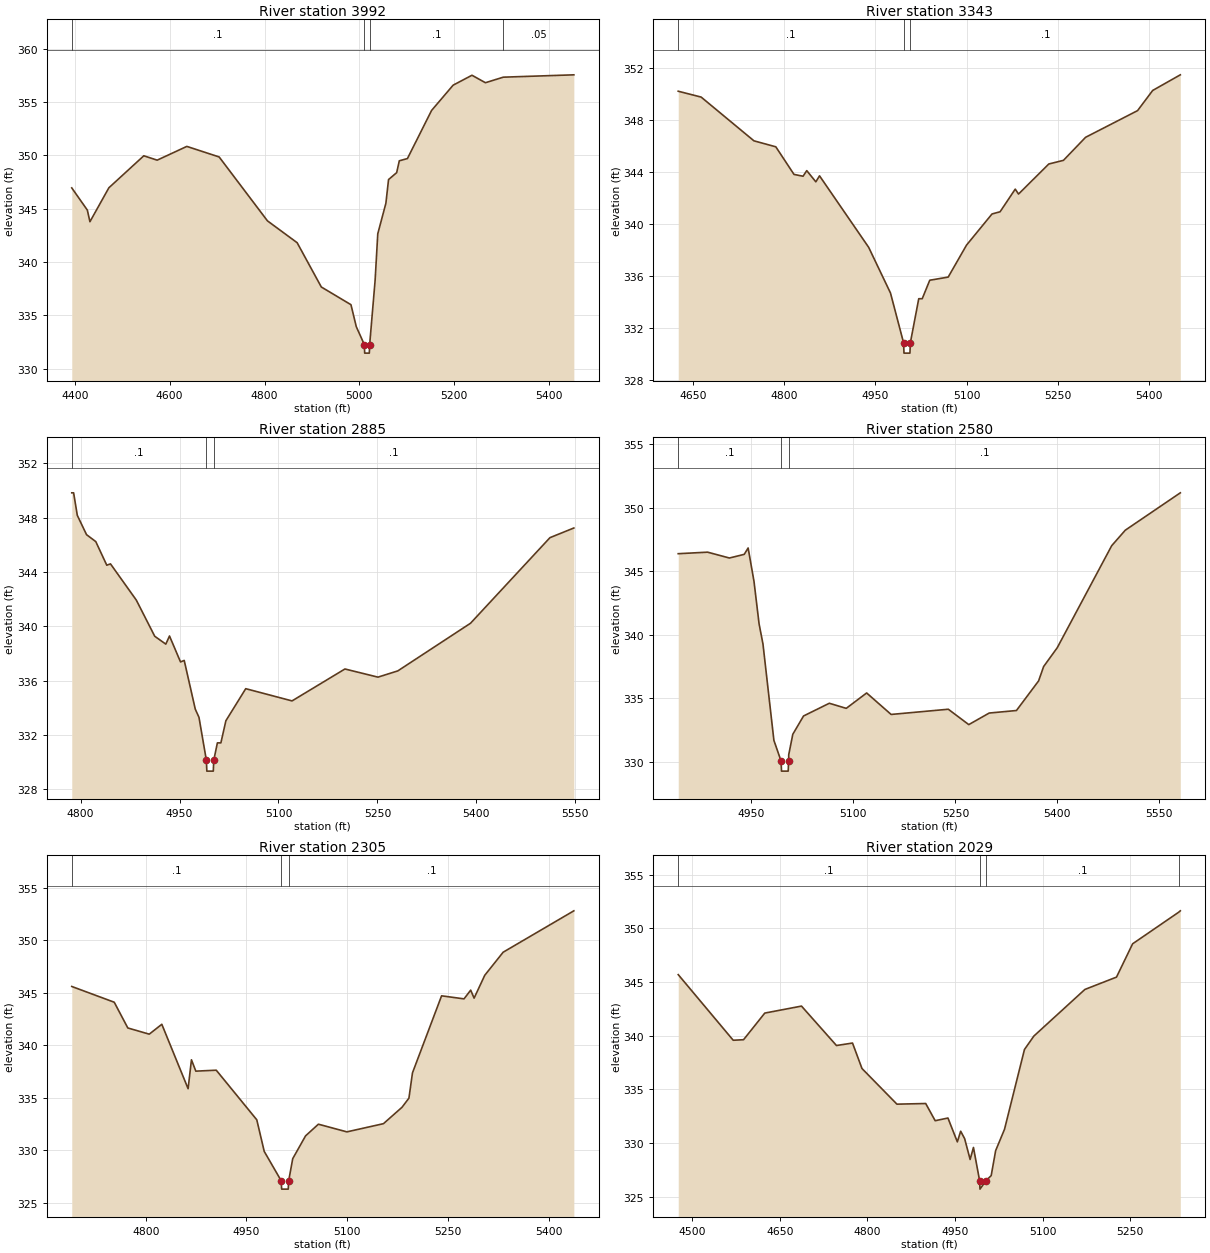
Type RM Length L Ch R = 1,3992,649,649,649
BEGIN DESCRIPTION:
Mapping XS 1cafab14
END DESCRIPTION:
XS GIS Cut Line= 2
      2060804.22     13425586.15      2061259.98     13424631.24
#Sta/Elev= 30
  4393.8  346.96  4426.6  344.88  4432.1  343.79  4472.0  346.97  4545.6  349.97
  4573.8  349.56  4636.3  350.85  4704.4  349.86  4806.2  343.87  4868.8  341.82
  4919.7  337.67  4982.2  336.01  4993.4  333.95  5010.4  332.27  5011.1  331.47
  5020.9  331.47  5021.6  332.27  5033.1  338.30  5038.7  342.66  5055.8  345.52
  5061.4  347.74  5078.5  348.39  5084.1  349.50  5101.2  349.71  5152.1  354.22
  5197.5  356.59  5237.2  357.52  5265.6  356.82  5303.2  357.34  5451.9  357.56
#Mann=4,-1,0
  4393.8     0.1       0  5010.4    0.07       0  5021.6     0.1       0
  5303.2    0.05       0
Bank Sta=5010.4,5021.6
Exp/Cntr=0.3,0.1

Type RM Length L Ch R = 1,3343,458,458,458
BEGIN DESCRIPTION:
UNT 059 in RCW 4.0
END DESCRIPTION:
XS GIS Cut Line= 3
      2061201.47     13425855.02      2061425.00     13425525.00
      2061575.00     13425125.00
#Sta/Elev= 30
  4625.7  350.18  4663.4  349.73  4750.2  346.37  4786.2  345.91  4816.1  343.79
  4831.0  343.65  4837.1  344.08  4852.0  343.22  4858.1  343.68  4938.9  338.19
  4974.8  334.68  4996.3  330.86  4997.0  330.06  5006.8  330.06  5007.5  330.86
  5021.3  334.24  5027.0  334.24  5039.4  335.66  5069.7  335.90  5099.9  338.36
  5141.8  340.75  5155.1  340.92  5180.0  342.66  5185.4  342.28  5235.2  344.59
  5259.3  344.87  5295.7  346.64  5381.2  348.69  5406.1  350.24  5451.5  351.44
#Mann=3,-1,0
  4625.7     0.1       0  4996.3    0.07       0  5007.5     0.1       0
Bank Sta=4996.3,5007.5
Exp/Cntr=0.3,0.1

Type RM Length L Ch R = 1,2885,305,305,305
BEGIN DESCRIPTION:
UNT 059 in RCW 3.0
END DESCRIPTION:
XS GIS Cut Line= 3
      2061674.98     13425975.03      2061775.00     13425775.00
      2061815.98     13425238.90
#Sta/Elev= 30
  4786.6  349.84  4789.4  349.84  4795.0  348.18  4809.0  346.76  4823.0  346.25
  4839.7  344.51  4845.3  344.61  4884.5  341.94  4912.4  339.28  4929.2  338.70
  4934.8  339.30  4951.5  337.39  4957.1  337.50  4973.9  333.91  4979.5  333.31
  4990.7  330.15  4991.4  329.35  5001.2  329.35  5001.9  330.15  5007.4  331.43
  5012.7  331.43  5020.3  333.06  5050.4  335.42  5120.6  334.52  5200.8  336.87
  5250.9  336.27  5281.0  336.73  5391.3  340.24  5511.7  346.54  5547.9  347.25
#Mann=3,-1,0
  4786.6     0.1       0  4990.7    0.07       0  5001.9     0.1       0
Bank Sta=4990.7,5001.9
Exp/Cntr=0.3,0.1

Type RM Length L Ch R = 1,2580,275,275,275
BEGIN DESCRIPTION:
Mapping XS 4e8312b8
END DESCRIPTION:
XS GIS Cut Line= 3
      2062118.17     13425982.63      2062003.57     13425774.26
      2061980.13     13425274.22
#Sta/Elev= 30
  4842.4  346.38  4885.6  346.50  4917.7  346.04  4939.5  346.33  4945.2  346.83
  4953.8  344.21  4961.3  340.86  4967.0  339.28  4983.1  331.69  4993.6  330.07
  4994.3  329.27  5004.1  329.27  5004.8  330.07  5004.9  330.56  5010.9  332.17
  5026.7  333.61  5064.6  334.61  5089.5  334.21  5119.5  335.42  5155.5  333.73
  5239.6  334.14  5269.7  332.93  5299.7  333.84  5339.8  334.04  5372.4  336.37
  5379.8  337.50  5399.8  338.98  5479.9  347.01  5499.9  348.23  5580.8  351.17
#Mann=3,-1,0
  4842.4     0.1       0  4993.6    0.07       0  5004.8     0.1       0
Bank Sta=4993.6,5004.8
Exp/Cntr=0.3,0.1

Type RM Length L Ch R = 1,2305,276,276,276
BEGIN DESCRIPTION:
Mapping XS ee0f14ad
END DESCRIPTION:
XS GIS Cut Line= 3
      2062172.83     13425977.42      2062209.30     13425743.01
      2062097.31     13425245.59
#Sta/Elev= 30
  4690.0  345.61  4753.2  344.11  4773.4  341.66  4805.3  341.07  4824.0  342.01
  4863.1  335.88  4868.1  338.63  4874.6  337.55  4905.0  337.64  4965.3  332.92
  4976.4  329.91  5001.6  327.12  5002.3  326.32  5012.1  326.32  5012.8  327.12
  5018.8  329.22  5037.9  331.39  5057.0  332.50  5099.4  331.77  5153.8  332.55
  5181.4  334.11  5191.7  334.98  5197.0  337.39  5240.3  344.72  5273.7  344.43
  5283.6  345.26  5288.7  344.50  5304.5  346.67  5331.9  348.87  5437.1  352.81
#Mann=3,-1,0
  4690.0     0.1       0  5001.6    0.07       0  5012.8     0.1       0
Bank Sta=5001.6,5012.8
Exp/Cntr=0.3,0.1

Type RM Length L Ch R = 1,2029,392,392,392
BEGIN DESCRIPTION:
Mapping XS e8ef66b2
END DESCRIPTION:
XS GIS Cut Line= 3
      2062204.08     13425985.24      2062235.34     13425808.11
      2062560.21     13425210.35
#Sta/Elev= 30
  4475.8  345.68  4570.0  339.57  4587.7  339.62  4624.1  342.10  4687.0  342.75
  4746.9  339.08  4774.4  339.31  4790.6  336.94  4850.5  333.62  4899.8  333.68
  4916.0  332.08  4937.9  332.33  4954.0  330.11  4959.7  331.10  4966.5  330.41
  4975.9  328.47  4981.6  329.59  4992.1  326.51  4992.8  325.71  5003.3  326.51
  5012.0  326.97  5019.6  329.29  5034.8  331.28  5069.0  338.71  5085.1  339.96
  5172.5  344.30  5226.7  345.45  5254.3  348.55  5333.2  351.49  5336.0  351.62
#Mann=4,-1,0
  4475.8     0.1       0  4992.1    0.07       0  5003.3     0.1       0
  5333.2    0.05       0
Bank Sta=4992.1,5003.3
Exp/Cntr=0.3,0.1

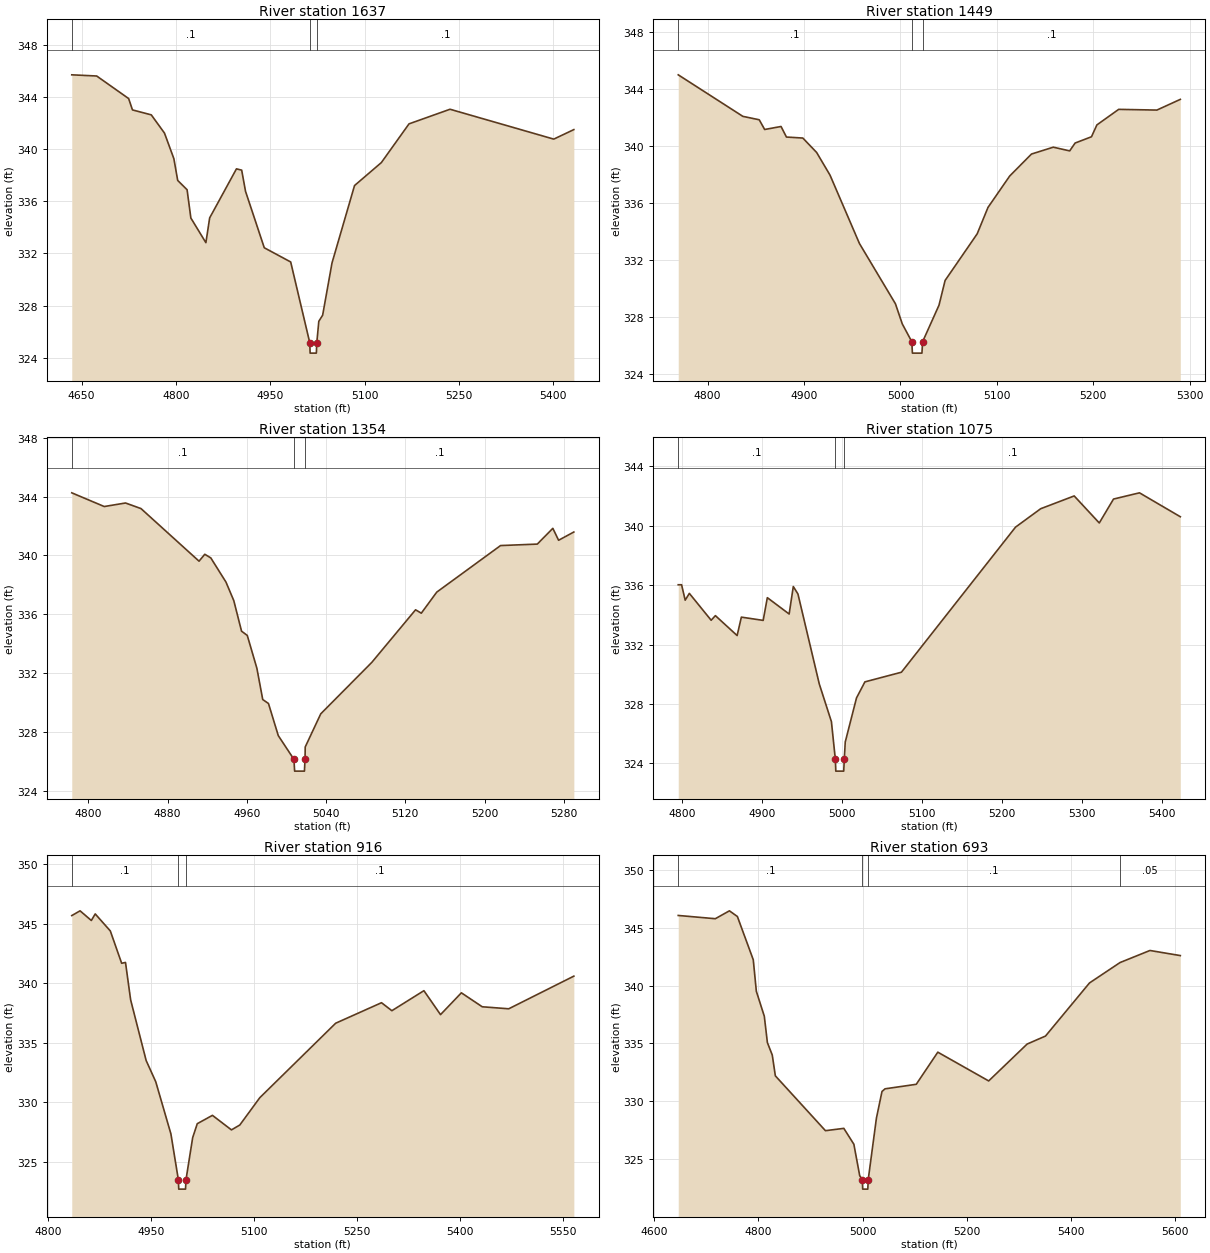
Type RM Length L Ch R = 1,1637,188,188,188
BEGIN DESCRIPTION:
UNT 059 in RCW 2.0
END DESCRIPTION:
XS GIS Cut Line= 3
      2062248.39     13425992.99      2062532.22     13425800.30
      2062907.20     13425542.50
#Sta/Elev= 30
  4634.4  345.69  4674.0  345.60  4724.8  343.87  4730.9  343.00  4760.8  342.62
  4781.8  341.22  4796.7  339.26  4802.8  337.59  4817.7  336.88  4823.7  334.71
  4847.6  332.82  4853.6  334.72  4896.2  338.48  4904.5  338.38  4910.6  336.76
  4940.4  332.43  4982.4  331.34  5012.7  325.15  5013.3  324.35  5023.2  324.35
  5023.9  325.15  5027.1  326.79  5033.2  327.26  5048.1  331.27  5083.9  337.20
  5126.5  338.96  5170.5  341.93  5235.7  343.05  5400.6  340.76  5432.5  341.49
#Mann=3,-1,0
  4634.4     0.1       0  5012.7    0.07       0  5023.9     0.1       0
Bank Sta=5012.7,5023.9
Exp/Cntr=0.3,0.1

Type RM Length L Ch R = 1,1449,95,95,95
BEGIN DESCRIPTION:
Mapping XS c8d34ce2
END DESCRIPTION:
XS GIS Cut Line= 2
      2062435.84     13426037.29      2062904.57     13425810.74
#Sta/Elev= 30
  4769.6  344.97  4836.6  342.06  4853.6  341.82  4859.2  341.14  4876.2  341.35
  4881.8  340.61  4898.8  340.54  4913.1  339.53  4927.0  337.94  4957.5  333.15
  4994.8  328.93  5001.9  327.52  5011.8  326.27  5012.4  325.47  5022.3  325.47
  5023.0  326.27  5040.0  328.83  5046.3  330.56  5079.6  333.83  5090.8  335.68
  5113.3  337.88  5135.9  339.42  5158.5  339.90  5175.5  339.64  5181.1  340.19
  5198.1  340.63  5203.7  341.46  5226.3  342.55  5265.9  342.50  5290.2  343.25
#Mann=3,-1,0
  4769.6     0.1       0  5011.8    0.07       0  5023.0     0.1       0
Bank Sta=5011.8,5023
Exp/Cntr=0.3,0.1

Type RM Length L Ch R = 1,1354,279,279,279
BEGIN DESCRIPTION:
Mapping XS 2bba779d
END DESCRIPTION:
XS GIS Cut Line= 2
      2062514.02     13426117.99      2062950.73     13425860.64
#Sta/Elev= 30
  4783.2  344.25  4816.0  343.32  4837.5  343.56  4853.1  343.18  4911.7  339.61
  4917.5  340.08  4923.6  339.83  4938.9  338.19  4946.8  336.93  4954.6  334.86
  4960.4  334.57  4970.1  332.34  4976.0  330.22  4981.8  329.95  4991.7  327.77
  5007.5  326.16  5008.2  325.36  5018.1  325.36  5018.7  326.16  5018.9  327.00
  5034.6  329.25  5086.1  332.74  5130.3  336.31  5136.1  336.08  5151.7  337.51
  5216.1  340.67  5253.2  340.77  5268.9  341.84  5274.7  341.03  5290.1  341.59
#Mann=3,-1,0
  4783.2     0.1       0  5007.5    0.07       0  5018.7     0.1       0
Bank Sta=5007.5,5018.7
Exp/Cntr=0.3,0.1

Type RM Length L Ch R = 1,1075,159,159,159
BEGIN DESCRIPTION:
Mapping XS ddea1e7f
END DESCRIPTION:
XS GIS Cut Line= 2
      2062847.32     13426368.02      2063034.28     13425768.18
#Sta/Elev= 30
  4794.8  336.03  4799.0  336.03  4803.5  334.99  4808.7  335.45  4836.0  333.64
  4841.3  333.95  4868.5  332.61  4873.8  333.85  4901.1  333.63  4906.3  335.16
  4933.6  334.06  4938.8  335.91  4944.6  335.41  4971.3  329.35  4986.5  326.81
  4991.4  324.28  4992.0  323.48  5001.9  323.48  5002.6  324.28  5003.8  325.44
  5017.9  328.41  5028.4  329.49  5074.1  330.14  5216.9  339.91  5248.4  341.15
  5290.3  342.01  5321.7  340.19  5339.5  341.80  5372.0  342.22  5423.1  340.61
#Mann=3,-1,0
  4794.8     0.1       0  4991.4    0.07       0  5002.6     0.1       0
Bank Sta=4991.4,5002.6
Exp/Cntr=0.3,0.1

Type RM Length L Ch R = 1,916,223,223,223
BEGIN DESCRIPTION:
Mapping XS 03c39ba8
END DESCRIPTION:
XS GIS Cut Line= 3
      2062964.51     13426381.02      2063076.49     13426167.49
      2063154.60     13425683.16
#Sta/Elev= 30
  4834.6  345.68  4846.7  346.08  4863.1  345.27  4868.8  345.82  4890.8  344.39
  4907.3  341.68  4912.9  341.75  4920.4  338.61  4943.0  333.52  4957.0  331.74
  4979.1  327.36  4989.9  323.53  4990.5  322.73  5000.4  322.73  5001.1  323.53
  5010.8  327.05  5017.5  328.22  5039.6  328.92  5067.3  327.70  5079.5  328.11
  5108.6  330.40  5219.2  336.65  5286.0  338.37  5301.1  337.70  5347.8  339.38
  5372.0  337.37  5402.4  339.20  5432.8  338.03  5471.4  337.86  5566.3  340.60
#Mann=3,-1,0
  4834.6     0.1       0  4989.9    0.07       0  5001.1     0.1       0
Bank Sta=4989.9,5001.1
Exp/Cntr=0.3,0.1

Type RM Length L Ch R = 1,693,421,421,421
BEGIN DESCRIPTION:
Mapping XS 165fc6a9
END DESCRIPTION:
XS GIS Cut Line= 3
      2062972.30     13426409.69      2063206.69     13426261.24
      2063454.10     13425620.60
#Sta/Elev= 30
  4645.9  346.04  4717.1  345.76  4744.2  346.44  4759.5  345.95  4790.0  342.22
  4795.9  339.50  4811.2  337.35  4817.1  335.08  4826.5  334.00  4832.4  332.21
  4928.6  327.48  4963.9  327.68  4983.2  326.31  4994.4  323.60  4999.5  323.24
  5000.1  322.44  5010.0  322.44  5010.7  323.24  5026.5  328.56  5037.2  330.86
  5043.1  331.09  5103.0  331.48  5144.4  334.25  5242.1  331.77  5315.9  334.95
  5351.2  335.64  5435.7  340.22  5494.4  341.98  5551.8  343.02  5610.1  342.58
#Mann=4,-1,0
  4645.9     0.1       0  4999.5    0.07       0  5010.7     0.1       0
  5494.4    0.05       0
Bank Sta=4999.5,5010.7
Exp/Cntr=0.3,0.1

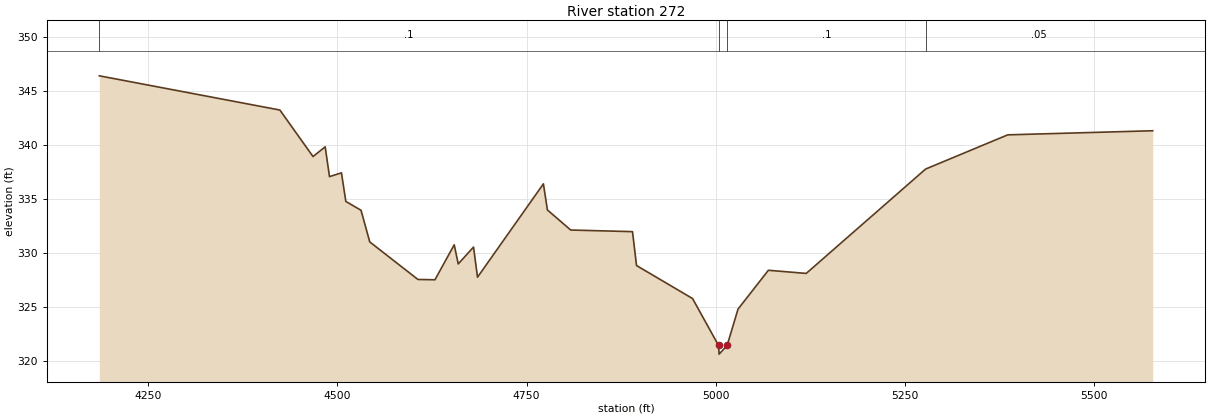
Type RM Length L Ch R = 1,272,0,0,0
BEGIN DESCRIPTION:
UNT 059 in RCW 1.0
END DESCRIPTION:
XS GIS Cut Line= 5
      2062908.49     13426493.02      2063189.77     13426340.23
      2063571.28     13426203.95      2063589.07     13425916.62
      2063530.05     13425541.63
#Sta/Elev= 30
  4185.2  346.42  4423.9  343.25  4467.7  338.94  4483.8  339.84  4489.5  337.08
  4505.3  337.43  4511.1  334.78  4531.2  333.96  4542.7  331.03  4606.4  327.55
  4628.9  327.52  4654.4  330.76  4659.7  328.99  4679.9  330.55  4685.2  327.76
  4772.3  336.41  4777.6  333.99  4808.4  332.13  4890.1  331.98  4895.4  328.84
  4969.5  325.78  5003.9  321.43  5004.6  320.63  5015.2  321.43  5029.6  324.80
  5069.7  328.40  5119.8  328.11  5277.6  337.78  5386.2  340.95  5577.9  341.33
#Mann=4,-1,0
  4185.2     0.1       0  5003.9    0.07       0  5015.2     0.1       0
  5277.6    0.05       0
Bank Sta=5003.9,5015.2
Exp/Cntr=0.3,0.1

Chan Stop Cuts=-1