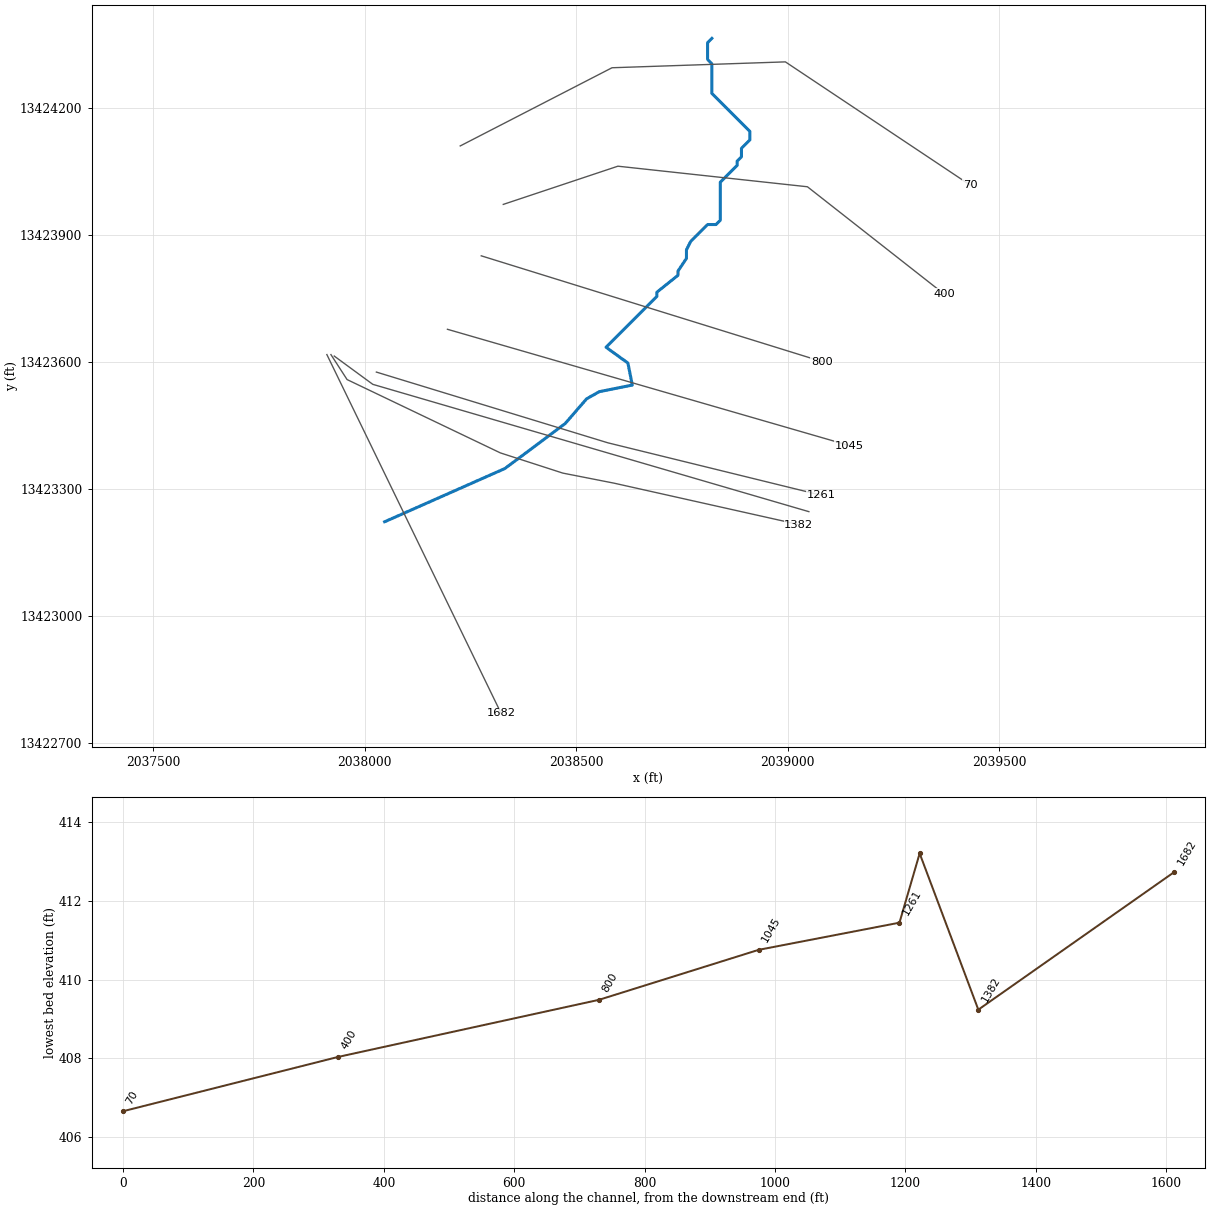
--- UNT 060 in RCW.prj (project) ---

Proj Title=UNT 060 in RCW Base Level Engineering
Current Plan=p01
Default Exp/Contr=0.3,0.1
English Units
Geom File=g01
Flow File=f01
Plan File=p01
BEGIN DESCRIPTION:
UNT 060 in RCW
END DESCRIPTION:

--- UNT 060 in RCW.p01 (plan) ---

Plan Title=Multiple Run
Short Identifier=Multiple
Geom File=g01
Flow File=f01
Subcritical Flow
K Sum by GR= 0
Std Step Tol= 0.01
Critical Tol= 0.01
Num of Std Step Trials= 20
Max Error Tol= 0.3
Flow Tol Ratio= 0.001
Split Flow NTrial= 30
Split Flow Tol= 0.02
Split Flow Ratio= 0.02
Log Output Level= 0
Friction Slope Method= 1
Unsteady Friction Slope Method= 2
Unsteady Bridges Friction Slope Method= 1
Parabolic Critical Depth
Global Vel Dist=  1 , 1 , 1
Global Log Level= 0
CheckData=True
Encroach Param= -1, 0, 0, 0
BEGIN DESCRIPTION:
Multiple Run
END DESCRIPTION:

--- UNT 060 in RCW.f01 (steady flow) ---

Flow Title=Multiple
Number of Profiles=7
Profile Names=10-year,25-year,50-year,1pct_min,100-year,1pct_plu,500-year
River Rch & RM= UNT 060 in RCW,Reach-1,1682
     153     206     249     150     299     597     439
River Rch & RM= UNT 060 in RCW,Reach-1,70
     346     488     606     375     749    1495    1162
Boundary for River Rch & Prof#=UNT 060 in RCW,Reach-1,1
Up Type=0
Dn Type=3
Dn Slope=0.005
Boundary for River Rch & Prof#=UNT 060 in RCW,Reach-1,2
Up Type=0
Dn Type=3
Dn Slope=0.005
Boundary for River Rch & Prof#=UNT 060 in RCW,Reach-1,3
Up Type=0
Dn Type=3
Dn Slope=0.005
Boundary for River Rch & Prof#=UNT 060 in RCW,Reach-1,4
Up Type=0
Dn Type=3
Dn Slope=0.005
Boundary for River Rch & Prof#=UNT 060 in RCW,Reach-1,5
Up Type=0
Dn Type=3
Dn Slope=0.005
Boundary for River Rch & Prof#=UNT 060 in RCW,Reach-1,6
Up Type=0
Dn Type=3
Dn Slope=0.005
Boundary for River Rch & Prof#=UNT 060 in RCW,Reach-1,7
Up Type=0
Dn Type=3
Dn Slope=0.005

--- UNT 060 in RCW.g01 (geometry) ---

Geom Title=Existing Conditions

River Reach=UNT 060 in RCW,Reach-1
Reach XY= 30
      2038047.59     13423222.10      2038331.88     13423347.97
      2038474.01     13423453.98      2038524.79     13423512.57
      2038554.74     13423529.50      2038632.86     13423545.12
      2038622.45     13423597.20      2038570.80     13423634.53
      2038690.80     13423754.54      2038690.80     13423764.54
      2038740.80     13423804.54      2038740.80     13423814.54
      2038760.80     13423844.54      2038760.80     13423864.54
      2038770.80     13423884.54      2038810.80     13423924.54
      2038830.80     13423924.54      2038840.80     13423934.54
      2038840.80     13424024.54      2038880.80     13424064.54
      2038880.80     13424074.54      2038890.80     13424084.54
      2038890.80     13424104.54      2038910.80     13424124.54
      2038910.80     13424144.54      2038820.80     13424234.54
      2038820.80     13424304.54      2038810.80     13424314.54
      2038810.80     13424354.54      2038820.80     13424364.54

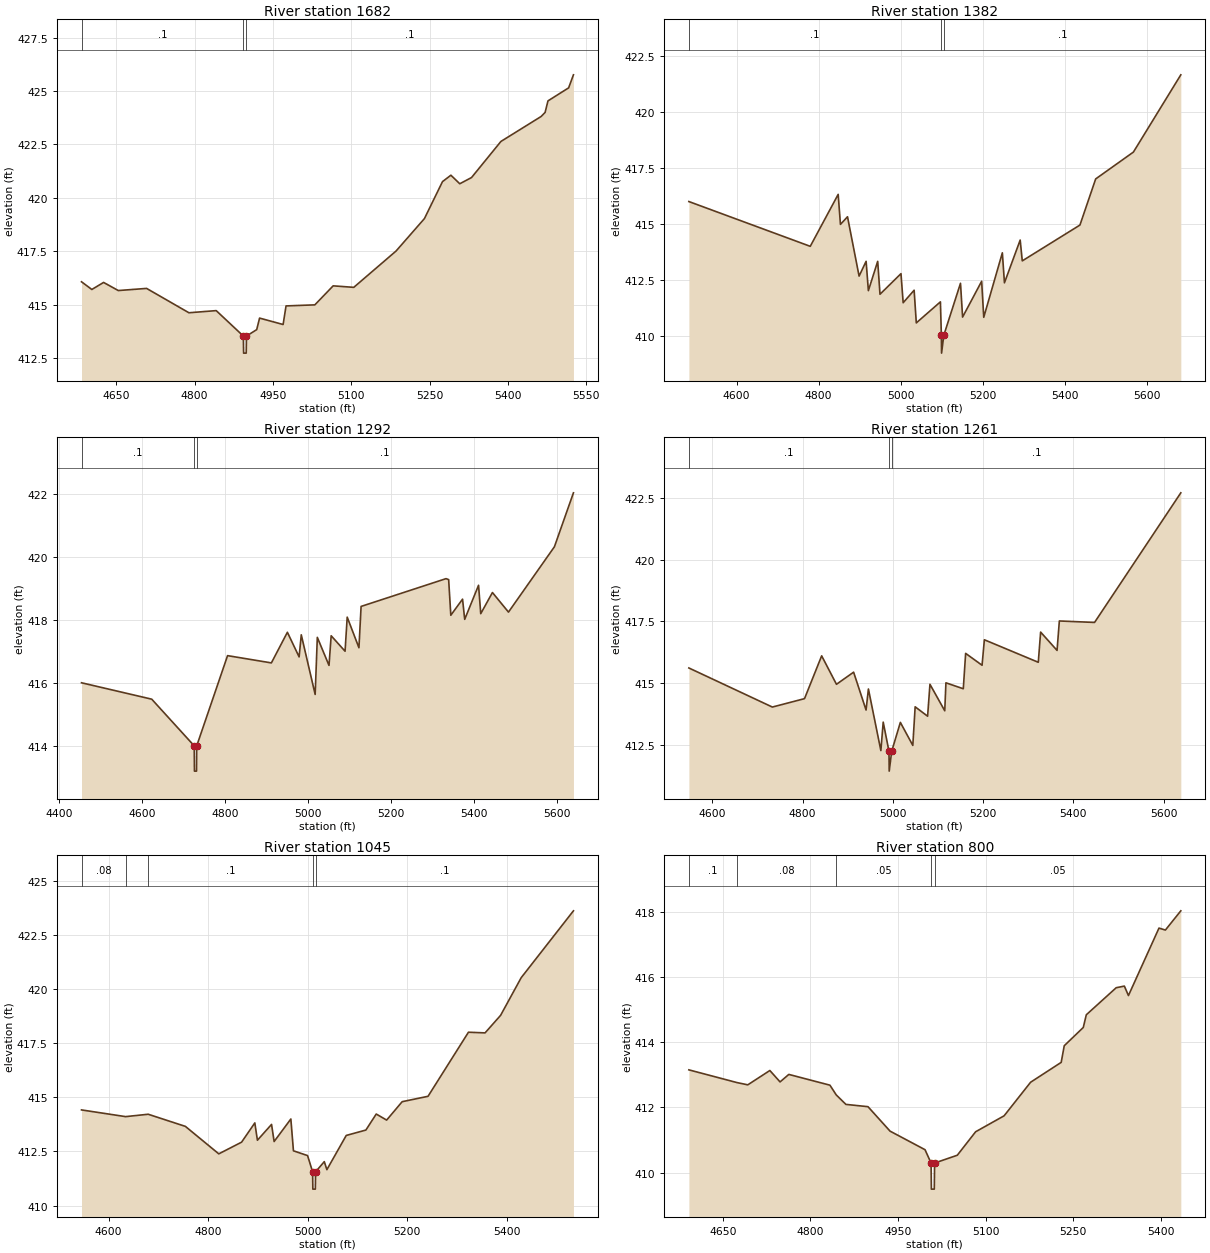
Type RM Length L Ch R = 1,1682,300,300,300
BEGIN DESCRIPTION:
UNT 060 in RCW 6.0
END DESCRIPTION:
XS GIS Cut Line= 2
      2037911.07     13423617.20      2038322.83     13422769.29
#Sta/Elev= 30
  4583.2  416.07  4603.0  415.71  4625.5  416.04  4653.7  415.66  4707.9  415.76
  4789.0  414.62  4841.3  414.72  4893.3  413.53  4893.8  412.73  4898.8  412.73
  4899.3  413.53  4918.9  413.83  4924.4  414.37  4969.5  414.07  4975.1  414.94
  5030.3  414.99  5065.4  415.88  5104.9  415.81  5185.9  417.51  5240.3  419.03
  5274.9  420.76  5291.0  421.06  5308.0  420.66  5330.5  420.95  5386.8  422.64
  5463.9  423.81  5471.5  424.00  5477.0  424.54  5516.6  425.15  5525.8  425.76
#Mann=3,-1,0
  4583.2     0.1       0  4893.3    0.07       0  4899.3     0.1       0
Bank Sta=4893.3,4899.3
Exp/Cntr=0.3,0.1

Type RM Length L Ch R = 1,1382,90,90,90
BEGIN DESCRIPTION:
UNT 060 in RCW 8.0
END DESCRIPTION:
XS GIS Cut Line= 6
      2037920.65     13423617.14      2037958.82     13423558.14
      2038321.02     13423384.86      2038468.59     13423337.12
      2038590.12     13423313.24      2039026.29     13423215.60
#Sta/Elev= 30
  4484.0  416.01  4779.5  414.01  4847.5  416.33  4853.0  414.99  4870.2  415.33
  4898.4  412.68  4915.5  413.34  4921.0  412.03  4943.7  413.34  4949.3  411.87
  5000.4  412.79  5005.7  411.49  5032.4  412.05  5037.7  410.59  5096.4  411.53
  5098.7  410.04  5099.2  409.24  5104.7  410.04  5145.3  412.36  5150.4  410.85
  5196.8  412.45  5201.9  410.84  5247.2  413.72  5252.3  412.38  5290.6  414.29
  5295.7  413.36  5436.1  414.96  5474.4  417.02  5566.3  418.22  5681.7  421.67
#Mann=3,-1,0
  4484.0     0.1       0  5098.7    0.07       0  5104.7     0.1       0
Bank Sta=5098.7,5104.7
Exp/Cntr=0.3,0.1

Type RM Length L Ch R = 1,1292,31,31,31
BEGIN DESCRIPTION:
UNT 060 in RCW 7.0
END DESCRIPTION:
XS GIS Cut Line= 3
      2037928.43     13423613.71      2038019.58     13423546.86
      2039050.12     13423245.99
#Sta/Elev= 30
  4453.5  416.01  4622.9  415.49  4725.4  414.01  4725.9  413.21  4730.9  413.21
  4731.4  414.01  4805.8  416.87  4911.5  416.64  4950.1  417.61  4978.4  416.83
  4983.6  417.53  5017.1  415.64  5022.3  417.45  5050.5  416.56  5055.7  417.50
  5089.2  417.01  5094.4  418.09  5122.7  417.12  5127.9  418.43  5332.7  419.31
  5339.1  419.28  5344.3  418.15  5372.6  418.66  5377.8  418.02  5411.2  419.10
  5416.5  418.20  5444.7  418.87  5483.4  418.25  5594.2  420.32  5640.1  422.03
#Mann=3,-1,0
  4453.5     0.1       0  4725.4    0.07       0  4731.4     0.1       0
Bank Sta=4725.4,4731.4
Exp/Cntr=0.3,0.1

Type RM Length L Ch R = 1,1261,216,216,216
BEGIN DESCRIPTION:
UNT 060 in RCW 4.0
END DESCRIPTION:
XS GIS Cut Line= 3
      2038028.04     13423575.84      2038574.93     13423408.73
      2039078.40     13423285.03
#Sta/Elev= 30
  4548.0  415.62  4733.0  414.04  4804.3  414.38  4842.3  416.11  4875.1  414.96
  4913.1  415.45  4940.7  413.92  4945.9  414.77  4973.5  412.28  4978.7  413.43
  4991.5  412.25  4992.0  411.45  4997.5  412.25  5016.7  413.42  5044.3  412.49
  5049.5  414.05  5077.1  413.67  5082.3  414.96  5115.1  413.89  5117.7  415.02
  5156.2  414.78  5161.4  416.21  5197.8  415.73  5202.9  416.76  5322.4  415.85
  5327.6  417.07  5364.0  416.33  5369.1  417.52  5447.1  417.46  5638.3  422.70
#Mann=3,-1,0
  4548.0     0.1       0  4991.5    0.07       0  4997.5     0.1       0
Bank Sta=4991.5,4997.5
Exp/Cntr=0.3,0.1

Type RM Length L Ch R = 1,1045,245,245,245
BEGIN DESCRIPTION:
UNT 060 in RCW 5.0
END DESCRIPTION:
XS GIS Cut Line= 2
      2038195.99     13423676.97      2039145.65     13423402.23
#Sta/Elev= 30
  4545.7  414.42  4634.3  414.11  4679.7  414.22  4754.4  413.66  4821.6  412.39
  4867.4  412.93  4894.0  413.82  4899.2  413.02  4927.6  413.75  4932.8  412.96
  4966.4  414.00  4971.6  412.53  5000.0  412.31  5010.1  411.56  5010.6  410.76
  5015.6  410.76  5016.1  411.56  5033.6  412.03  5038.8  411.66  5077.7  413.24
  5117.2  413.49  5138.0  414.23  5158.9  413.95  5190.1  414.80  5242.1  415.05
  5323.3  418.01  5356.7  417.98  5387.9  418.79  5429.3  420.53  5534.3  423.62
#Mann=5,-1,0
  4545.7    0.08       0  4634.3    0.05       0  4679.7     0.1       0
  5010.1    0.07       0  5016.1     0.1       0
Bank Sta=5010.1,5016.1
Exp/Cntr=0.3,0.1

Type RM Length L Ch R = 1,800,400,400,400
BEGIN DESCRIPTION:
UNT 060 in RCW 3.0
END DESCRIPTION:
XS GIS Cut Line= 2
      2038275.87     13423850.58      2039080.70     13423600.80
#Sta/Elev= 30
  4591.7  413.15  4674.0  412.76  4692.6  412.69  4730.4  413.13  4747.9  412.78
  4762.9  413.01  4833.3  412.68  4844.2  412.38  4860.7  412.09  4898.5  412.02
  4936.3  411.27  4996.2  410.70  5006.6  410.29  5007.1  409.49  5012.1  409.49
  5012.6  410.29  5051.5  410.53  5082.9  411.25  5131.7  411.74  5177.1  412.77
  5229.5  413.38  5234.7  413.89  5267.3  414.45  5272.5  414.84  5323.7  415.67
  5337.7  415.72  5344.7  415.43  5397.0  417.50  5408.0  417.44  5434.4  418.03
#Mann=5,-1,0
  4591.7     0.1       0  4674.0    0.08       0  4844.2    0.05       0
  5006.6    0.03       0  5012.6    0.05       0
Bank Sta=5006.6,5012.6
Exp/Cntr=0.3,0.1

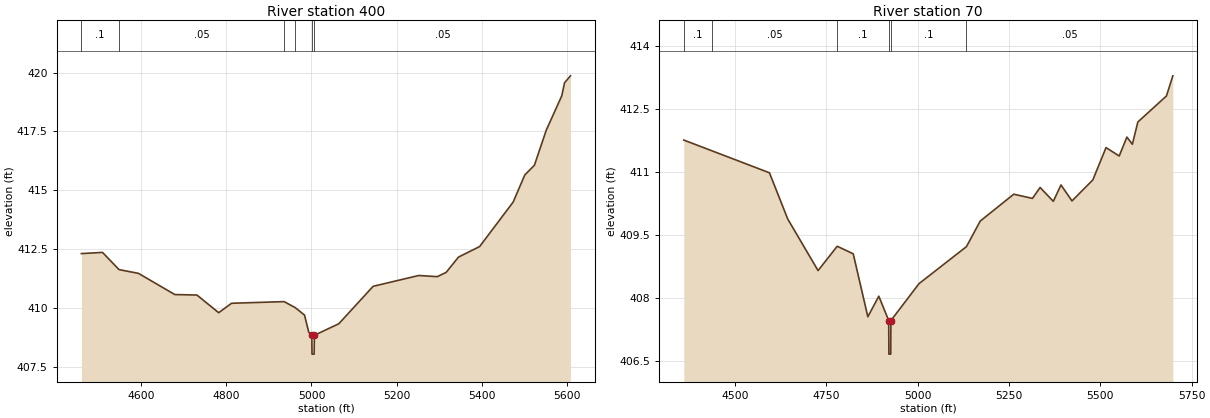
Type RM Length L Ch R = 1,400,330,330,330
BEGIN DESCRIPTION:
UNT 060 in RCW 2.0
END DESCRIPTION:
XS GIS Cut Line= 4
      2038327.97     13423972.10      2038598.80     13424062.38
      2039046.72     13424013.77      2039369.60     13423760.32
#Sta/Elev= 30
  4460.6  412.31  4510.2  412.36  4548.9  411.63  4594.5  411.47  4679.7  410.57
  4731.5  410.55  4782.5  409.80  4812.7  410.20  4935.9  410.27  4961.5  410.02
  4983.7  409.70  4993.7  408.97  5000.8  408.84  5001.3  408.04  5006.3  408.04
  5006.8  408.84  5064.1  409.33  5144.6  410.92  5251.5  411.38  5294.8  411.33
  5315.7  411.51  5344.6  412.16  5394.3  412.61  5472.9  414.50  5500.1  415.65
  5522.6  416.06  5550.4  417.55  5586.8  419.01  5593.2  419.56  5607.1  419.86
#Mann=6,-1,0
  4460.6     0.1       0  4548.9    0.05       0  4935.9     0.1       0
  4961.5    0.05       0  5000.8    0.03       0  5006.8    0.05       0
Bank Sta=5000.8,5006.8
Exp/Cntr=0.3,0.1

Type RM Length L Ch R = 1,70,0,0,0
BEGIN DESCRIPTION:
UNT 060 in RCW 1.0
END DESCRIPTION:
XS GIS Cut Line= 4
      2038226.22     13424110.25      2038584.91     13424295.02
      2038994.64     13424308.90      2039431.10     13424017.93
#Sta/Elev= 30
  4360.5  411.76  4438.7  411.50  4594.9  410.98  4644.9  409.88  4727.9  408.65
  4780.3  409.23  4824.1  409.05  4864.1  407.55  4894.1  408.04  4921.2  407.46
  4921.7  406.66  4926.7  406.66  4927.2  407.46  5004.2  408.34  5133.8  409.22
  5171.6  409.83  5263.3  410.47  5314.4  410.37  5335.4  410.63  5371.5  410.30
  5392.5  410.69  5422.6  410.31  5479.6  410.81  5515.7  411.58  5551.8  411.38
  5572.8  411.83  5587.8  411.66  5602.8  412.19  5681.0  412.81  5698.5  413.29
#Mann=6,-1,0
  4360.5     0.1       0  4438.7    0.05       0  4780.3     0.1       0
  4921.2    0.07       0  4927.2     0.1       0  5133.8    0.05       0
Bank Sta=4921.2,4927.2
Exp/Cntr=0.3,0.1

Chan Stop Cuts=-1