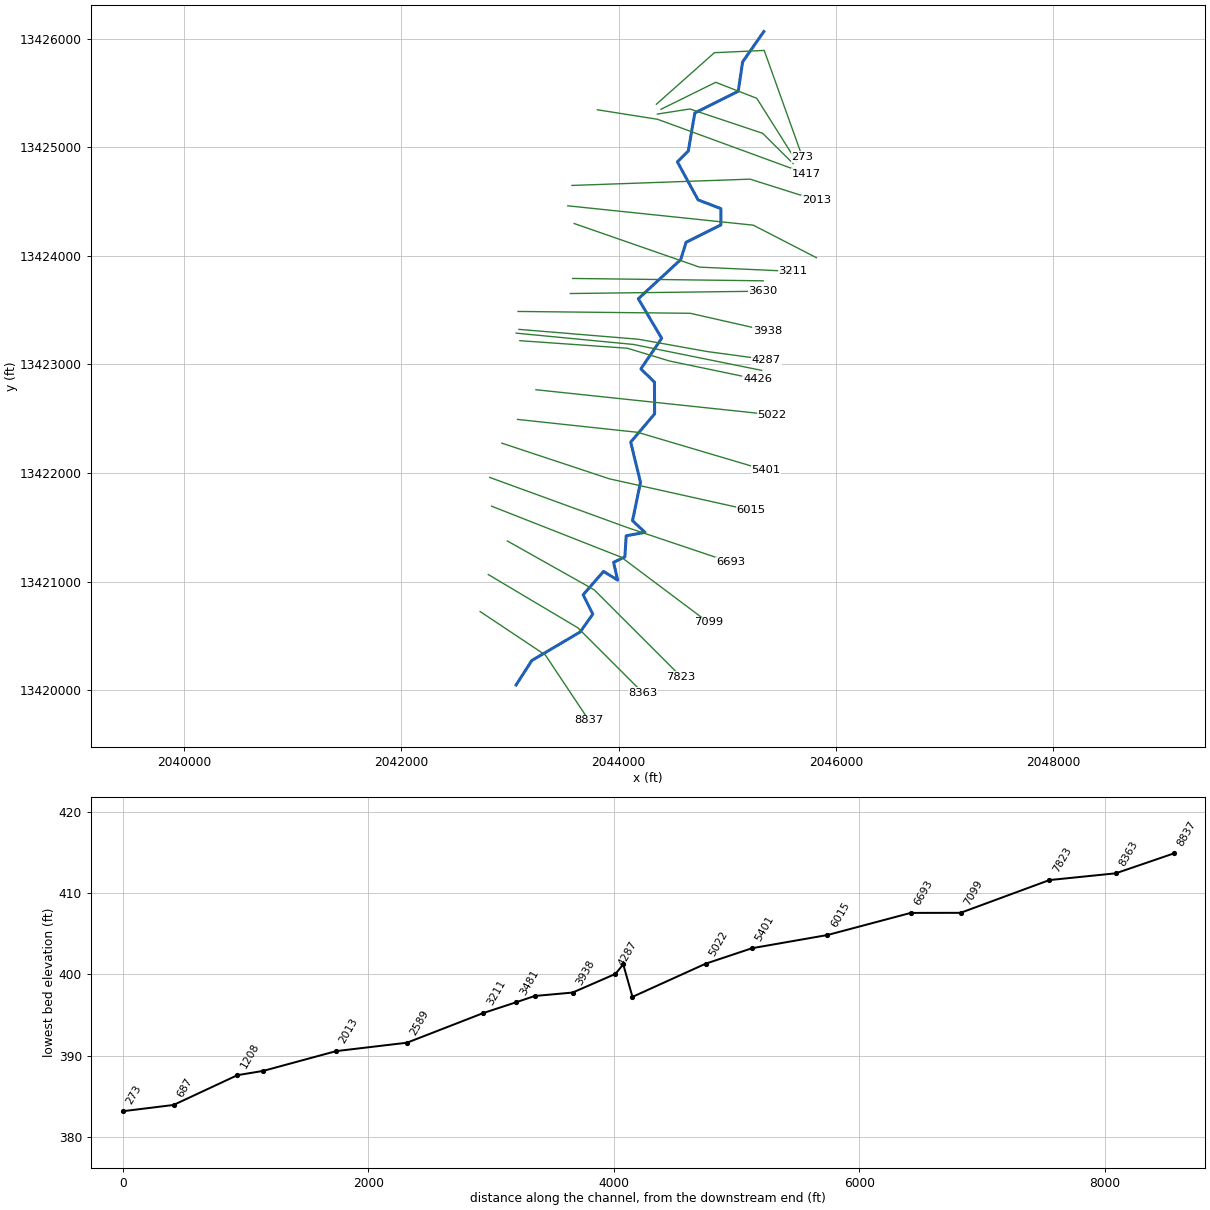
--- UNT 061 in RCW.prj (project) ---

Proj Title=UNT 061 in RCW Base Level Engineering
Current Plan=p01
Default Exp/Contr=0.3,0.1
English Units
Geom File=g01
Flow File=f01
Plan File=p01
BEGIN DESCRIPTION:
UNT 061 in RCW
END DESCRIPTION:

--- UNT 061 in RCW.p01 (plan) ---

Plan Title=Multiple Run
Short Identifier=Multiple
Geom File=g01
Flow File=f01
Subcritical Flow
K Sum by GR= 0
Std Step Tol= 0.01
Critical Tol= 0.01
Num of Std Step Trials= 20
Max Error Tol= 0.3
Flow Tol Ratio= 0.001
Split Flow NTrial= 30
Split Flow Tol= 0.02
Split Flow Ratio= 0.02
Log Output Level= 0
Friction Slope Method= 1
Unsteady Friction Slope Method= 2
Unsteady Bridges Friction Slope Method= 1
Parabolic Critical Depth
Global Vel Dist=  1 , 1 , 1
Global Log Level= 0
CheckData=True
Encroach Param= -1, 0, 0, 0
BEGIN DESCRIPTION:
Multiple Run
END DESCRIPTION:

--- UNT 061 in RCW.f01 (steady flow) ---

Flow Title=Multiple
Number of Profiles=7
Profile Names=10-year,25-year,50-year,1pct_min,100-year,1pct_plu,500-year
River Rch & RM= UNT 061 in RCW,Reach-1,8837
     183     250     306     186     372     742     560
River Rch & RM= UNT 061 in RCW,Reach-1,7823
     226     313     384     235     469     935     710
Boundary for River Rch & Prof#=UNT 061 in RCW,Reach-1,1
Up Type=0
Dn Type=3
Dn Slope=0.005
Boundary for River Rch & Prof#=UNT 061 in RCW,Reach-1,2
Up Type=0
Dn Type=3
Dn Slope=0.005
Boundary for River Rch & Prof#=UNT 061 in RCW,Reach-1,3
Up Type=0
Dn Type=3
Dn Slope=0.005
Boundary for River Rch & Prof#=UNT 061 in RCW,Reach-1,4
Up Type=0
Dn Type=3
Dn Slope=0.005
Boundary for River Rch & Prof#=UNT 061 in RCW,Reach-1,5
Up Type=0
Dn Type=3
Dn Slope=0.005
Boundary for River Rch & Prof#=UNT 061 in RCW,Reach-1,6
Up Type=0
Dn Type=3
Dn Slope=0.005
Boundary for River Rch & Prof#=UNT 061 in RCW,Reach-1,7
Up Type=0
Dn Type=3
Dn Slope=0.005

--- UNT 061 in RCW.g01 (geometry) ---

Geom Title=Existing Conditions

River Reach=UNT 061 in RCW,Reach-1
Reach XY= 30
      2043055.80     13420049.54      2043200.80     13420274.54
      2043645.86     13420537.26      2043761.75     13420701.32
      2043673.21     13420879.71      2043860.80     13421094.54
      2043990.80     13421014.54      2043953.16     13421177.88
      2044057.32     13421228.66      2044069.04     13421422.67
      2044242.22     13421453.92      2044127.63     13421562.00
      2044200.80     13421914.54      2044110.80     13422284.54
      2044330.80     13422544.54      2044329.46     13422836.74
      2044204.46     13422959.13      2044395.86     13423240.38
      2044180.80     13423604.54      2044570.80     13423964.54
      2044620.80     13424124.54      2044940.80     13424284.54
      2044940.80     13424434.54      2044730.80     13424514.54
      2044540.80     13424864.54      2044640.80     13424964.54
      2044700.80     13425314.54      2045100.80     13425514.54
      2045140.80     13425784.54      2045336.32     13426064.54

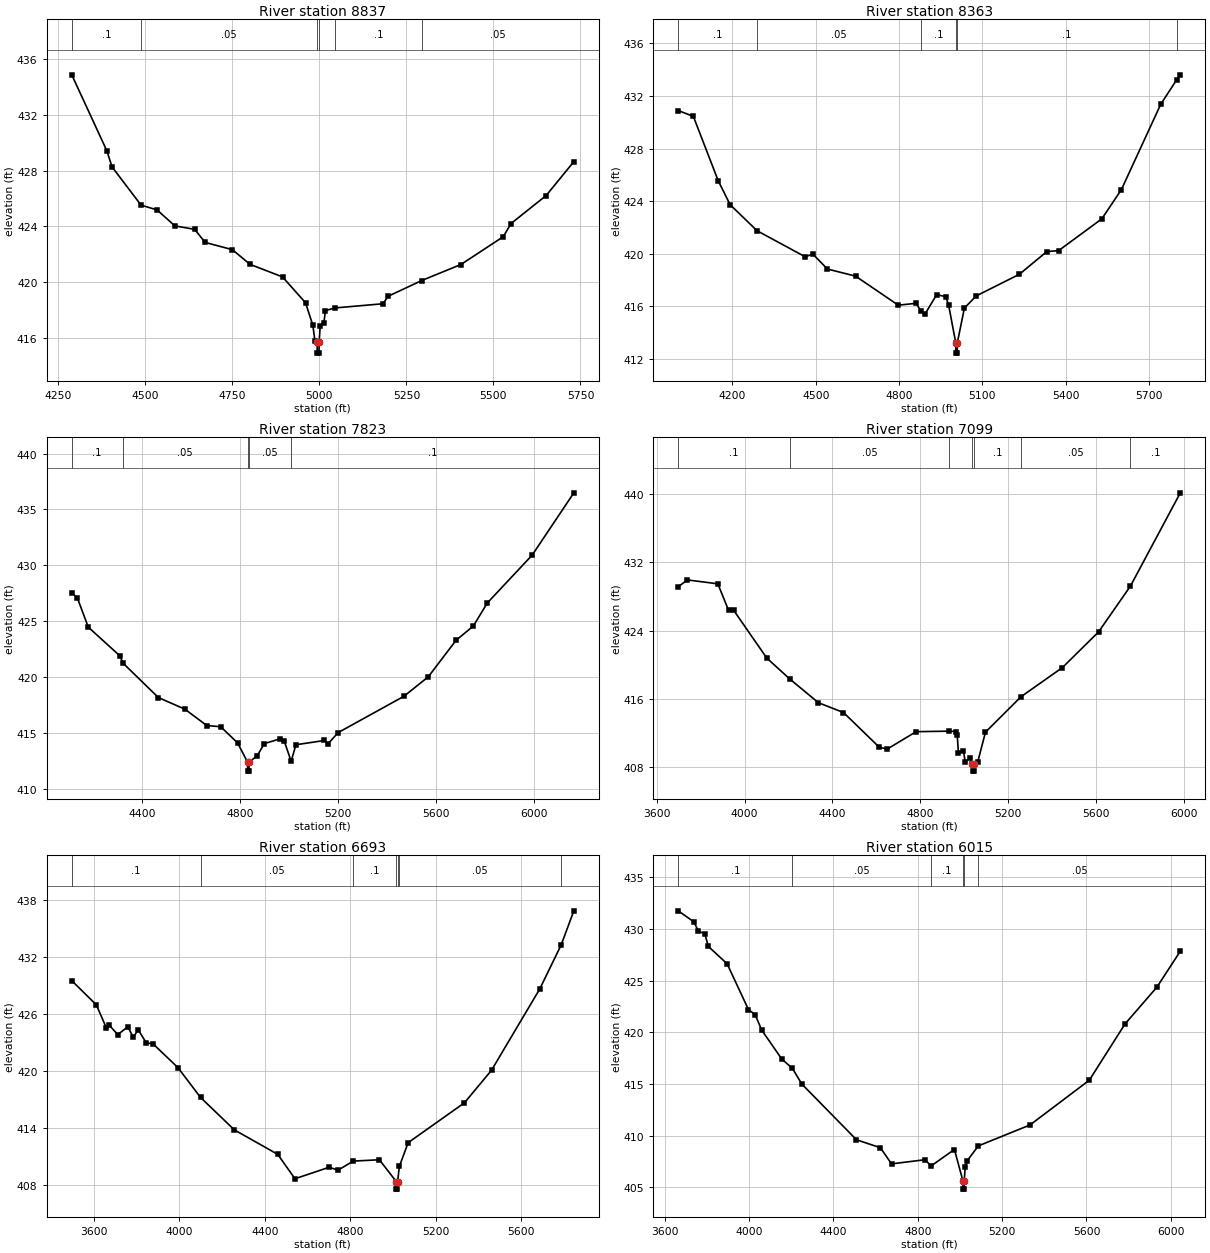
Type RM Length L Ch R = 1,8837,474,474,474
BEGIN DESCRIPTION:
UNT 061 in RCW 12.0
END DESCRIPTION:
XS GIS Cut Line= 3
      2042725.00     13420725.00      2043325.00     13420325.00
      2043724.99     13419725.01
#Sta/Elev= 30
  4288.8  434.89  4389.5  429.43  4404.5  428.27  4487.8  425.52  4533.7  425.18
  4584.8  424.03  4641.8  423.78  4671.9  422.84  4750.0  422.32  4801.1  421.26
  4894.2  420.36  4960.3  418.50  4981.4  416.87  4987.4  415.73  4993.4  415.68
  4993.9  414.88  4998.9  414.88  4999.4  415.68  5002.4  416.83  5012.9  417.04
  5017.4  417.94  5045.3  418.13  5182.7  418.43  5197.7  418.97  5294.0  420.10
  5406.5  421.25  5528.2  423.25  5550.7  424.20  5651.4  426.21  5731.0  428.65
#Mann=6,-1,0
  4288.8     0.1       0  4487.8    0.05       0  4993.4    0.03       0
  4999.4    0.05       0  5045.3     0.1       0  5294.0    0.05       0
Bank Sta=4993.4,4999.4
Exp/Cntr=0.3,0.1

Type RM Length L Ch R = 1,8363,540,540,540
BEGIN DESCRIPTION:
UNT 061 in RCW 11.0
END DESCRIPTION:
XS GIS Cut Line= 3
      2042799.80     13421065.73      2043625.00     13420575.00
      2044224.99     13419975.01
#Sta/Elev= 30
  4004.6  430.89  4059.0  430.45  4148.6  425.55  4191.4  423.73  4288.8  421.74
  4462.2  419.76  4489.4  419.97  4542.0  418.83  4643.3  418.29  4797.2  416.08
  4861.4  416.22  4879.3  415.62  4892.6  415.37  4935.5  416.88  4968.2  416.73
  4978.8  416.07  5004.1  413.23  5004.6  412.43  5009.6  412.43  5010.1  413.23
  5035.4  415.86  5077.8  416.78  5233.4  418.43  5332.4  420.16  5374.8  420.23
  5530.4  422.65  5601.1  424.88  5742.5  431.36  5800.0  433.23  5813.2  433.61
#Mann=6,-1,0
  4004.6     0.1       0  4288.8    0.05       0  4879.3     0.1       0
  5004.1    0.07       0  5010.1     0.1       0  5800.0    0.05       0
Bank Sta=5004.1,5010.1
Exp/Cntr=0.3,0.1

Type RM Length L Ch R = 1,7823,724,724,724
BEGIN DESCRIPTION:
UNT 061 in RCW 10.0
END DESCRIPTION:
XS GIS Cut Line= 3
      2042974.97     13421375.02      2043775.00     13420925.00
      2044575.01     13420124.99
#Sta/Elev= 30
  4114.2  427.56  4137.2  427.08  4181.5  424.48  4311.5  421.89  4321.9  421.29
  4467.7  418.18  4576.0  417.14  4665.0  415.68  4722.3  415.57  4791.2  414.12
  4831.8  412.40  4832.3  411.60  4837.4  411.60  4837.9  412.40  4871.5  412.98
  4899.9  414.06  4964.9  414.49  4980.8  414.33  5009.6  412.48  5029.2  413.96
  5145.3  414.34  5159.4  414.03  5201.8  415.05  5470.5  418.30  5569.5  420.04
  5682.7  423.30  5753.4  424.58  5809.9  426.63  5993.8  430.93  6163.5  436.49
#Mann=5,-1,0
  4114.2     0.1       0  4321.9    0.05       0  4831.8    0.03       0
  4837.9    0.05       0  5009.6     0.1       0
Bank Sta=4831.8,4837.9
Exp/Cntr=0.3,0.1

Type RM Length L Ch R = 1,7099,406,406,406
BEGIN DESCRIPTION:
UNT 061 in RCW 9.0
END DESCRIPTION:
XS GIS Cut Line= 3
      2042830.21     13421695.07      2044025.00     13421225.00
      2044824.97     13420625.02
#Sta/Elev= 30
  3698.3  429.12  3740.3  429.91  3878.4  429.46  3927.2  426.37  3950.6  426.36
  4101.1  420.78  4205.9  418.33  4336.2  415.56  4450.0  414.42  4612.5  410.37
  4649.1  410.15  4780.4  412.18  4931.5  412.24  4960.7  412.20  4967.3  411.81
  4972.7  409.74  4995.8  409.90  5004.1  408.61  5024.9  409.11  5036.5  408.37
  5037.0  407.57  5042.1  407.57  5042.6  408.37  5060.4  408.61  5095.8  412.12
  5257.9  416.27  5445.8  419.67  5610.4  423.84  5755.3  429.19  5982.2  440.09
#Mann=7,-1,0
  3698.3     0.1       0  4205.9    0.05       0  4931.5     0.1       0
  5036.5    0.07       0  5042.6     0.1       0  5257.9    0.05       0
  5755.3     0.1       0
Bank Sta=5036.5,5042.6
Exp/Cntr=0.3,0.1

Type RM Length L Ch R = 1,6693,678,678,678
BEGIN DESCRIPTION:
Mapping XS 9ab43a3c
END DESCRIPTION:
XS GIS Cut Line= 3
      2042812.82     13421959.84      2044075.83     13421499.77
      2045030.38     13421178.69
#Sta/Elev= 30
  3496.2  429.50  3611.4  426.95  3658.2  424.52  3672.6  424.80  3711.4  423.82
  3759.0  424.65  3784.2  423.53  3807.2  424.34  3845.4  422.94  3875.9  422.87
  3992.9  420.36  4099.2  417.21  4257.4  413.80  4460.8  411.22  4541.5  408.65
  4701.2  409.86  4743.7  409.56  4814.3  410.51  4936.8  410.65  5015.8  408.36
  5016.3  407.56  5021.5  407.56  5022.0  408.36  5030.6  409.97  5071.6  412.45
  5335.4  416.65  5461.9  420.07  5687.7  428.62  5787.7  433.24  5847.5  436.85
#Mann=7,-1,0
  3496.2     0.1       0  4099.2    0.05       0  4814.3     0.1       0
  5015.8    0.07       0  5022.0     0.1       0  5030.6    0.05       0
  5787.7     0.1       0
Bank Sta=5015.8,5022
Exp/Cntr=0.3,0.1

Type RM Length L Ch R = 1,6015,614,614,614
BEGIN DESCRIPTION:
UNT 061 in RCW 8.0
END DESCRIPTION:
XS GIS Cut Line= 3
      2042924.96     13422275.01      2043915.24     13421946.82
      2045220.83     13421656.20
#Sta/Elev= 30
  3664.2  431.74  3738.0  430.68  3759.1  429.81  3790.7  429.49  3806.9  428.30
  3896.0  426.62  3997.1  422.20  4028.8  421.70  4060.4  420.20  4155.5  417.41
  4205.5  416.51  4250.6  414.99  4509.5  409.61  4622.9  408.84  4675.6  407.28
  4833.1  407.68  4863.8  407.09  4973.8  408.67  5014.2  405.64  5014.7  404.84
  5019.9  404.84  5020.4  405.64  5024.8  406.94  5035.0  407.60  5087.3  409.02
  5332.1  411.04  5613.6  415.37  5782.9  420.81  5933.5  424.35  6045.0  427.84
#Mann=6,-1,0
  3664.2     0.1       0  4205.5    0.05       0  4863.8     0.1       0
  5014.2    0.07       0  5020.4     0.1       0  5087.3    0.05       0
Bank Sta=5014.2,5020.4
Exp/Cntr=0.3,0.1

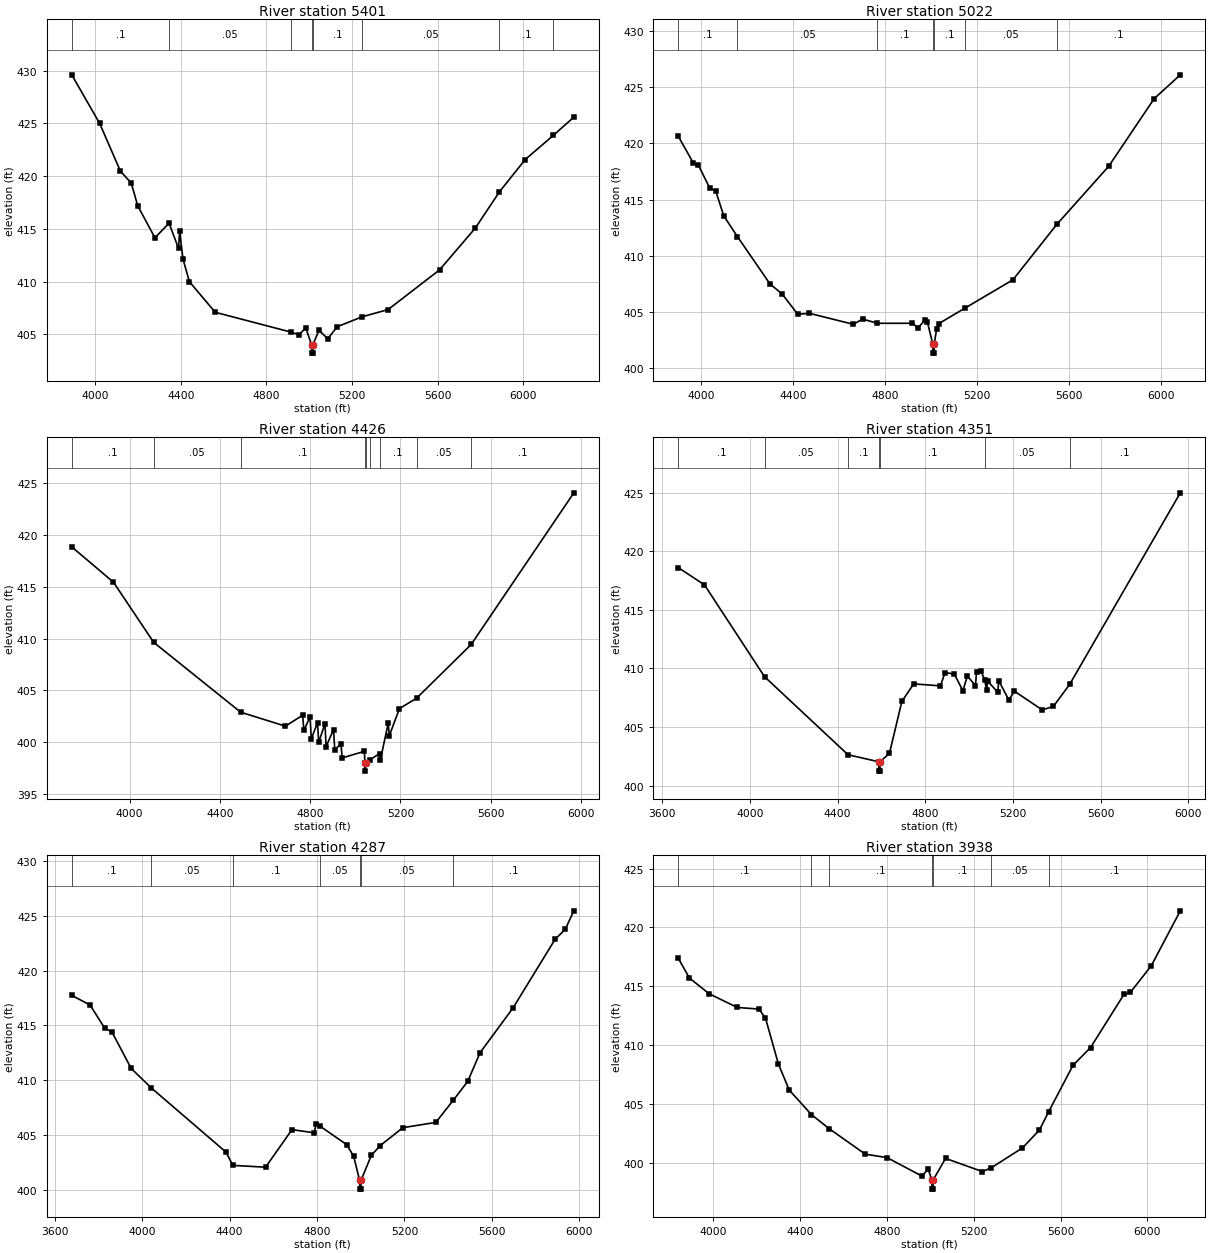
Type RM Length L Ch R = 1,5401,379,379,379
BEGIN DESCRIPTION:
UNT 061 in RCW 7.0
END DESCRIPTION:
XS GIS Cut Line= 3
      2043068.85     13422493.70      2044175.00     13422375.00
      2045356.22     13422024.94
#Sta/Elev= 30
  3890.9  429.60  4021.0  425.00  4118.3  420.46  4168.6  419.35  4198.8  417.19
  4279.3  414.15  4345.2  415.54  4389.5  413.14  4394.5  414.80  4410.0  412.16
  4440.2  409.99  4560.9  407.09  4915.0  405.21  4952.3  404.96  4983.3  405.62
  5010.7  404.02  5011.2  403.22  5016.5  403.22  5017.0  404.02  5045.1  405.38
  5086.5  404.58  5130.2  405.72  5246.3  406.66  5368.1  407.35  5608.3  411.11
  5775.2  415.07  5888.0  418.51  6008.2  421.57  6140.2  423.87  6235.4  425.59
#Mann=8,-1,0
  3890.9     0.1       0  4345.2    0.05       0  4915.0     0.1       0
  5010.7    0.07       0  5017.0     0.1       0  5246.3    0.05       0
  5888.0     0.1       0  6140.2    0.05       0
Bank Sta=5010.7,5017
Exp/Cntr=0.3,0.1

Type RM Length L Ch R = 1,5022,596,596,596
BEGIN DESCRIPTION:
Mapping XS 59ed77fc
END DESCRIPTION:
XS GIS Cut Line= 2
      2043238.12     13422767.13      2045408.26     13422537.10
#Sta/Elev= 30
  3901.2  420.65  3966.2  418.28  3988.6  418.07  4038.8  416.00  4063.9  415.78
  4099.2  413.54  4158.4  411.70  4300.3  407.47  4352.0  406.60  4421.0  404.77
  4471.3  404.86  4662.3  403.88  4702.5  404.35  4766.9  403.97  4918.2  403.97
  4943.9  403.58  4974.1  404.26  4984.1  404.08  5007.7  402.11  5008.2  401.31
  5013.5  401.31  5014.0  402.11  5024.3  403.47  5034.4  403.95  5146.5  405.31
  5356.2  407.85  5546.8  412.79  5772.4  417.97  5969.6  423.99  6083.5  426.12
#Mann=7,-1,0
  3901.2     0.1       0  4158.4    0.05       0  4766.9     0.1       0
  5007.7    0.07       0  5014.0     0.1       0  5146.5    0.05       0
  5546.8     0.1       0
Bank Sta=5007.7,5014
Exp/Cntr=0.3,0.1

Type RM Length L Ch R = 1,4426,75,75,75
BEGIN DESCRIPTION:
Mapping XS d2a12131
END DESCRIPTION:
XS GIS Cut Line= 4
      2043090.61     13423218.52      2044080.18     13423149.07
      2044466.46     13423031.89      2045278.13     13422862.61
#Sta/Elev= 30
  3743.8  418.83  3928.6  415.43  4107.0  409.63  4492.1  402.91  4690.5  401.56
  4767.0  402.62  4772.2  401.16  4799.9  402.45  4805.1  400.34  4832.8  401.89
  4838.0  400.00  4865.7  401.80  4870.9  399.60  4903.8  401.23  4909.1  399.30
  4936.7  399.84  4942.0  398.50  5040.6  399.14  5042.7  398.03  5043.2  397.23
  5049.1  398.03  5063.1  398.30  5108.0  398.92  5111.7  398.35  5145.9  401.83
  5151.0  400.65  5195.9  403.26  5271.4  404.25  5513.6  409.43  5968.6  424.04
#Mann=9,-1,0
  3743.8     0.1       0  4107.0    0.05       0  4492.1     0.1       0
  5042.7    0.07       0  5049.1     0.1       0  5063.1    0.05       0
  5108.0     0.1       0  5271.4    0.05       0  5513.6     0.1       0
Bank Sta=5042.7,5049.1
Exp/Cntr=0.3,0.1

Type RM Length L Ch R = 1,4351,64,64,64
BEGIN DESCRIPTION:
UNT 061 in RCW 6.0
END DESCRIPTION:
XS GIS Cut Line= 3
      2043055.85     13423287.96      2044136.60     13423183.80
      2045317.15     13422945.08
#Sta/Elev= 30
  3672.9  418.61  3792.6  417.13  4066.6  409.29  4447.3  402.63  4587.3  402.03
  4587.8  401.23  4593.2  401.23  4593.7  402.03  4636.5  402.76  4692.9  407.18
  4747.0  408.68  4869.2  408.51  4889.7  409.65  4932.4  409.51  4971.3  408.09
  4991.7  409.34  5028.7  408.54  5033.8  409.73  5052.9  409.82  5070.5  409.03
  5079.5  408.17  5084.6  408.90  5130.2  407.98  5135.3  408.94  5180.9  407.30
  5205.9  408.06  5333.1  406.46  5383.9  406.75  5458.2  408.63  5963.1  424.99
#Mann=7,-1,0
  3672.9     0.1       0  4066.6    0.05       0  4447.3     0.1       0
  4587.3    0.07       0  4593.7     0.1       0  5070.5    0.05       0
  5458.2     0.1       0
Bank Sta=4587.3,4593.7
Exp/Cntr=0.3,0.1

Type RM Length L Ch R = 1,4287,349,349,349
BEGIN DESCRIPTION:
Mapping XS dd346c3e
END DESCRIPTION:
XS GIS Cut Line= 4
      2043081.93     13423322.68      2044184.34     13423231.54
      2044813.68     13423118.69      2045360.28     13423044.94
#Sta/Elev= 30
  3678.0  417.73  3761.3  416.86  3829.2  414.73  3861.7  414.39  3950.1  411.06
  4041.2  409.30  4383.5  403.43  4414.8  402.22  4564.6  402.05  4685.5  405.48
  4787.0  405.19  4796.5  406.02  4812.2  405.82  4937.2  404.09  4967.8  403.03
  4995.0  400.85  4995.5  400.05  5000.9  400.05  5001.4  400.85  5049.0  403.15
  5089.6  404.03  5192.9  405.66  5343.6  406.14  5423.7  408.17  5489.5  409.88
  5546.0  412.50  5697.3  416.60  5889.0  422.84  5935.9  423.77  5975.1  425.45
#Mann=7,-1,0
  3678.0     0.1       0  4041.2    0.05       0  4414.8     0.1       0
  4812.2    0.05       0  4995.0    0.03       0  5001.4    0.05       0
  5423.7     0.1       0
Bank Sta=4995,5001.4
Exp/Cntr=0.3,0.1

Type RM Length L Ch R = 1,3938,308,308,308
BEGIN DESCRIPTION:
UNT 061 in RCW 5.0
END DESCRIPTION:
XS GIS Cut Line= 3
      2043073.27     13423487.61      2044659.03     13423470.66
      2045368.48     13423309.84
#Sta/Elev= 30
  3838.0  417.38  3889.7  415.70  3979.7  414.37  4109.7  413.20  4209.7  413.06
  4239.8  412.31  4299.8  408.37  4349.8  406.17  4451.9  404.09  4533.3  402.90
  4699.8  400.73  4799.8  400.44  4959.8  398.88  4989.8  399.44  5006.6  398.56
  5007.1  397.76  5012.5  397.76  5013.0  398.56  5069.8  400.37  5239.8  399.25
  5280.8  399.58  5423.8  401.26  5501.7  402.77  5544.0  404.31  5656.8  408.28
  5737.6  409.79  5891.4  414.30  5920.7  414.47  6017.2  416.73  6151.3  421.41
#Mann=7,-1,0
  3838.0     0.1       0  4451.9    0.05       0  4533.3     0.1       0
  5006.6    0.07       0  5013.0     0.1       0  5280.8    0.05       0
  5544.0     0.1       0
Bank Sta=5006.6,5013
Exp/Cntr=0.3,0.1

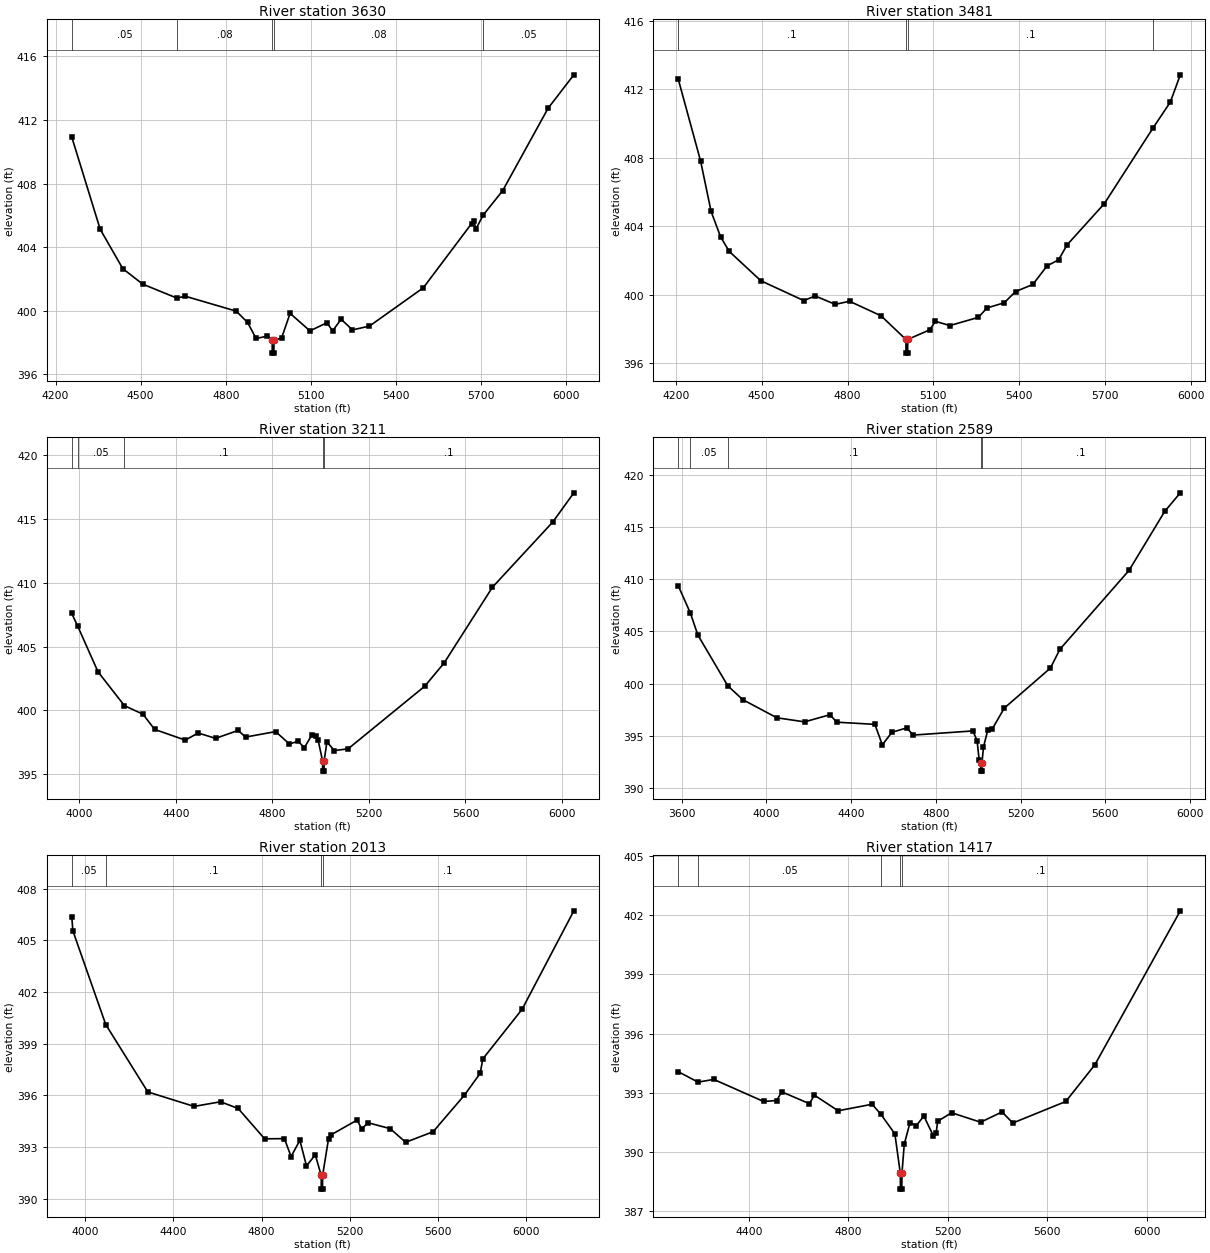
Type RM Length L Ch R = 1,3630,149,149,149
BEGIN DESCRIPTION:
Mapping XS 49ef72ba
END DESCRIPTION:
XS GIS Cut Line= 2
      2043554.97     13423652.55      2045325.83     13423674.25
#Sta/Elev= 30
  4257.0  410.93  4357.0  405.14  4437.0  402.65  4507.1  401.68  4627.9  400.80
  4657.1  400.92  4837.1  399.98  4877.1  399.27  4907.1  398.26  4947.1  398.41
  4963.8  398.14  4964.3  397.34  4969.8  397.34  4970.3  398.14  4997.1  398.29
  5027.1  399.84  5097.1  398.74  5157.1  399.25  5177.1  398.74  5207.1  399.47
  5247.1  398.80  5307.1  399.04  5497.1  401.45  5667.1  405.48  5676.8  405.64
  5681.8  405.12  5708.6  406.03  5777.1  407.56  5937.2  412.74  6028.0  414.84
#Mann=5,-1,0
  4257.0    0.05       0  4627.9    0.08       0  4963.8    0.07       0
  4970.3    0.08       0  5708.6    0.05       0
Bank Sta=4963.8,4970.3
Exp/Cntr=0.3,0.1

Type RM Length L Ch R = 1,3481,270,270,270
BEGIN DESCRIPTION:
Mapping XS 6eeaba47
END DESCRIPTION:
XS GIS Cut Line= 2
      2043576.66     13423791.44      2045330.13     13423769.73
#Sta/Elev= 30
  4208.7  412.59  4287.0  407.79  4323.4  404.86  4357.0  403.36  4387.0  402.52
  4497.1  400.81  4647.1  399.65  4687.1  399.92  4757.1  399.43  4807.1  399.61
  4917.1  398.76  5003.8  397.38  5004.3  396.58  5009.8  396.58  5010.3  397.38
  5087.1  397.94  5107.1  398.44  5157.1  398.19  5257.1  398.67  5287.1  399.22
  5347.1  399.52  5387.1  400.18  5447.1  400.59  5497.1  401.68  5537.1  402.03
  5567.1  402.91  5697.2  405.32  5866.8  409.73  5927.2  411.24  5962.3  412.84
#Mann=4,-1,0
  4208.7     0.1       0  5003.8    0.07       0  5010.3     0.1       0
  5866.8    0.05       0
Bank Sta=5003.8,5010.3
Exp/Cntr=0.3,0.1

Type RM Length L Ch R = 1,3211,622,622,622
BEGIN DESCRIPTION:
Mapping XS b480c2b3
END DESCRIPTION:
XS GIS Cut Line= 3
      2043590.85     13424296.84      2044744.24     13423895.60
      2045601.76     13423856.62
#Sta/Elev= 30
  3969.2  407.60  3993.9  406.60  4077.8  403.03  4187.4  400.37  4264.4  399.70
  4312.4  398.51  4439.5  397.67  4492.4  398.23  4564.8  397.81  4658.1  398.43
  4689.2  397.91  4813.6  398.34  4870.5  397.37  4906.9  397.58  4932.7  397.08
  4963.8  398.08  4979.4  398.00  4989.6  397.67  5008.0  396.04  5008.5  395.24
  5014.0  395.24  5014.5  396.04  5026.0  397.53  5057.1  396.85  5114.0  396.99
  5431.4  401.90  5511.5  403.72  5711.7  409.66  5961.9  414.78  6048.8  417.06
#Mann=5,-1,0
  3969.2     0.1       0  3993.9    0.05       0  4187.4     0.1       0
  5008.0    0.07       0  5014.5     0.1       0
Bank Sta=5008,5014.5
Exp/Cntr=0.3,0.1

Type RM Length L Ch R = 1,2589,576,576,576
BEGIN DESCRIPTION:
Mapping XS 76465e1f
END DESCRIPTION:
XS GIS Cut Line= 3
      2043531.75     13424460.06      2045239.03     13424281.89
      2045820.34     13423982.56
#Sta/Elev= 30
  3583.3  409.39  3640.3  406.78  3676.1  404.65  3816.9  399.79  3888.2  398.45
  4049.1  396.71  4179.8  396.32  4300.4  397.01  4330.6  396.29  4511.6  396.08
  4547.0  394.11  4592.0  395.32  4662.4  395.74  4692.5  395.05  4974.1  395.45
  4994.2  394.53  5004.2  392.62  5011.0  392.39  5011.5  391.59  5017.0  391.59
  5017.5  392.39  5024.1  393.87  5044.4  395.51  5064.6  395.59  5122.6  397.64
  5340.3  401.48  5385.3  403.29  5711.5  410.86  5880.2  416.53  5953.7  418.31
#Mann=5,-1,0
  3583.3     0.1       0  3640.3    0.05       0  3816.9     0.1       0
  5011.0    0.07       0  5017.5     0.1       0
Bank Sta=5011,5017.5
Exp/Cntr=0.3,0.1

Type RM Length L Ch R = 1,2013,596,596,596
BEGIN DESCRIPTION:
Mapping XS 212cdc29
END DESCRIPTION:
XS GIS Cut Line= 3
      2043569.96     13424647.55      2045209.52     13424705.50
      2045818.89     13424512.79
#Sta/Elev= 30
  3938.5  406.37  3943.5  405.55  4092.8  400.11  4283.8  396.20  4493.9  395.36
  4614.0  395.63  4694.0  395.24  4814.1  393.48  4904.1  393.49  4934.2  392.45
  4974.2  393.39  5004.2  391.91  5044.2  392.55  5071.0  391.36  5071.5  390.56
  5077.0  390.56  5077.5  391.36  5104.3  393.48  5114.3  393.70  5234.3  394.57
  5254.4  394.06  5284.4  394.41  5384.4  394.07  5454.5  393.28  5579.1  393.89
  5721.2  396.01  5792.8  397.28  5805.1  398.12  5983.4  401.00  6218.2  406.71
#Mann=4,-1,0
  3938.5    0.05       0  4092.8     0.1       0  5071.0    0.07       0
  5077.5     0.1       0
Bank Sta=5071,5077.5
Exp/Cntr=0.3,0.1

Type RM Length L Ch R = 1,1417,209,209,209
BEGIN DESCRIPTION:
Mapping XS 42f7aeca
END DESCRIPTION:
XS GIS Cut Line= 3
      2043803.92     13425344.15      2044358.11     13425256.50
      2045727.70     13424754.99
#Sta/Elev= 30
  4115.7  394.07  4195.6  393.54  4258.5  393.68  4459.1  392.56  4511.6  392.61
  4531.9  393.05  4643.3  392.45  4663.5  392.88  4758.9  392.09  4895.5  392.42
  4930.4  391.92  4987.1  390.92  5009.0  388.92  5009.5  388.12  5015.1  388.12
  5015.6  388.92  5024.9  390.40  5048.1  391.49  5073.3  391.34  5103.8  391.82
  5142.0  390.82  5152.7  390.94  5159.5  391.56  5215.2  391.99  5332.0  391.51
  5418.2  392.03  5461.5  391.47  5674.5  392.56  5791.6  394.42  6135.3  402.22
#Mann=5,-1,0
  4115.7     0.1       0  4195.6    0.05       0  4930.4     0.1       0
  5009.0    0.07       0  5015.6     0.1       0
Bank Sta=5009,5015.6
Exp/Cntr=0.3,0.1

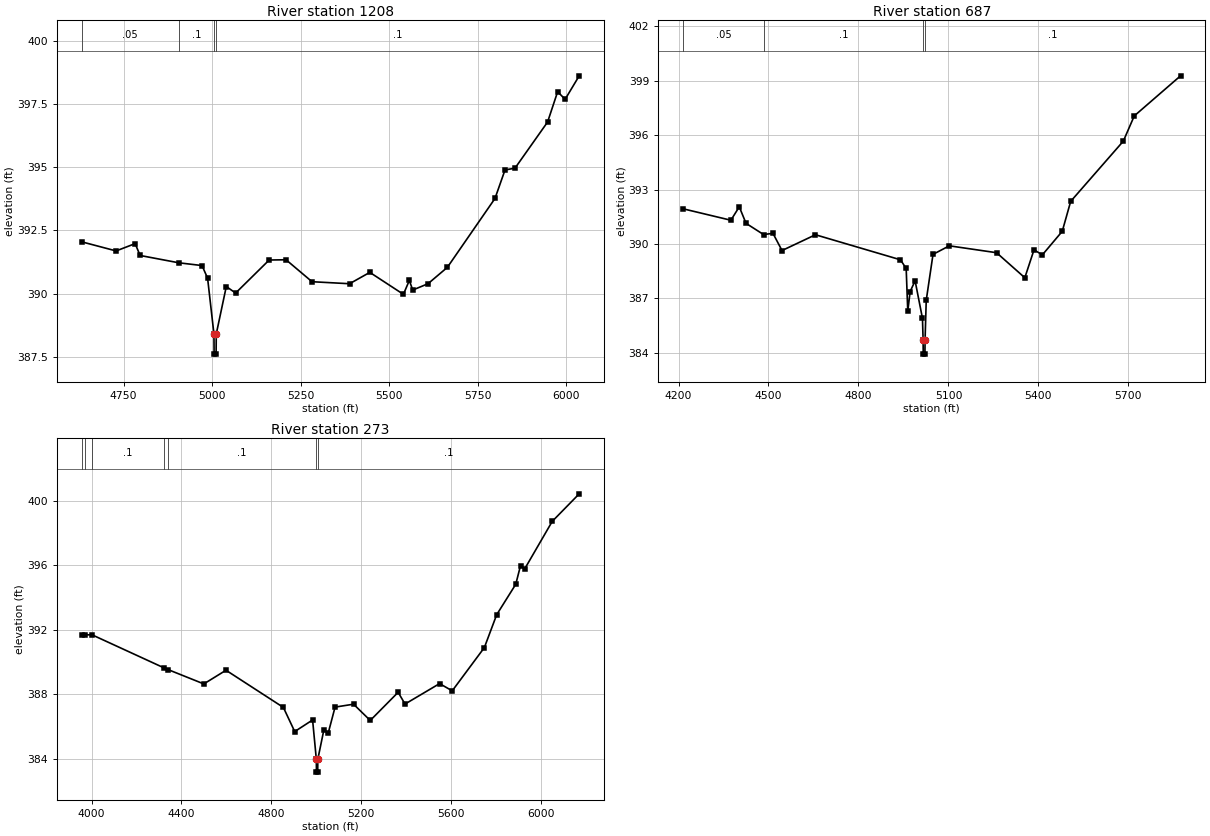
Type RM Length L Ch R = 1,1208,521,521,521
BEGIN DESCRIPTION:
Mapping XS cc8579d1
END DESCRIPTION:
XS GIS Cut Line= 4
      2044356.25     13425304.72      2044655.69     13425351.59
      2045324.96     13425127.63      2045605.68     13424849.50
#Sta/Elev= 30
  4632.0  392.05  4728.9  391.69  4782.6  391.98  4796.6  391.51  4905.8  391.22
  4971.4  391.11  4987.1  390.61  5005.0  388.40  5005.5  387.60  5011.1  387.60
  5011.6  388.40  5039.9  390.28  5066.2  390.02  5160.9  391.33  5208.5  391.34
  5281.9  390.47  5387.8  390.39  5445.0  390.84  5539.8  389.97  5556.5  390.52
  5566.1  390.14  5609.2  390.39  5663.9  391.04  5798.3  393.77  5826.6  394.90
  5854.8  394.97  5946.8  396.80  5975.1  398.00  5996.3  397.70  6036.0  398.63
#Mann=4,-1,0
  4632.0    0.05       0  4905.8     0.1       0  5005.0    0.07       0
  5011.6     0.1       0
Bank Sta=5005,5011.6
Exp/Cntr=0.3,0.1

Type RM Length L Ch R = 1,687,414,414,414
BEGIN DESCRIPTION:
Mapping XS f29ee6ea
END DESCRIPTION:
XS GIS Cut Line= 4
      2044389.20     13425348.72      2044893.54     13425596.99
      2045271.36     13425449.64      2045639.41     13424865.02
#Sta/Elev= 30
  4215.4  391.94  4374.6  391.31  4402.6  392.05  4425.1  391.14  4483.7  390.52
  4514.9  390.59  4545.1  389.64  4656.6  390.51  4940.1  389.13  4959.1  388.65
  4964.4  386.29  4972.3  387.38  4988.9  387.97  5013.4  385.90  5015.5  384.73
  5016.0  383.93  5021.6  383.93  5022.1  384.73  5026.0  386.90  5048.6  389.43
  5103.0  389.90  5260.5  389.52  5354.7  388.14  5385.3  389.68  5413.1  389.40
  5479.5  390.70  5507.6  392.35  5683.1  395.67  5719.6  397.06  5873.9  399.27
#Mann=4,-1,0
  4215.4    0.05       0  4483.7     0.1       0  5015.5    0.07       0
  5022.1     0.1       0
Bank Sta=5015.5,5022.1
Exp/Cntr=0.3,0.1

Type RM Length L Ch R = 1,273,0,0,0
BEGIN DESCRIPTION:
UNT 061 in RCW 1.0
END DESCRIPTION:
XS GIS Cut Line= 4
      2044347.56     13425395.63      2044881.39     13425869.56
      2045339.72     13425890.39      2045691.14     13424908.97
#Sta/Elev= 30
  3956.4  391.70  3971.5  391.69  4002.2  391.69  4320.5  389.65  4340.6  389.53
  4499.9  388.64  4598.6  389.49  4854.1  387.18  4904.6  385.68  4984.2  386.40
  5000.9  383.96  5001.4  383.16  5007.0  383.16  5007.5  383.96  5034.2  385.77
  5054.3  385.61  5084.3  387.20  5166.7  387.38  5241.0  386.37  5365.2  388.12
  5395.9  387.39  5549.8  388.66  5606.0  388.21  5749.2  390.90  5804.0  392.94
  5888.9  394.83  5910.2  395.99  5928.5  395.78  6051.5  398.74  6171.5  400.45
#Mann=7,-1,0
  3956.4     0.1       0  3971.5    0.05       0  4002.2     0.1       0
  4320.5    0.05       0  4340.6     0.1       0  5000.9    0.07       0
  5007.5     0.1       0
Bank Sta=5000.9,5007.5
Exp/Cntr=0.3,0.1

Chan Stop Cuts=-1