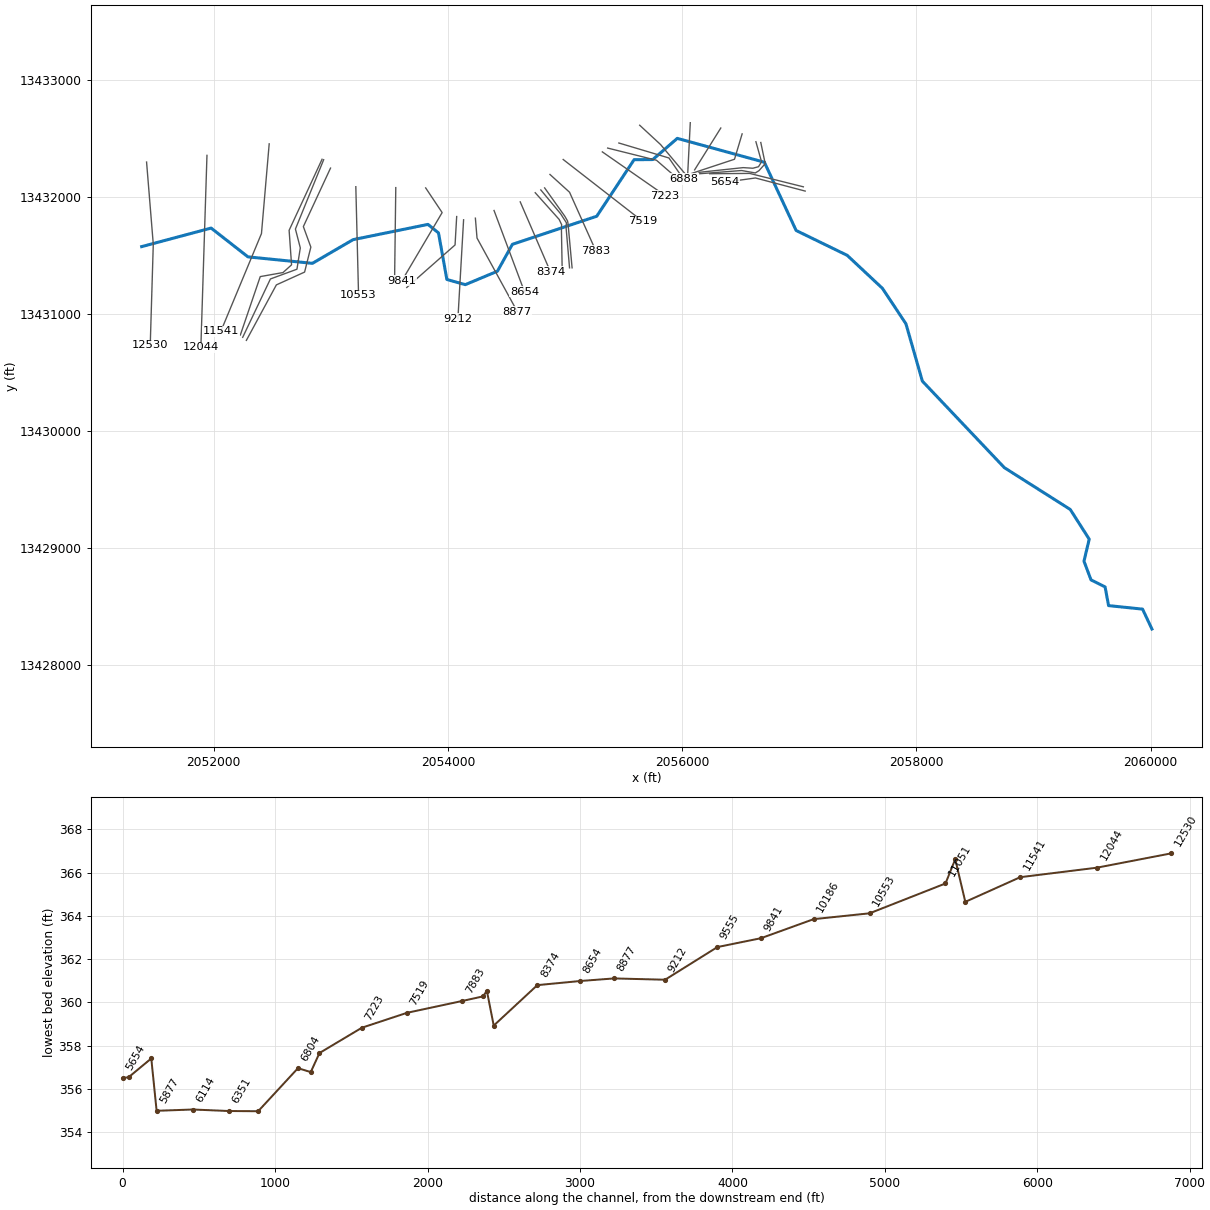
--- UNT 062 in RCW.prj (project) ---

Proj Title=UNT 062 in RCW Base Level Engineering
Current Plan=p01
Default Exp/Contr=0.3,0.1
English Units
Geom File=g01
Flow File=f01
Plan File=p01
BEGIN DESCRIPTION:
UNT 062 in RCW
END DESCRIPTION:

--- UNT 062 in RCW.p01 (plan) ---

Plan Title=Multiple Run
Short Identifier=Multiple
Geom File=g01
Flow File=f01
Subcritical Flow
K Sum by GR= 0
Std Step Tol= 0.01
Critical Tol= 0.01
Num of Std Step Trials= 20
Max Error Tol= 0.3
Flow Tol Ratio= 0.001
Split Flow NTrial= 30
Split Flow Tol= 0.02
Split Flow Ratio= 0.02
Log Output Level= 0
Friction Slope Method= 1
Unsteady Friction Slope Method= 2
Unsteady Bridges Friction Slope Method= 1
Parabolic Critical Depth
Global Vel Dist=  1 , 1 , 1
Global Log Level= 0
CheckData=True
Encroach Param= -1, 0, 0, 0
BEGIN DESCRIPTION:
Multiple Run
END DESCRIPTION:

--- UNT 062 in RCW.f01 (steady flow) ---

Flow Title=Multiple
Number of Profiles=7
Profile Names=10-year,25-year,50-year,1pct_min,100-year,1pct_plu,500-year
River Rch & RM= UNT 062 in RCW,Reach-1,12530
     130     173     206     123     245     490     352
River Rch & RM= UNT 062 in RCW,Reach-1,12044
     165     219     260     154     308     615     438
River Rch & RM= UNT 062 in RCW,Reach-1,690
     164     217     259     153     306     611     435
Boundary for River Rch & Prof#=UNT 062 in RCW,Reach-1,1
Up Type=0
Dn Type=3
Dn Slope=0.005
Boundary for River Rch & Prof#=UNT 062 in RCW,Reach-1,2
Up Type=0
Dn Type=3
Dn Slope=0.005
Boundary for River Rch & Prof#=UNT 062 in RCW,Reach-1,3
Up Type=0
Dn Type=3
Dn Slope=0.005
Boundary for River Rch & Prof#=UNT 062 in RCW,Reach-1,4
Up Type=0
Dn Type=3
Dn Slope=0.005
Boundary for River Rch & Prof#=UNT 062 in RCW,Reach-1,5
Up Type=0
Dn Type=3
Dn Slope=0.005
Boundary for River Rch & Prof#=UNT 062 in RCW,Reach-1,6
Up Type=0
Dn Type=3
Dn Slope=0.005
Boundary for River Rch & Prof#=UNT 062 in RCW,Reach-1,7
Up Type=0
Dn Type=3
Dn Slope=0.005

--- UNT 062 in RCW.g01 (geometry) ---

Geom Title=Existing Conditions

River Reach=UNT 062 in RCW,Reach-1
Reach XY= 30
      2051385.83     13431574.77      2051978.64     13431733.47
      2052293.31     13431487.16      2052843.44     13431431.82
      2053190.80     13431634.54      2053829.76     13431764.94
      2053919.82     13431692.24      2053991.38     13431293.96
      2054148.77     13431249.53      2054423.30     13431364.55
      2054550.80     13431594.54      2055270.80     13431834.54
      2055589.75     13432318.33      2055749.25     13432319.41
      2055958.67     13432500.62      2056701.94     13432296.62
      2056973.21     13431712.86      2057409.41     13431500.18
      2057709.97     13431218.06      2057910.80     13430914.54
      2058050.80     13430424.54      2058750.80     13429684.54
      2059313.70     13429326.79      2059475.38     13429072.88
      2059430.80     13428884.54      2059490.80     13428724.54
      2059610.80     13428664.54      2059640.80     13428504.54
      2059930.80     13428474.54      2060010.80     13428304.54

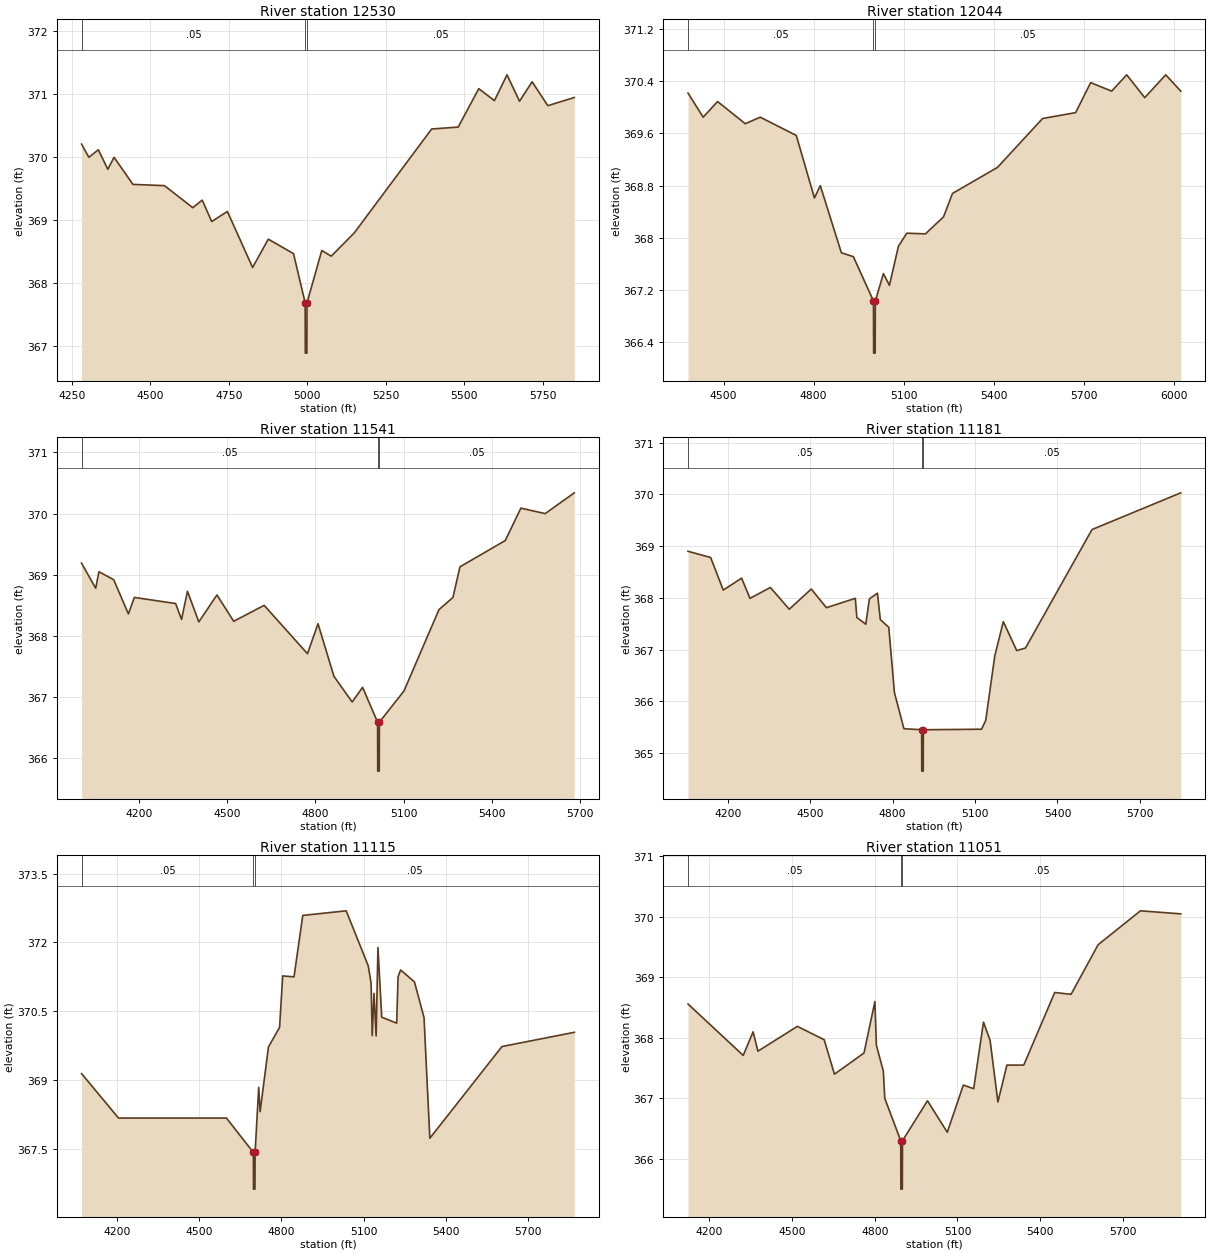
Type RM Length L Ch R = 1,12530,486,486,486
BEGIN DESCRIPTION:
UNT 062 in RCW 10.0
END DESCRIPTION:
XS GIS Cut Line= 3
      2051427.59     13432298.28      2051484.88     13431595.16
      2051458.84     13430730.60
#Sta/Elev= 30
  4280.8  370.21  4304.2  370.00  4334.3  370.12  4364.4  369.81  4384.4  370.00
  4444.6  369.57  4545.0  369.55  4635.3  369.20  4665.4  369.32  4695.5  368.98
  4745.6  369.14  4825.9  368.25  4876.0  368.70  4956.3  368.47  4993.4  367.69
  4993.9  366.89  4998.9  366.89  4999.4  367.69  5046.4  368.52  5076.5  368.43
  5150.0  368.80  5396.6  370.45  5481.1  370.48  5546.7  371.09  5596.7  370.90
  5636.7  371.31  5676.7  370.89  5716.7  371.20  5766.8  370.82  5851.2  370.95
#Mann=3,-1,0
  4280.8    0.05       0  4993.4    0.03       0  4999.4    0.05       0
Bank Sta=4993.4,4999.4
Exp/Cntr=0.3,0.1

Type RM Length L Ch R = 1,12044,503,503,503
BEGIN DESCRIPTION:
Mapping XS c67c9063
END DESCRIPTION:
XS GIS Cut Line= 2
      2051943.22     13432355.52      2051891.13     13430714.95
#Sta/Elev= 30
  4381.5  370.22  4432.0  369.85  4480.0  370.09  4572.1  369.75  4622.1  369.85
  4742.2  369.57  4802.6  368.61  4822.2  368.80  4892.3  367.77  4932.3  367.71
  4999.3  367.03  4999.8  366.23  5004.9  366.23  5005.4  367.03  5032.4  367.45
  5052.4  367.27  5082.4  367.87  5110.3  368.07  5172.4  368.06  5232.5  368.32
  5262.5  368.68  5412.5  369.08  5562.6  369.83  5672.7  369.92  5722.7  370.38
  5792.7  370.25  5842.8  370.50  5902.8  370.15  5972.8  370.50  6022.9  370.25
#Mann=3,-1,0
  4381.5    0.05       0  4999.3    0.03       0  5005.4    0.05       0
Bank Sta=4999.3,5005.4
Exp/Cntr=0.3,0.1

Type RM Length L Ch R = 1,11541,360,360,360
BEGIN DESCRIPTION:
Mapping XS 5f7ef348
END DESCRIPTION:
XS GIS Cut Line= 3
      2052474.47     13432453.86      2052408.50     13431686.48
      2052061.35     13430849.85
#Sta/Elev= 30
  4004.4  369.19  4052.5  368.78  4063.5  369.05  4113.7  368.92  4163.8  368.36
  4183.9  368.63  4324.4  368.53  4344.5  368.27  4364.6  368.73  4403.3  368.23
  4464.9  368.67  4521.9  368.24  4625.5  368.50  4772.8  367.71  4808.7  368.20
  4862.8  367.34  4924.8  366.92  4960.3  367.16  5011.3  366.59  5011.8  365.79
  5016.9  365.79  5017.4  366.59  5101.0  367.10  5220.1  368.43  5267.6  368.63
  5291.5  369.13  5445.6  369.56  5498.7  370.09  5581.2  370.00  5680.4  370.34
#Mann=3,-1,0
  4004.4    0.05       0  5011.3    0.03       0  5017.4    0.05       0
Bank Sta=5011.3,5017.4
Exp/Cntr=0.3,0.1

Type RM Length L Ch R = 1,11181,66,66,66
BEGIN DESCRIPTION:
Mapping XS 45fe5d95
END DESCRIPTION:
XS GIS Cut Line= 6
      2052925.87     13432321.92      2052644.61     13431714.25
      2052665.44     13431419.11      2052592.52     13431353.14
      2052398.08     13431318.42      2052228.20     13430819.19
#Sta/Elev= 30
  4055.8  368.90  4138.1  368.78  4184.0  368.15  4250.8  368.38  4281.2  367.99
  4355.5  368.20  4424.2  367.78  4504.2  368.17  4559.3  367.81  4664.5  367.99
  4670.0  367.62  4702.5  367.49  4715.8  367.98  4744.9  368.09  4755.4  367.58
  4786.2  367.43  4806.7  366.17  4841.3  365.47  4905.7  365.45  4906.2  364.65
  4911.5  364.65  4912.0  365.45  5123.6  365.46  5138.9  365.63  5171.9  366.88
  5202.9  367.54  5251.7  366.98  5283.6  367.03  5525.5  369.32  5848.5  370.03
#Mann=3,-1,0
  4055.8    0.05       0  4905.7    0.03       0  4912.0    0.05       0
Bank Sta=4905.7,4912
Exp/Cntr=0.3,0.1

Type RM Length L Ch R = 1,11115,64,64,64
BEGIN DESCRIPTION:
Mapping XS feb5d51f
END DESCRIPTION:
XS GIS Cut Line= 6
      2052939.50     13432318.06      2052698.43     13431725.36
      2052740.09     13431563.91      2052711.45     13431381.61
      2052484.88     13431298.28      2052248.32     13430799.15
#Sta/Elev= 30
  4071.4  369.14  4206.2  368.17  4599.6  368.17  4697.7  367.42  4698.2  366.62
  4703.5  366.62  4704.0  367.42  4717.2  368.84  4722.3  368.31  4752.7  369.72
  4793.3  370.15  4804.6  371.27  4845.9  371.25  4877.8  372.59  5036.1  372.69
  5116.5  371.49  5126.9  371.11  5130.9  369.97  5137.5  370.89  5145.2  369.96
  5151.8  371.89  5165.6  370.37  5220.1  370.24  5225.1  371.25  5234.5  371.40
  5284.9  371.14  5319.8  370.36  5341.0  367.73  5603.9  369.73  5867.6  370.04
#Mann=3,-1,0
  4071.4    0.05       0  4697.7    0.03       0  4704.0    0.05       0
Bank Sta=4697.7,4704
Exp/Cntr=0.3,0.1

Type RM Length L Ch R = 1,11051,498,498,498
BEGIN DESCRIPTION:
Mapping XS fbf7240f
END DESCRIPTION:
XS GIS Cut Line= 6
      2052998.08     13432246.42      2052766.13     13431746.20
      2052830.12     13431570.66      2052776.74     13431357.12
      2052535.67     13431247.50      2052279.59     13430773.05
#Sta/Elev= 30
  4123.5  368.56  4323.5  367.71  4359.4  368.10  4376.8  367.78  4519.7  368.19
  4616.9  367.97  4654.2  367.40  4761.3  367.75  4800.8  368.60  4806.1  367.88
  4831.3  367.45  4836.6  367.00  4894.4  366.30  4894.9  365.50  4900.2  365.50
  4900.7  366.30  4991.4  366.96  5063.1  366.44  5121.3  367.22  5158.8  367.16
  5194.3  368.26  5218.2  367.96  5246.6  366.94  5279.2  367.55  5340.3  367.55
  5452.5  368.75  5511.7  368.72  5609.8  369.54  5763.1  370.10  5909.3  370.05
#Mann=3,-1,0
  4123.5    0.05       0  4894.4    0.03       0  4900.7    0.05       0
Bank Sta=4894.4,4900.7
Exp/Cntr=0.3,0.1

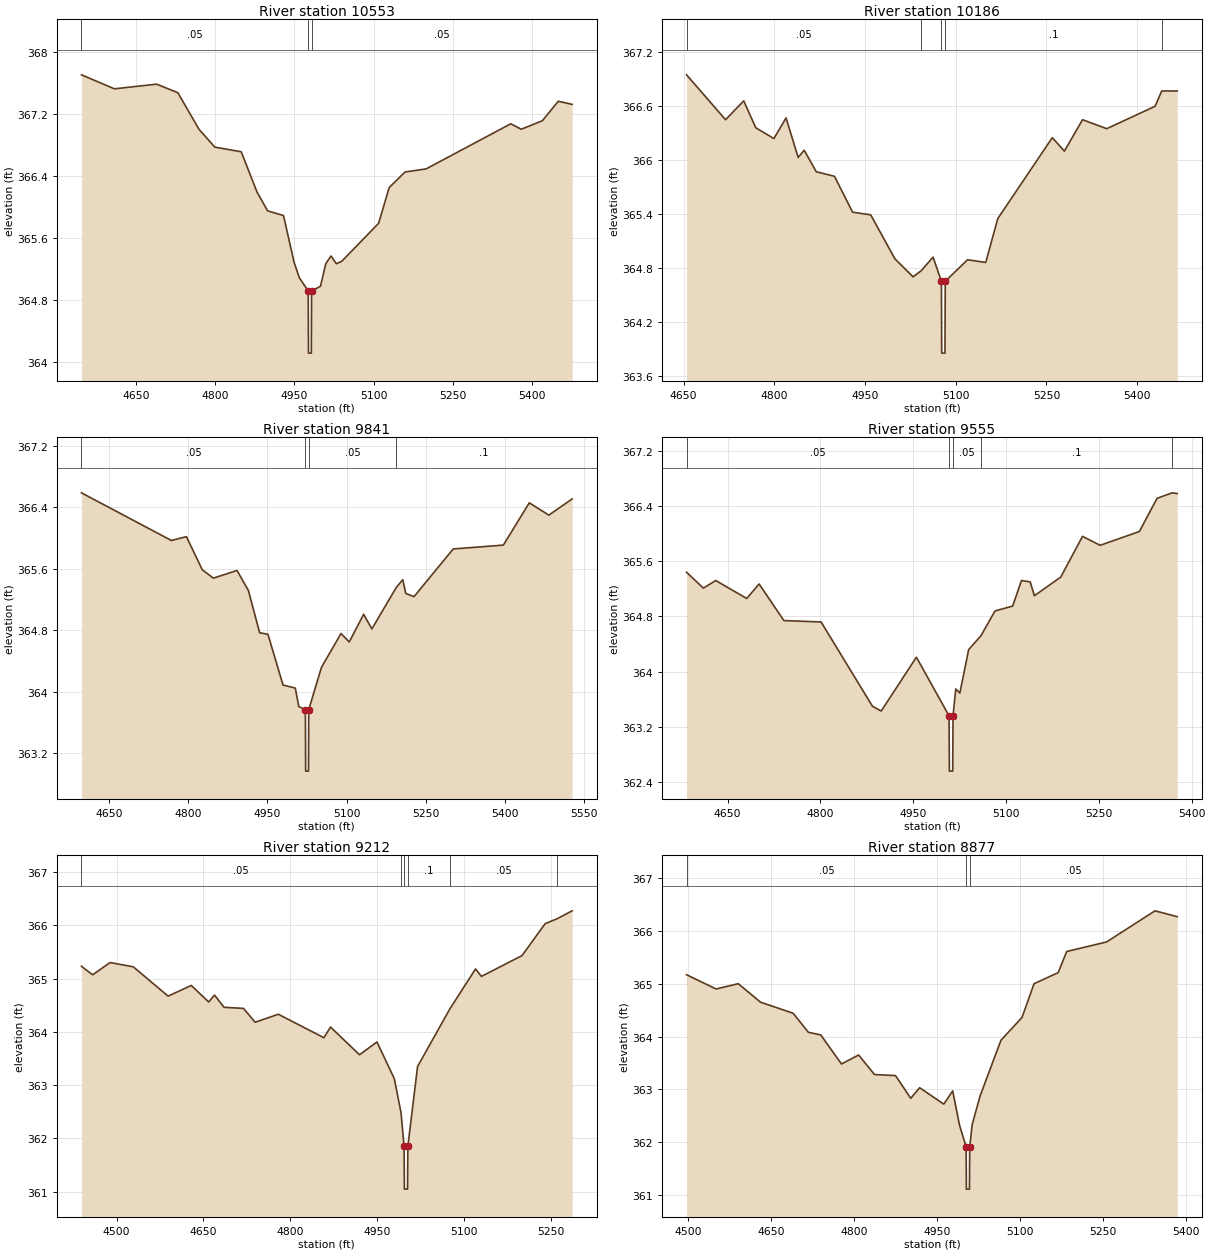
Type RM Length L Ch R = 1,10553,367,367,367
BEGIN DESCRIPTION:
Mapping XS c2243fc1
END DESCRIPTION:
XS GIS Cut Line= 2
      2053214.05     13432087.39      2053237.46     13431158.79
#Sta/Elev= 30
  4547.0  367.70  4609.4  367.52  4689.4  367.58  4729.5  367.47  4769.5  367.00
  4799.5  366.77  4849.5  366.71  4879.5  366.19  4899.5  365.95  4929.5  365.89
  4949.5  365.29  4959.5  365.09  4976.3  364.92  4976.8  364.12  4982.2  364.12
  4982.7  364.92  4999.5  364.98  5009.5  365.27  5019.5  365.37  5029.5  365.27
  5039.6  365.30  5109.6  365.79  5129.6  366.25  5159.6  366.45  5199.6  366.49
  5359.7  367.07  5379.7  367.00  5419.7  367.11  5449.7  367.36  5475.9  367.32
#Mann=3,-1,0
  4547.0    0.05       0  4976.3    0.03       0  4982.7    0.05       0
Bank Sta=4976.3,4982.7
Exp/Cntr=0.3,0.1

Type RM Length L Ch R = 1,10186,345,345,345
BEGIN DESCRIPTION:
Mapping XS c22f8ee1
END DESCRIPTION:
XS GIS Cut Line= 2
      2053555.20     13432079.51      2053544.80     13431268.48
#Sta/Elev= 30
  4655.0  366.95  4719.5  366.45  4749.5  366.66  4769.5  366.36  4799.5  366.24
  4819.5  366.47  4839.5  366.03  4849.5  366.11  4869.5  365.87  4899.5  365.82
  4929.5  365.42  4959.5  365.39  4999.5  364.90  5029.5  364.70  5043.3  364.77
  5062.5  364.92  5076.3  364.65  5076.8  363.85  5082.2  363.85  5082.7  364.65
  5119.5  364.89  5149.6  364.86  5169.6  365.35  5259.6  366.25  5279.6  366.10
  5309.6  366.45  5349.6  366.35  5429.6  366.60  5440.5  366.77  5466.1  366.77
#Mann=5,-1,0
  4655.0    0.05       0  5043.3     0.1       0  5076.3    0.03       0
  5082.7     0.1       0  5440.5    0.05       0
Bank Sta=5076.3,5082.7
Exp/Cntr=0.3,0.1

Type RM Length L Ch R = 1,9841,286,286,286
BEGIN DESCRIPTION:
Mapping XS 0c89291c
END DESCRIPTION:
XS GIS Cut Line= 3
      2053810.41     13432076.93      2053951.03     13431865.99
      2053607.28     13431282.65
#Sta/Elev= 30
  4597.3  366.59  4767.9  365.97  4796.4  366.02  4826.4  365.59  4847.5  365.48
  4892.4  365.58  4913.9  365.32  4935.3  364.77  4951.0  364.75  4979.6  364.09
  5002.9  364.05  5009.5  363.81  5022.0  363.77  5022.5  362.97  5027.9  362.97
  5028.4  363.77  5052.5  364.32  5089.6  364.76  5105.2  364.65  5132.5  365.01
  5148.1  364.82  5194.5  365.36  5206.7  365.46  5212.5  365.28  5228.1  365.24
  5302.4  365.86  5397.5  365.91  5446.7  366.46  5483.8  366.30  5527.9  366.51
#Mann=4,-1,0
  4597.3    0.05       0  5022.0    0.03       0  5028.4    0.05       0
  5194.5     0.1       0
Bank Sta=5022,5028.4
Exp/Cntr=0.3,0.1

Type RM Length L Ch R = 1,9555,343,343,343
BEGIN DESCRIPTION:
Mapping XS 2ee3e0ca
END DESCRIPTION:
XS GIS Cut Line= 3
      2054075.16     13431832.11      2054061.27     13431589.08
      2053649.03     13431225.34
#Sta/Elev= 30
  4583.5  365.44  4610.7  365.21  4630.7  365.32  4680.8  365.06  4700.8  365.27
  4740.9  364.74  4801.0  364.72  4884.0  363.50  4898.2  363.43  4955.1  364.21
  5007.9  363.36  5008.4  362.56  5013.8  362.56  5014.3  363.36  5018.7  363.75
  5025.3  363.69  5039.6  364.32  5059.4  364.52  5082.2  364.88  5110.7  364.95
  5124.9  365.32  5139.1  365.30  5145.8  365.10  5188.5  365.37  5223.6  365.96
  5252.1  365.83  5315.6  366.03  5344.1  366.51  5368.5  366.59  5376.7  366.58
#Mann=5,-1,0
  4583.5    0.05       0  5007.9    0.03       0  5014.3    0.05       0
  5059.4     0.1       0  5368.5    0.05       0
Bank Sta=5007.9,5014.3
Exp/Cntr=0.3,0.1

Type RM Length L Ch R = 1,9212,335,335,335
BEGIN DESCRIPTION:
Mapping XS f87c5fde
END DESCRIPTION:
XS GIS Cut Line= 2
      2054134.19     13431804.32      2054085.66     13430958.61
#Sta/Elev= 30
  4439.3  365.23  4458.6  365.07  4488.7  365.30  4528.8  365.22  4588.9  364.67
  4628.9  364.87  4659.0  364.56  4669.0  364.69  4685.5  364.46  4719.1  364.44
  4739.1  364.18  4779.2  364.33  4857.9  363.89  4869.3  364.09  4919.4  363.57
  4949.5  363.81  4979.5  363.12  4991.1  362.48  4996.3  361.85  4996.8  361.05
  5002.3  361.05  5002.8  361.85  5019.6  363.35  5075.3  364.43  5119.7  365.18
  5129.8  365.04  5199.9  365.43  5239.9  366.03  5260.2  366.12  5286.4  366.27
#Mann=6,-1,0
  4439.3    0.05       0  4991.1     0.1       0  4996.3    0.07       0
  5002.8     0.1       0  5075.3    0.05       0  5260.2     0.1       0
Bank Sta=4996.3,5002.8
Exp/Cntr=0.3,0.1

Type RM Length L Ch R = 1,8877,223,223,223
BEGIN DESCRIPTION:
Mapping XS 9f810d3f
END DESCRIPTION:
XS GIS Cut Line= 3
      2054234.89     13431818.22      2054248.77     13431648.11
      2054592.42     13431019.83
#Sta/Elev= 30
  4497.1  365.17  4550.5  364.90  4590.6  365.00  4630.8  364.65  4689.8  364.44
  4717.3  364.08  4739.7  364.03  4777.1  363.48  4808.1  363.65  4836.8  363.28
  4874.8  363.26  4902.3  362.83  4918.4  363.03  4962.0  362.72  4978.1  362.97
  4990.5  362.32  5002.4  361.91  5002.9  361.11  5008.4  361.11  5008.9  361.91
  5013.3  362.33  5027.5  362.87  5065.4  363.93  5103.4  364.36  5125.2  365.00
  5168.8  365.21  5184.2  365.61  5256.1  365.79  5343.8  366.38  5383.9  366.27
#Mann=3,-1,0
  4497.1    0.05       0  5002.4    0.03       0  5008.9    0.05       0
Bank Sta=5002.4,5008.9
Exp/Cntr=0.3,0.1

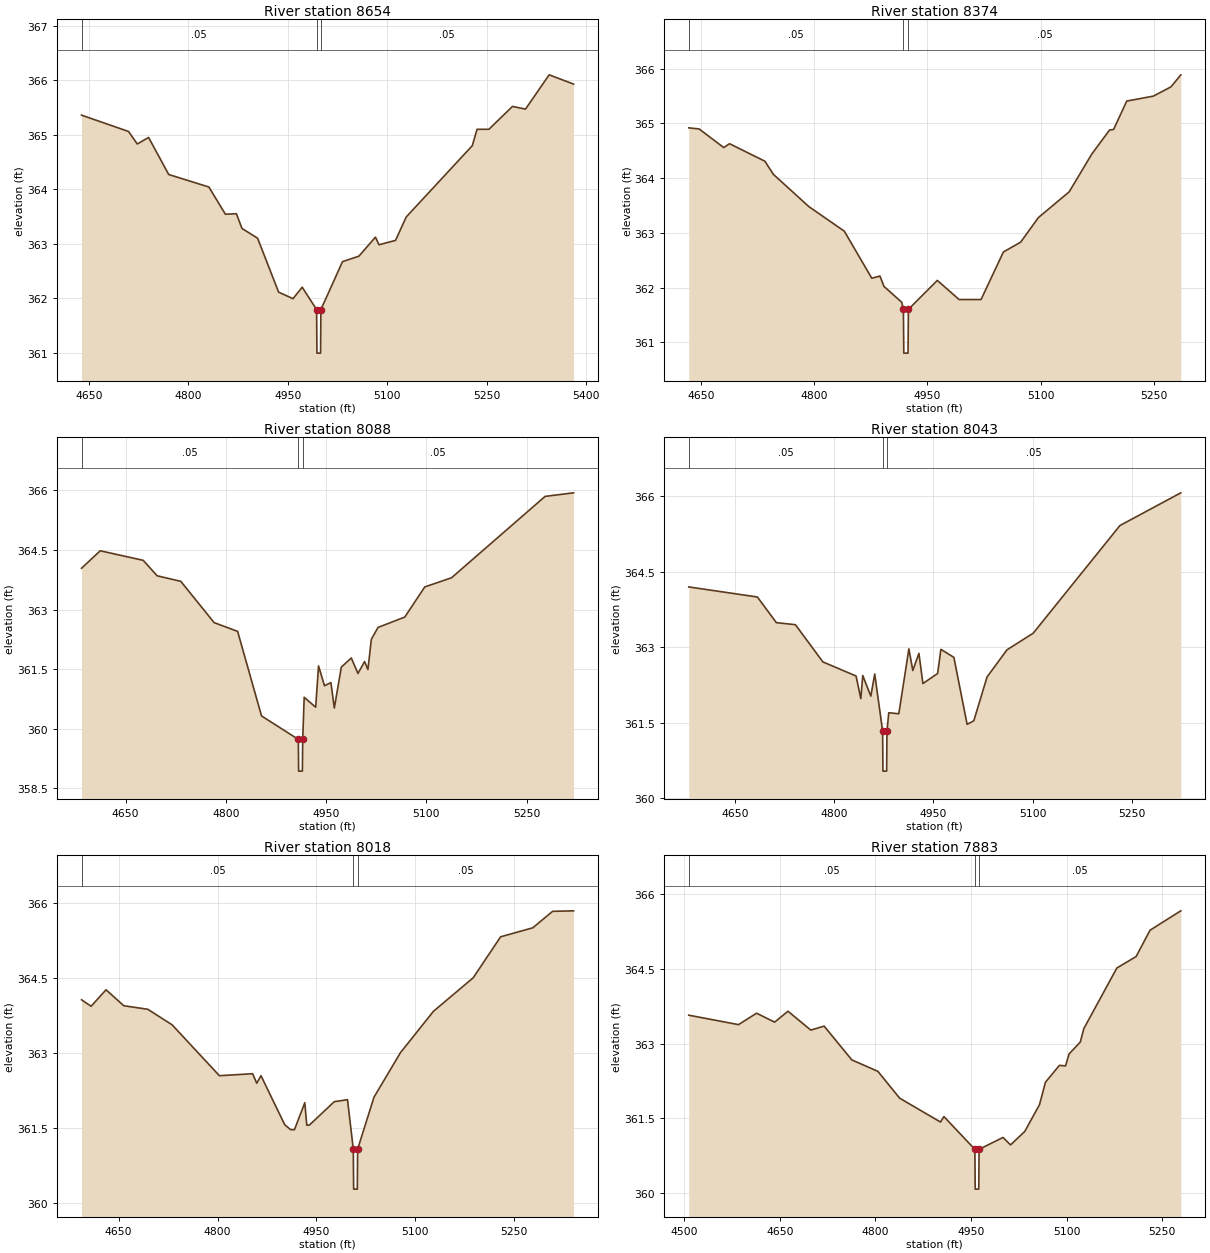
Type RM Length L Ch R = 1,8654,280,280,280
BEGIN DESCRIPTION:
Mapping XS de55fb23
END DESCRIPTION:
XS GIS Cut Line= 2
      2054394.17     13431883.80      2054654.06     13431188.59
#Sta/Elev= 30
  4639.1  365.36  4710.0  365.06  4723.2  364.83  4740.3  364.95  4770.6  364.27
  4831.2  364.04  4856.2  363.54  4872.7  363.55  4881.1  363.28  4904.7  363.10
  4936.4  362.11  4958.1  361.99  4972.0  362.20  4993.7  361.79  4994.2  360.99
  4999.7  360.99  5000.2  361.79  5032.8  362.67  5057.5  362.77  5082.5  363.12
  5087.8  362.98  5112.8  363.06  5128.9  363.49  5228.6  364.80  5235.7  365.10
  5253.6  365.10  5289.2  365.52  5308.8  365.47  5344.5  366.10  5381.3  365.93
#Mann=3,-1,0
  4639.1    0.05       0  4993.7    0.03       0  5000.2    0.05       0
Bank Sta=4993.7,5000.2
Exp/Cntr=0.3,0.1

Type RM Length L Ch R = 1,8374,286,286,286
BEGIN DESCRIPTION:
Mapping XS 80f19317
END DESCRIPTION:
XS GIS Cut Line= 2
      2054617.71     13431957.53      2054875.66     13431359.27
#Sta/Elev= 30
  4634.0  364.92  4647.7  364.90  4680.3  364.56  4688.0  364.63  4734.8  364.31
  4746.0  364.07  4793.0  363.48  4840.0  363.03  4876.3  362.17  4887.1  362.21
  4892.5  362.02  4916.0  361.73  4918.2  361.60  4918.7  360.80  4924.3  360.80
  4924.8  361.60  4963.1  362.13  4992.0  361.78  5021.0  361.78  5050.6  362.65
  5073.5  362.83  5097.0  363.28  5137.7  363.75  5167.6  364.44  5191.1  364.88
  5196.5  364.89  5213.9  365.41  5249.0  365.50  5272.5  365.67  5285.5  365.89
#Mann=3,-1,0
  4634.0    0.05       0  4918.2    0.03       0  4924.8    0.05       0
Bank Sta=4918.2,4924.8
Exp/Cntr=0.3,0.1

Type RM Length L Ch R = 1,8088,45,45,45
BEGIN DESCRIPTION:
Mapping XS 6785d044
END DESCRIPTION:
XS GIS Cut Line= 5
      2054745.70     13432035.73      2054949.73     13431807.83
      2054971.43     13431762.26      2054969.26     13431729.71
      2054975.77     13431382.45
#Sta/Elev= 30
  4584.1  364.04  4612.1  364.48  4676.4  364.24  4697.3  363.85  4732.7  363.71
  4782.6  362.67  4817.7  362.45  4853.5  360.32  4908.5  359.73  4909.0  358.93
  4914.6  358.93  4915.1  359.73  4917.3  360.79  4934.5  360.54  4938.8  361.58
  4947.7  361.08  4957.3  361.16  4962.4  360.52  4972.9  361.55  4987.8  361.78
  4997.8  361.39  5007.7  361.69  5012.7  361.49  5017.8  362.25  5027.8  362.55
  5067.8  362.81  5097.8  363.57  5137.8  363.80  5277.8  365.85  5320.4  365.94
#Mann=3,-1,0
  4584.1    0.05       0  4908.5    0.03       0  4915.1    0.05       0
Bank Sta=4908.5,4915.1
Exp/Cntr=0.3,0.1

Type RM Length L Ch R = 1,8043,25,25,25
BEGIN DESCRIPTION:
Mapping XS 906b20e3
END DESCRIPTION:
XS GIS Cut Line= 5
      2054793.50     13432059.54      2054962.75     13431855.57
      2055012.66     13431777.45      2055008.32     13431747.07
      2055038.71     13431393.31
#Sta/Elev= 30
  4580.6  364.20  4684.3  364.00  4713.0  363.49  4741.7  363.45  4783.3  362.71
  4833.4  362.43  4840.6  361.98  4843.5  362.44  4855.7  362.03  4861.6  362.47
  4873.5  361.34  4874.0  360.54  4879.6  360.54  4880.1  361.34  4882.8  361.70
  4898.0  361.68  4913.2  362.97  4919.1  362.54  4928.4  362.88  4934.4  362.28
  4956.6  362.48  4961.6  362.96  4981.2  362.80  5001.2  361.47  5011.3  361.54
  5031.3  362.41  5061.4  362.95  5101.0  363.28  5232.1  365.42  5324.1  366.07
#Mann=3,-1,0
  4580.6    0.05       0  4873.5    0.03       0  4880.1    0.05       0
Bank Sta=4873.5,4880.1
Exp/Cntr=0.3,0.1

Type RM Length L Ch R = 1,8018,135,135,135
BEGIN DESCRIPTION:
Mapping XS 1da3796c
END DESCRIPTION:
XS GIS Cut Line= 5
      2054826.04     13432076.91      2054997.47     13431836.04
      2055021.34     13431794.81      2055025.68     13431773.11
      2055060.41     13431393.31
#Sta/Elev= 30
  4593.6  364.07  4608.2  363.94  4630.8  364.27  4657.8  363.95  4694.1  363.88
  4731.0  363.57  4802.9  362.55  4853.3  362.59  4859.5  362.40  4866.0  362.55
  4902.0  361.57  4911.0  361.47  4916.8  361.47  4932.5  362.01  4935.5  361.56
  4939.3  361.56  4977.2  362.03  4997.3  362.07  5006.1  361.08  5006.6  360.28
  5012.2  360.28  5012.7  361.08  5037.5  362.12  5077.6  363.01  5127.8  363.84
  5188.1  364.51  5229.7  365.33  5278.5  365.51  5308.6  365.84  5340.4  365.85
#Mann=3,-1,0
  4593.6    0.05       0  5006.1    0.03       0  5012.7    0.05       0
Bank Sta=5006.1,5012.7
Exp/Cntr=0.3,0.1

Type RM Length L Ch R = 1,7883,364,364,364
BEGIN DESCRIPTION:
Mapping XS 392feee0
END DESCRIPTION:
XS GIS Cut Line= 3
      2054871.59     13432191.95      2055038.70     13432040.04
      2055262.21     13431540.94
#Sta/Elev= 30
  4506.8  363.57  4584.9  363.38  4613.3  363.61  4641.6  363.43  4662.6  363.65
  4698.4  363.27  4719.4  363.35  4762.9  362.67  4803.8  362.44  4838.0  361.90
  4902.1  361.42  4907.5  361.53  4956.1  360.87  4956.6  360.07  4962.2  360.07
  4962.7  360.87  5000.3  361.11  5012.1  360.96  5034.4  361.23  5057.6  361.77
  5066.9  362.22  5088.8  362.56  5098.5  362.55  5104.0  362.79  5121.7  363.03
  5127.2  363.30  5179.1  364.52  5209.3  364.75  5231.2  365.28  5279.5  365.67
#Mann=3,-1,0
  4506.8    0.05       0  4956.1    0.03       0  4962.7    0.05       0
Bank Sta=4956.1,4962.7
Exp/Cntr=0.3,0.1

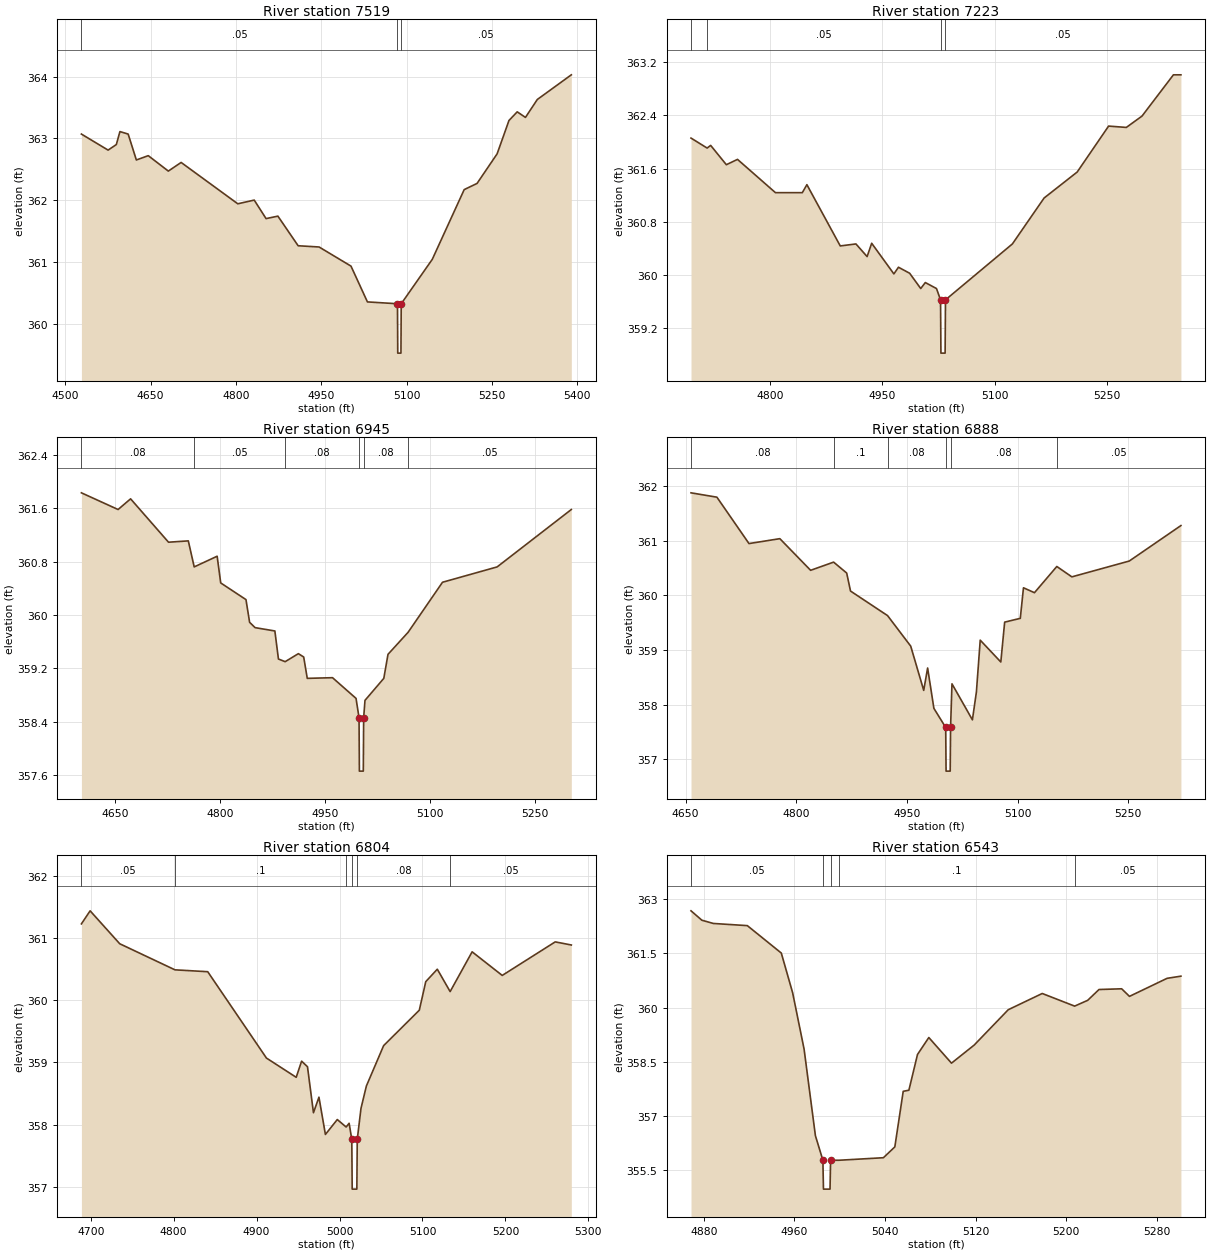
Type RM Length L Ch R = 1,7519,296,296,296
BEGIN DESCRIPTION:
Mapping XS a9ac753d
END DESCRIPTION:
XS GIS Cut Line= 2
      2054984.48     13432319.96      2055663.68     13431790.48
#Sta/Elev= 30
  4528.5  363.07  4575.4  362.81  4589.9  362.90  4596.2  363.11  4610.7  363.07
  4625.1  362.65  4646.0  362.72  4681.3  362.47  4703.8  362.61  4803.4  361.94
  4832.3  362.00  4853.1  361.70  4873.9  361.74  4909.5  361.26  4946.3  361.24
  5002.4  360.93  5031.3  360.35  5084.1  360.32  5084.6  359.52  5090.2  359.52
  5090.7  360.32  5145.3  361.04  5201.4  362.17  5224.0  362.27  5259.3  362.75
  5280.1  363.29  5294.6  363.43  5309.1  363.34  5329.9  363.63  5389.7  364.03
#Mann=3,-1,0
  4528.5    0.05       0  5084.1    0.03       0  5090.7    0.05       0
Bank Sta=5084.1,5090.7
Exp/Cntr=0.3,0.1

Type RM Length L Ch R = 1,7223,278,278,278
BEGIN DESCRIPTION:
Mapping XS e4d59e27
END DESCRIPTION:
XS GIS Cut Line= 2
      2055318.66     13432385.08      2055854.70     13432011.81
#Sta/Elev= 30
  4694.9  362.06  4716.4  361.91  4721.1  361.95  4742.0  361.66  4756.9  361.74
  4807.5  361.24  4843.3  361.24  4849.4  361.36  4893.9  360.44  4914.8  360.47
  4929.7  360.28  4935.8  360.48  4965.4  360.02  4971.5  360.12  4986.4  360.03
  5001.2  359.80  5007.3  359.89  5022.2  359.80  5027.6  359.63  5028.1  358.83
  5033.7  358.83  5034.2  359.63  5123.4  360.47  5165.7  361.16  5209.8  361.55
  5251.7  362.24  5275.3  362.22  5296.2  362.39  5338.1  363.01  5348.1  363.01
#Mann=4,-1,0
  4694.9    0.08       0  4716.4    0.05       0  5027.6    0.03       0
  5034.2    0.05       0
Bank Sta=5027.6,5034.2
Exp/Cntr=0.3,0.1

Type RM Length L Ch R = 1,6945,57,57,57
BEGIN DESCRIPTION:
Mapping XS 001434a8
END DESCRIPTION:
XS GIS Cut Line= 3
      2055364.19     13432417.65      2055780.89     13432313.47
      2055984.86     13432135.54
#Sta/Elev= 30
  4602.0  361.83  4654.4  361.58  4672.3  361.74  4726.5  361.09  4754.8  361.11
  4763.2  360.72  4796.0  360.88  4801.1  360.48  4837.2  360.23  4842.4  359.89
  4850.2  359.81  4878.5  359.76  4883.6  359.34  4893.2  359.30  4912.1  359.42
  4919.7  359.37  4924.8  359.05  4960.9  359.06  4994.5  358.75  4998.8  358.46
  4999.3  357.66  5004.9  357.66  5005.4  358.46  5007.3  358.72  5034.2  359.05
  5040.2  359.41  5068.9  359.74  5118.1  360.49  5196.2  360.72  5302.2  361.58
#Mann=6,-1,0
  4602.0    0.08       0  4763.2    0.05       0  4893.2    0.08       0
  4998.8    0.07       0  5005.4    0.08       0  5068.9    0.05       0
Bank Sta=4998.8,5005.4
Exp/Cntr=0.3,0.1

Type RM Length L Ch R = 1,6888,84,84,84
BEGIN DESCRIPTION:
Mapping XS fdd26aa7
END DESCRIPTION:
XS GIS Cut Line= 3
      2055459.68     13432461.05      2055887.23     13432333.00
      2056010.46     13432153.56
#Sta/Elev= 30
  4657.3  361.88  4692.4  361.80  4735.9  360.95  4777.7  361.04  4819.4  360.46
  4850.6  360.61  4868.3  360.41  4873.5  360.08  4923.7  359.63  4955.1  359.07
  4972.7  358.26  4978.0  358.67  4986.5  357.93  5002.5  357.58  5003.0  356.78
  5008.6  356.78  5009.1  357.58  5011.0  358.38  5038.7  357.72  5044.1  358.23
  5049.3  359.18  5077.2  358.78  5082.4  359.51  5103.6  359.58  5107.9  360.14
  5122.8  360.05  5153.1  360.53  5173.5  360.34  5251.3  360.63  5321.3  361.28
#Mann=6,-1,0
  4657.3    0.08       0  4850.6     0.1       0  4923.7    0.08       0
  5002.5    0.07       0  5009.1    0.08       0  5153.1    0.05       0
Bank Sta=5002.5,5009.1
Exp/Cntr=0.3,0.1

Type RM Length L Ch R = 1,6804,261,261,261
BEGIN DESCRIPTION:
Mapping XS 8eb4be33
END DESCRIPTION:
XS GIS Cut Line= 3
      2055637.70     13432612.92      2055815.61     13432448.02
      2056039.11     13432181.12
#Sta/Elev= 30
  4688.8  361.23  4699.3  361.44  4735.0  360.91  4801.6  360.49  4841.1  360.46
  4911.9  359.07  4947.8  358.76  4954.3  359.02  4961.4  358.93  4968.6  358.19
  4975.2  358.44  4983.0  357.84  4997.3  358.08  5008.0  357.96  5011.6  358.02
  5014.8  357.76  5015.3  356.96  5020.9  356.96  5021.4  357.76  5025.9  358.26
  5032.4  358.62  5053.2  359.27  5096.2  359.84  5104.0  360.30  5117.9  360.50
  5133.4  360.14  5159.9  360.78  5196.2  360.40  5260.1  360.94  5279.5  360.89
#Mann=6,-1,0
  4688.8    0.05       0  4801.6     0.1       0  5008.0    0.08       0
  5014.8    0.07       0  5021.4    0.08       0  5133.4    0.05       0
Bank Sta=5014.8,5021.4
Exp/Cntr=0.3,0.1

Type RM Length L Ch R = 1,6543,192,192,192
BEGIN DESCRIPTION:
Mapping XS 3037a3b7
END DESCRIPTION:
XS GIS Cut Line= 2
      2056069.52     13432634.63      2056047.82     13432202.78
#Sta/Elev= 30
  4868.7  362.68  4878.3  362.42  4888.4  362.33  4918.4  362.27  4948.4  361.51
  4958.4  360.41  4968.5  358.85  4978.5  356.45  4985.1  355.77  4985.6  354.97
  4991.4  354.97  4991.9  355.77  4999.4  355.77  5038.5  355.84  5048.6  356.14
  5056.0  357.68  5061.0  357.71  5068.6  358.70  5078.6  359.17  5098.6  358.46
  5118.6  358.96  5148.7  359.94  5178.7  360.39  5207.3  360.04  5218.8  360.20
  5228.8  360.50  5248.8  360.52  5255.7  360.31  5288.9  360.81  5301.1  360.87
#Mann=5,-1,0
  4868.7    0.05       0  4985.1    0.07       0  4991.9    0.05       0
  4999.4     0.1       0  5207.3    0.05       0
Bank Sta=4985.1,4991.9
Exp/Cntr=0.3,0.1

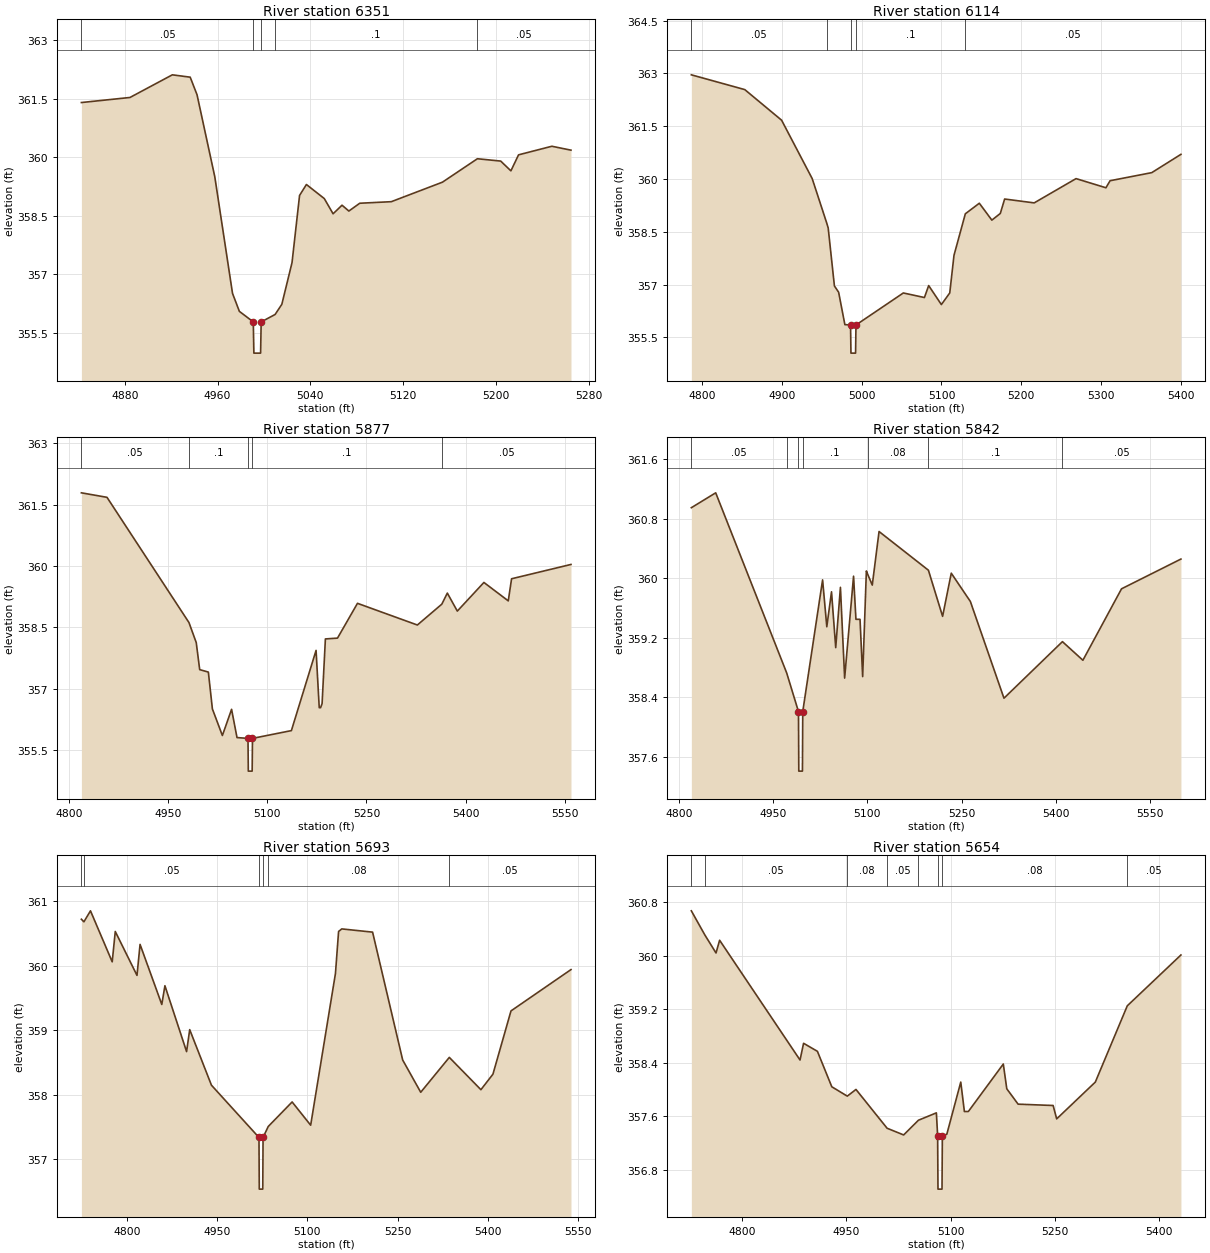
Type RM Length L Ch R = 1,6351,237,237,237
BEGIN DESCRIPTION:
Mapping XS a8c69468
END DESCRIPTION:
XS GIS Cut Line= 2
      2056329.94     13432589.09      2056106.43     13432231.03
#Sta/Elev= 30
  4842.6  361.40  4884.5  361.53  4921.0  362.11  4936.4  362.05  4942.3  361.60
  4957.6  359.50  4972.9  356.51  4978.8  356.05  4990.8  355.78  4991.3  354.98
  4997.1  354.98  4997.6  355.78  5009.6  355.97  5015.4  356.23  5024.2  357.30
  5030.7  359.02  5036.6  359.30  5052.0  358.94  5059.6  358.55  5067.3  358.77
  5073.2  358.62  5082.6  358.82  5109.8  358.86  5153.9  359.36  5184.0  359.96
  5204.1  359.90  5212.9  359.65  5219.5  360.06  5248.2  360.28  5264.7  360.18
#Mann=5,-1,0
  4842.6    0.05       0  4990.8    0.03       0  4997.6    0.05       0
  5009.6     0.1       0  5184.0    0.05       0
Bank Sta=4990.8,4997.6
Exp/Cntr=0.3,0.1

Type RM Length L Ch R = 1,6114,237,237,237
BEGIN DESCRIPTION:
Mapping XS 95935b58
END DESCRIPTION:
XS GIS Cut Line= 3
      2056512.21     13432539.12      2056447.12     13432322.15
      2056080.36     13432200.62
#Sta/Elev= 30
  4786.9  362.96  4853.8  362.54  4899.9  361.67  4938.2  360.01  4956.2  358.76
  4958.2  358.61  4966.0  356.96  4971.3  356.78  4979.1  355.86  4986.2  355.85
  4986.7  355.05  4992.5  355.05  4993.0  355.85  5052.3  356.76  5078.7  356.63
  5084.0  356.97  5099.9  356.43  5110.4  356.76  5115.7  357.83  5129.9  359.01
  5147.4  359.31  5163.1  358.83  5173.7  359.02  5179.1  359.43  5216.1  359.32
  5268.5  360.01  5305.9  359.75  5311.1  359.95  5363.3  360.18  5399.8  360.70
#Mann=5,-1,0
  4786.9    0.05       0  4956.2     0.1       0  4986.2    0.07       0
  4993.0     0.1       0  5129.9    0.05       0
Bank Sta=4986.2,4993
Exp/Cntr=0.3,0.1

Type RM Length L Ch R = 1,5877,35,35,35
BEGIN DESCRIPTION:
Mapping XS 5183c60c
END DESCRIPTION:
XS GIS Cut Line= 6
      2056629.84     13432471.80      2056678.03     13432299.91
      2056651.99     13432258.24      2056603.81     13432245.22
      2056520.47     13432250.43      2056144.15     13432210.06
#Sta/Elev= 30
  4819.1  361.79  4857.8  361.68  4981.7  358.62  4992.7  358.13  4997.9  357.47
  5011.0  357.41  5017.1  356.51  5032.2  355.86  5046.1  356.50  5054.3  355.81
  5070.9  355.79  5071.4  354.99  5077.2  354.99  5077.7  355.79  5136.5  355.98
  5173.8  357.94  5178.6  356.54  5180.6  356.54  5182.9  356.64  5187.9  358.22
  5206.2  358.24  5236.4  359.09  5326.9  358.56  5363.9  359.07  5372.2  359.34
  5387.3  358.90  5427.5  359.60  5464.3  359.15  5469.3  359.69  5559.1  360.04
#Mann=5,-1,0
  4819.1    0.05       0  4981.7     0.1       0  5070.9    0.07       0
  5077.7     0.1       0  5363.9    0.05       0
Bank Sta=5070.9,5077.7
Exp/Cntr=0.3,0.1

Type RM Length L Ch R = 1,5842,149,149,149
BEGIN DESCRIPTION:
Mapping XS dd7404ba
END DESCRIPTION:
XS GIS Cut Line= 6
      2056671.51     13432465.31      2056709.28     13432284.28
      2056655.89     13432224.39      2056624.64     13432204.86
      2056507.45     13432225.69      2056150.68     13432198.35
#Sta/Elev= 30
  4819.7  360.95  4858.5  361.15  4971.5  358.73  4990.3  358.21  4990.8  357.41
  4996.6  357.41  4997.1  358.21  5028.7  359.98  5035.4  359.35  5042.9  359.82
  5049.6  359.07  5057.1  359.88  5063.8  358.66  5078.0  360.03  5081.8  359.45
  5088.3  359.45  5092.5  358.68  5098.4  360.10  5100.3  360.06  5107.8  359.91
  5118.6  360.63  5197.2  360.11  5219.8  359.49  5233.6  360.07  5264.0  359.69
  5317.5  358.39  5410.6  359.15  5443.2  358.90  5504.7  359.86  5599.3  360.26
#Mann=7,-1,0
  4819.7    0.05       0  4971.5     0.1       0  4990.3    0.07       0
  4997.1     0.1       0  5100.3    0.08       0  5197.2     0.1       0
  5410.6    0.05       0
Bank Sta=4990.3,4997.1
Exp/Cntr=0.3,0.1

Type RM Length L Ch R = 1,5693,39,39,39
BEGIN DESCRIPTION:
Mapping XS ba96f163
END DESCRIPTION:
XS GIS Cut Line= 3
      2057034.76     13432086.38      2056576.46     13432200.95
      2056235.28     13432198.35
#Sta/Elev= 30
  4724.4  360.72  4728.6  360.68  4739.5  360.85  4775.6  360.06  4780.7  360.53
  4816.8  359.85  4821.9  360.33  4858.0  359.40  4863.2  359.69  4899.2  358.67
  4904.4  359.01  4940.5  358.15  5019.5  357.34  5020.0  356.54  5025.8  356.54
  5026.3  357.34  5034.9  357.51  5074.6  357.89  5105.4  357.53  5146.6  359.88
  5151.8  360.53  5157.1  360.57  5208.3  360.52  5258.3  358.54  5288.3  358.04
  5335.8  358.58  5388.3  358.08  5408.3  358.32  5438.3  359.30  5538.0  359.94
#Mann=6,-1,0
  4724.4    0.08       0  4728.6    0.05       0  5019.5    0.03       0
  5026.3    0.05       0  5034.9    0.08       0  5335.8    0.05       0
Bank Sta=5019.5,5026.3
Exp/Cntr=0.3,0.1

Type RM Length L Ch R = 1,5654,131,131,131
BEGIN DESCRIPTION:
Mapping XS d0c413c9
END DESCRIPTION:
XS GIS Cut Line= 3
      2057050.42     13432049.91      2056625.94     13432161.89
      2056362.96     13432125.43
#Sta/Elev= 30
  4727.0  360.67  4746.4  360.31  4762.5  360.04  4767.7  360.23  4883.4  358.44
  4888.5  358.69  4908.4  358.57  4929.1  358.04  4951.4  357.90  4963.9  358.00
  5008.7  357.42  5032.5  357.32  5053.8  357.54  5079.6  357.65  5081.4  357.31
  5081.9  356.51  5087.7  356.51  5088.2  357.31  5094.6  357.33  5114.7  358.11
  5119.9  357.67  5125.6  357.67  5175.9  358.38  5180.9  358.01  5197.2  357.78
  5247.6  357.76  5252.7  357.56  5308.3  358.11  5354.3  359.25  5431.5  360.01
#Mann=8,-1,0
  4727.0    0.08       0  4746.4    0.05       0  4951.4    0.08       0
  5008.7    0.05       0  5053.8    0.08       0  5081.4    0.07       0
  5088.2    0.08       0  5354.3    0.05       0
Bank Sta=5081.4,5088.2
Exp/Cntr=0.3,0.1