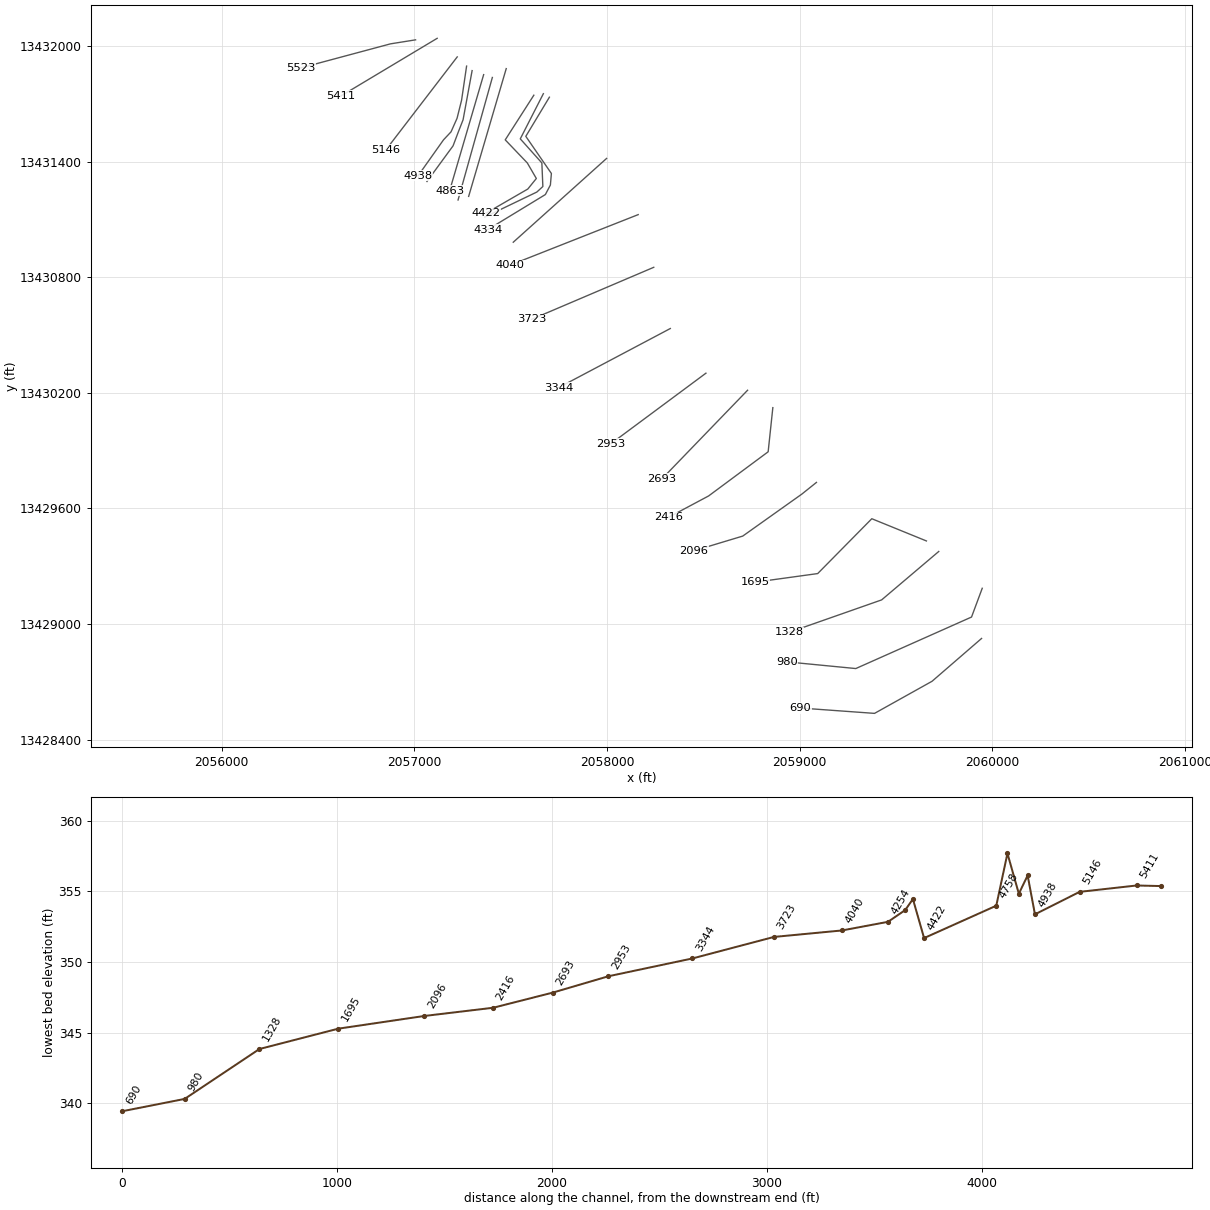
HEC-RAS study UNT 062 in RCW.prj: UNT 062 in RCW Base Level Engineering

--- UNT 062 in RCW.g01 (geometry) --- (continued)

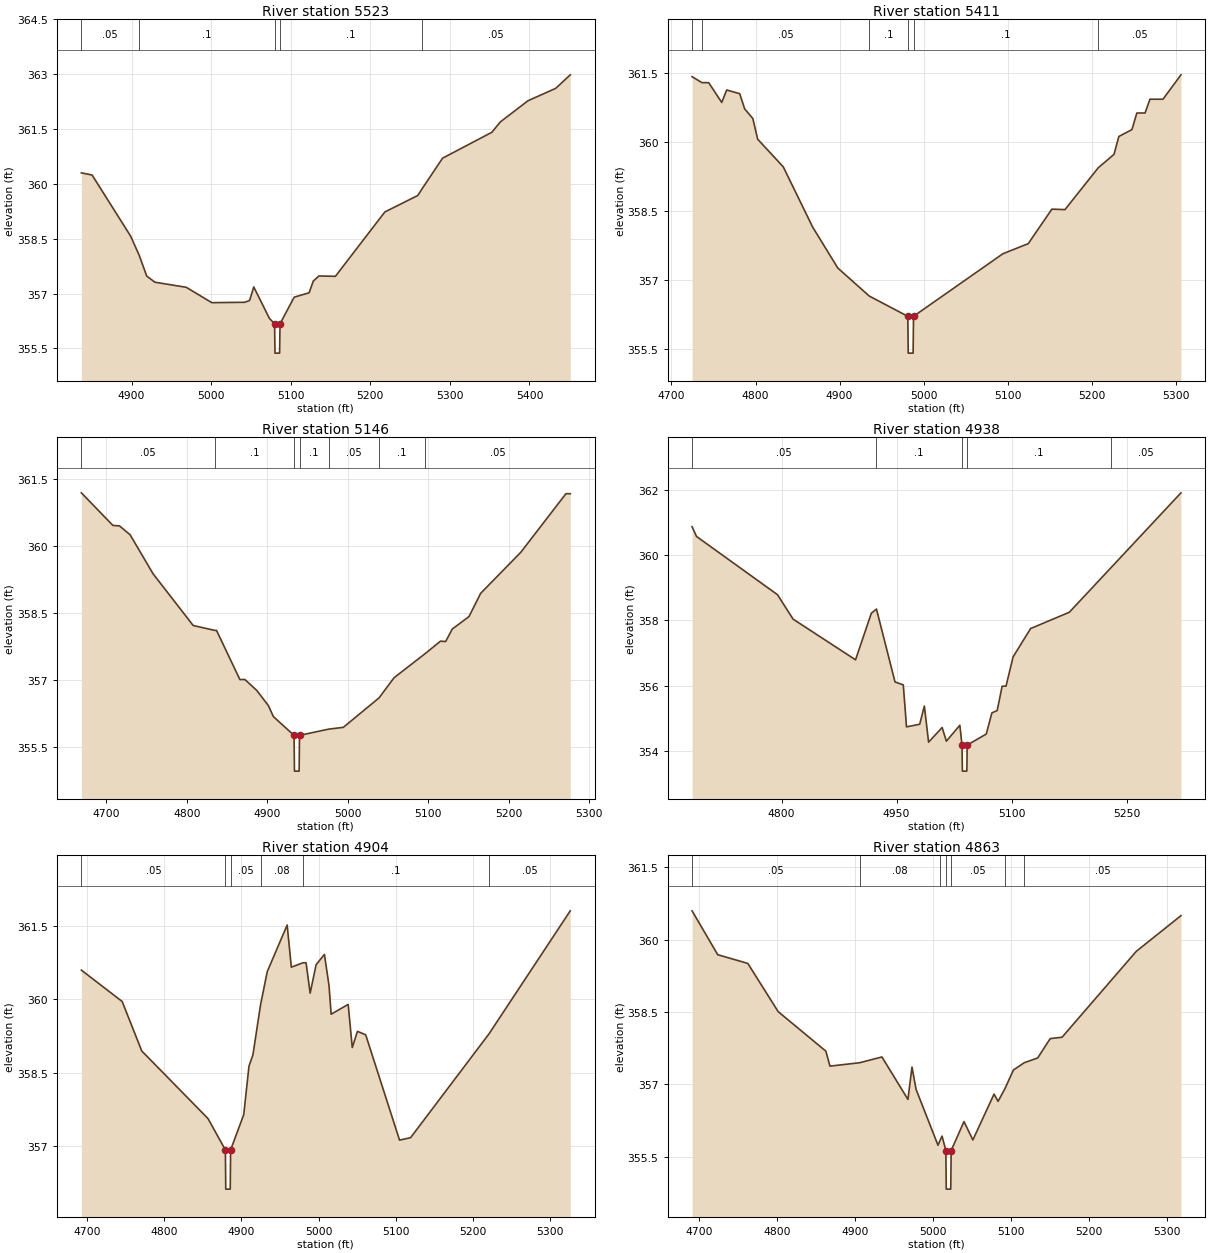
Type RM Length L Ch R = 1,5523,112,112,112
BEGIN DESCRIPTION:
Mapping XS ec228c9f
END DESCRIPTION:
XS GIS Cut Line= 3
      2057006.11     13432031.67      2056875.94     13432010.85
      2056409.93     13431885.88
#Sta/Elev= 30
  4837.0  360.30  4850.5  360.24  4898.9  358.57  4909.6  358.05  4919.1  357.48
  4929.3  357.31  4968.8  357.17  5000.9  356.75  5042.3  356.76  5048.4  356.81
  5053.6  357.18  5073.3  356.32  5079.8  356.17  5080.3  355.37  5086.1  355.37
  5086.6  356.17  5104.4  356.90  5123.2  357.02  5128.4  357.34  5135.5  357.48
  5156.2  357.47  5218.3  359.23  5259.7  359.68  5264.4  359.84  5290.8  360.70
  5352.9  361.41  5363.3  361.69  5398.1  362.27  5433.0  362.61  5451.3  362.98
#Mann=5,-1,0
  4837.0    0.05       0  4909.6     0.1       0  5079.8    0.07       0
  5086.6     0.1       0  5264.4    0.05       0
Bank Sta=5079.8,5086.6
Exp/Cntr=0.3,0.1

Type RM Length L Ch R = 1,5411,265,265,265
BEGIN DESCRIPTION:
Mapping XS ae86be4e
END DESCRIPTION:
XS GIS Cut Line= 2
      2057118.11     13432039.48      2056619.08     13431740.58
#Sta/Elev= 30
  4724.5  361.42  4736.3  361.29  4744.3  361.29  4759.8  360.86  4765.7  361.13
  4781.2  361.05  4787.1  360.72  4796.8  360.51  4802.6  360.06  4833.0  359.46
  4868.0  358.15  4897.9  357.26  4935.4  356.65  4981.2  356.21  4981.7  355.41
  4987.5  355.41  4988.0  356.21  5094.3  357.57  5124.5  357.79  5152.6  358.54
  5168.2  358.53  5207.8  359.44  5226.5  359.73  5232.3  360.12  5247.9  360.27
  5253.7  360.63  5263.5  360.63  5269.3  360.93  5284.8  360.93  5306.2  361.46
#Mann=6,-1,0
  4724.5    0.08       0  4736.3    0.05       0  4935.4     0.1       0
  4981.2    0.07       0  4988.0     0.1       0  5207.8    0.05       0
Bank Sta=4981.2,4988
Exp/Cntr=0.3,0.1

Type RM Length L Ch R = 1,5146,208,208,208
BEGIN DESCRIPTION:
Mapping XS 7ae07292
END DESCRIPTION:
XS GIS Cut Line= 2
      2057222.28     13431943.11      2056852.50     13431461.36
#Sta/Elev= 30
  4668.9  361.19  4708.1  360.46  4716.3  360.45  4729.5  360.25  4757.9  359.38
  4807.8  358.22  4834.8  358.11  4836.8  358.11  4865.8  357.01  4872.1  357.01
  4886.6  356.77  4901.1  356.43  4907.5  356.18  4933.1  355.76  4933.6  354.96
  4939.4  354.96  4939.9  355.76  4976.1  355.90  4994.3  355.94  5038.7  356.60
  5057.3  357.05  5095.9  357.59  5115.1  357.87  5121.4  357.86  5129.6  358.14
  5150.4  358.42  5164.9  358.94  5214.8  359.86  5270.8  361.17  5276.2  361.17
#Mann=7,-1,0
  4668.9    0.05       0  4834.8     0.1       0  4933.1   0.033       0
  4939.9     0.1       0  4976.1    0.05       0  5038.7     0.1       0
  5095.9    0.05       0
Bank Sta=4933.1,4939.9
Exp/Cntr=0.3,0.1

Type RM Length L Ch R = 1,4938,34,34,34
BEGIN DESCRIPTION:
Mapping XS ed190f7d
END DESCRIPTION:
XS GIS Cut Line= 6
      2057270.90     13431895.35      2057244.87     13431718.31
      2057221.43     13431624.56      2057190.18     13431554.25
      2057151.12     13431512.58      2057019.18     13431326.32
#Sta/Elev= 30
  4683.1  360.88  4688.9  360.58  4794.6  358.79  4814.9  358.04  4896.4  356.79
  4917.0  358.22  4923.7  358.35  4947.9  356.11  4958.7  356.02  4962.9  354.73
  4980.1  354.81  4986.2  355.37  4991.7  354.26  5009.4  354.71  5014.9  354.29
  5032.5  354.78  5035.3  354.17  5035.8  353.37  5041.6  353.37  5042.1  354.17
  5067.0  354.51  5074.3  355.16  5081.2  355.23  5087.7  355.98  5092.7  355.98
  5102.0  356.88  5124.8  357.75  5175.3  358.25  5229.7  359.62  5321.0  361.92
#Mann=5,-1,0
  4683.1    0.05       0  4923.7     0.1       0  5035.3    0.07       0
  5042.1     0.1       0  5229.7    0.05       0
Bank Sta=5035.3,5042.1
Exp/Cntr=0.3,0.1

Type RM Length L Ch R = 1,4904,41,41,41
BEGIN DESCRIPTION:
Mapping XS ef023e88
END DESCRIPTION:
XS GIS Cut Line= 5
      2057299.56     13431872.00      2057252.68     13431616.75
      2057229.24     13431556.85      2057200.60     13431481.33
      2057065.17     13431296.43
#Sta/Elev= 30
  4692.5  360.59  4745.4  359.95  4770.8  358.94  4856.7  357.56  4879.2  356.92
  4879.7  356.12  4885.5  356.12  4886.0  356.92  4903.0  357.64  4909.8  358.63
  4914.9  358.86  4924.9  359.89  4933.5  360.56  4959.3  361.51  4964.7  360.65
  4979.8  360.74  4983.8  360.74  4989.1  360.12  4996.8  360.70  5007.6  360.91
  5013.6  360.27  5016.3  359.69  5038.4  359.89  5043.7  359.01  5050.4  359.34
  5061.1  359.27  5105.0  357.12  5119.3  357.17  5221.0  359.29  5326.3  361.80
#Mann=6,-1,0
  4692.5    0.05       0  4879.2    0.07       0  4886.0    0.05       0
  4924.9    0.08       0  4979.8     0.1       0  5221.0    0.05       0
Bank Sta=4879.2,4886
Exp/Cntr=0.3,0.1

Type RM Length L Ch R = 1,4863,53,53,53
BEGIN DESCRIPTION:
Mapping XS 7fcff258
END DESCRIPTION:
XS GIS Cut Line= 2
      2057359.45     13431851.12      2057182.81     13431248.47
#Sta/Elev= 30
  4690.5  360.60  4723.5  359.69  4762.1  359.51  4801.1  358.51  4862.4  357.69
  4867.6  357.38  4905.6  357.45  4934.4  357.57  4967.8  356.69  4973.0  357.36
  4978.2  356.90  5006.4  355.74  5009.3  355.85  5011.6  355.93  5016.5  355.63
  5017.0  354.83  5022.8  354.83  5023.3  355.63  5039.8  356.23  5051.2  355.85
  5078.4  356.80  5083.6  356.65  5092.3  356.91  5103.3  357.30  5117.1  357.45
  5134.5  357.55  5150.5  357.95  5165.8  357.98  5261.1  359.76  5318.5  360.50
#Mann=7,-1,0
  4690.5    0.05       0  4905.6    0.08       0  5009.3    0.05       0
  5016.5    0.07       0  5023.3    0.05       0  5092.3     0.1       0
  5117.1    0.05       0
Bank Sta=5016.5,5023.3
Exp/Cntr=0.3,0.1

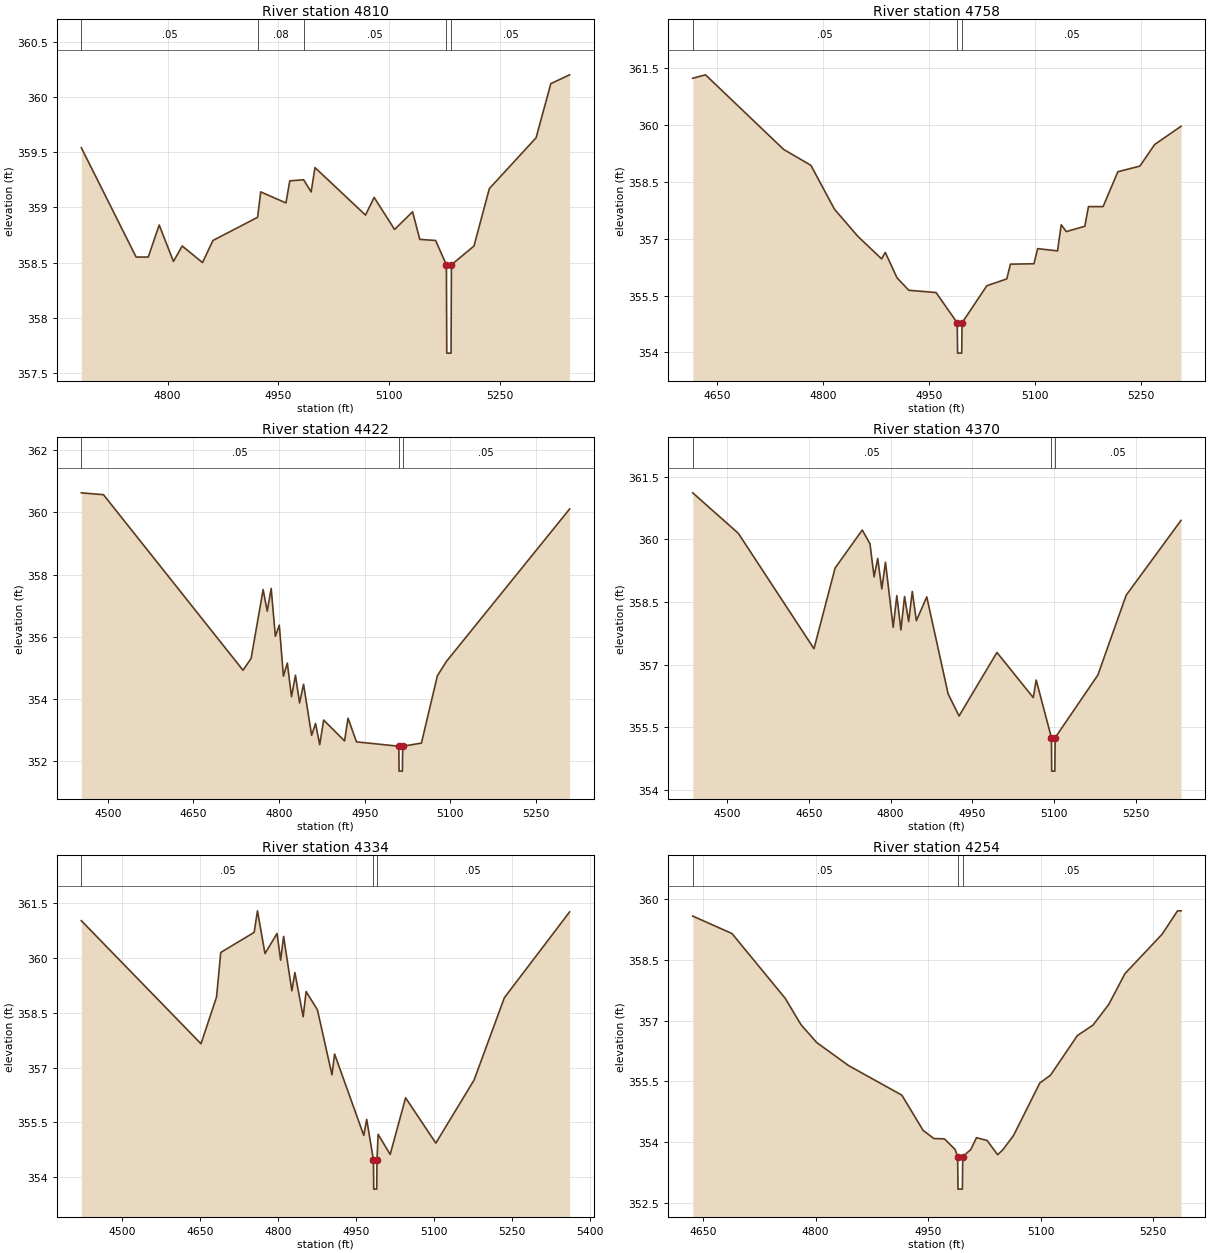
Type RM Length L Ch R = 1,4810,52,52,52
BEGIN DESCRIPTION:
Mapping XS 7f06c647
END DESCRIPTION:
XS GIS Cut Line= 2
      2057404.60     13431836.38      2057226.64     13431200.51
#Sta/Elev= 30
  4683.4  359.54  4757.5  358.55  4773.9  358.55  4788.7  358.84  4808.0  358.51
  4819.8  358.65  4847.3  358.50  4861.4  358.70  4921.8  358.91  4926.0  359.14
  4960.1  359.04  4965.3  359.24  4984.0  359.25  4994.2  359.14  4999.4  359.36
  5067.7  358.93  5079.4  359.09  5107.0  358.80  5131.4  358.96  5141.1  358.71
  5162.5  358.70  5177.1  358.48  5177.6  357.68  5183.4  357.68  5183.9  358.48
  5214.4  358.65  5235.2  359.17  5298.4  359.63  5318.3  360.12  5343.7  360.20
#Mann=5,-1,0
  4683.4    0.05       0  4921.8    0.08       0  4984.0    0.05       0
  5177.1    0.04       0  5183.9    0.05       0
Bank Sta=5177.1,5183.9
Exp/Cntr=0.3,0.1

Type RM Length L Ch R = 1,4758,336,336,336
BEGIN DESCRIPTION:
Mapping XS b4919b44
END DESCRIPTION:
XS GIS Cut Line= 2
      2057476.65     13431882.41      2057281.59     13431219.20
#Sta/Elev= 30
  4615.7  361.24  4633.8  361.33  4744.4  359.36  4783.0  358.94  4816.4  357.78
  4849.7  357.06  4883.1  356.47  4888.3  356.64  4904.9  355.97  4921.6  355.64
  4960.2  355.58  4990.2  354.78  4990.7  353.98  4996.5  353.98  4997.0  354.78
  5032.1  355.76  5060.3  355.94  5065.5  356.33  5098.8  356.34  5104.1  356.74
  5132.2  356.68  5137.4  357.37  5144.6  357.19  5170.8  357.33  5176.0  357.85
  5196.7  357.85  5217.6  358.77  5248.8  358.92  5269.7  359.49  5307.0  359.97
#Mann=3,-1,0
  4615.7    0.05       0  4990.2    0.03       0  4997.0    0.05       0
Bank Sta=4990.2,4997
Exp/Cntr=0.3,0.1

Type RM Length L Ch R = 1,4422,52,52,52
BEGIN DESCRIPTION:
Mapping XS 2a56d5f9
END DESCRIPTION:
XS GIS Cut Line= 6
      2057619.84     13431744.31      2057471.43     13431512.58
      2057586.01     13431392.79      2057632.89     13431312.06
      2057588.62     13431257.37      2057372.43     13431132.35
#Sta/Elev= 30
  4453.6  360.63  4492.4  360.57  4736.8  354.93  4750.9  355.31  4772.0  357.52
  4779.2  356.83  4786.1  357.56  4793.4  356.02  4800.3  356.38  4807.5  354.74
  4814.4  355.16  4821.7  354.08  4828.6  354.77  4835.8  353.88  4842.8  354.48
  4856.9  352.84  4863.8  353.22  4871.1  352.54  4878.0  353.33  4914.6  352.66
  4920.7  353.39  4935.5  352.63  5009.6  352.49  5010.1  351.69  5015.9  351.69
  5016.4  352.49  5049.2  352.59  5077.1  354.75  5092.8  355.21  5308.7  360.11
#Mann=3,-1,0
  4453.6    0.05       0  5009.6    0.03       0  5016.4    0.05       0
Bank Sta=5009.6,5016.4
Exp/Cntr=0.3,0.1

Type RM Length L Ch R = 1,4370,36,36,36
BEGIN DESCRIPTION:
Mapping XS 1a80623d
END DESCRIPTION:
XS GIS Cut Line= 6
      2057669.35     13431752.17      2057549.55     13431517.79
      2057661.53     13431392.79      2057666.74     13431270.40
      2057635.49     13431241.75      2057364.68     13431111.55
#Sta/Elev= 30
  4436.4  361.11  4520.2  360.14  4659.1  357.38  4697.9  359.31  4747.8  360.22
  4762.0  359.89  4769.5  359.10  4776.2  359.54  4783.7  358.81  4790.4  359.45
  4804.6  357.89  4811.3  358.65  4818.8  357.83  4825.5  358.63  4833.0  358.03
  4839.7  358.75  4847.2  358.05  4866.3  358.62  4905.5  356.30  4925.6  355.77
  4995.2  357.29  5061.9  356.21  5067.3  356.63  5095.3  355.25  5095.8  354.45
  5101.6  354.45  5102.1  355.25  5180.6  356.75  5232.6  358.66  5333.3  360.45
#Mann=3,-1,0
  4436.4    0.05       0  5095.3    0.03       0  5102.1    0.05       0
Bank Sta=5095.3,5102.1
Exp/Cntr=0.3,0.1

Type RM Length L Ch R = 1,4334,80,80,80
BEGIN DESCRIPTION:
Mapping XS ac45bd7c
END DESCRIPTION:
XS GIS Cut Line= 6
      2057700.60     13431733.94      2057578.20     13431530.81
      2057711.01     13431338.10      2057705.80     13431278.21
      2057679.76     13431228.73      2057380.28     13431046.43
#Sta/Elev= 30
  4422.0  361.02  4652.0  357.65  4681.9  358.93  4690.0  360.15  4754.2  360.70
  4760.6  361.29  4775.0  360.12  4798.2  360.67  4805.1  359.94  4810.8  360.59
  4826.7  359.10  4832.5  359.60  4848.4  358.39  4854.1  359.08  4875.8  358.58
  4903.8  356.80  4908.8  357.37  4964.9  355.14  4970.5  355.58  4983.5  354.47
  4984.0  353.67  4989.8  353.67  4990.3  354.47  4992.5  355.17  5015.6  354.62
  5045.3  356.17  5103.4  354.93  5177.0  356.66  5235.1  358.91  5360.5  361.26
#Mann=3,-1,0
  4422.0    0.05       0  4983.5    0.03       0  4990.3    0.05       0
Bank Sta=4983.5,4990.3
Exp/Cntr=0.3,0.1

Type RM Length L Ch R = 1,4254,214,214,214
BEGIN DESCRIPTION:
Mapping XS 33962e0c
END DESCRIPTION:
XS GIS Cut Line= 2
      2057997.50     13431416.25      2057513.10     13430981.33
#Sta/Elev= 30
  4636.1  359.58  4688.4  359.15  4759.4  357.55  4780.4  356.90  4801.3  356.46
  4843.9  355.89  4914.9  355.16  4943.3  354.29  4957.5  354.09  4971.7  354.08
  4985.9  353.82  4989.3  353.64  4989.8  352.84  4995.6  352.84  4996.1  353.64
  5006.9  353.82  5014.4  354.11  5028.6  354.04  5042.6  353.69  5049.5  353.81
  5063.7  354.16  5098.8  355.46  5113.0  355.65  5148.9  356.63  5169.8  356.89
  5190.8  357.40  5212.4  358.16  5261.8  359.13  5282.5  359.71  5287.1  359.71
#Mann=3,-1,0
  4636.1    0.05       0  4989.3    0.03       0  4996.1    0.05       0
Bank Sta=4989.3,4996.1
Exp/Cntr=0.3,0.1

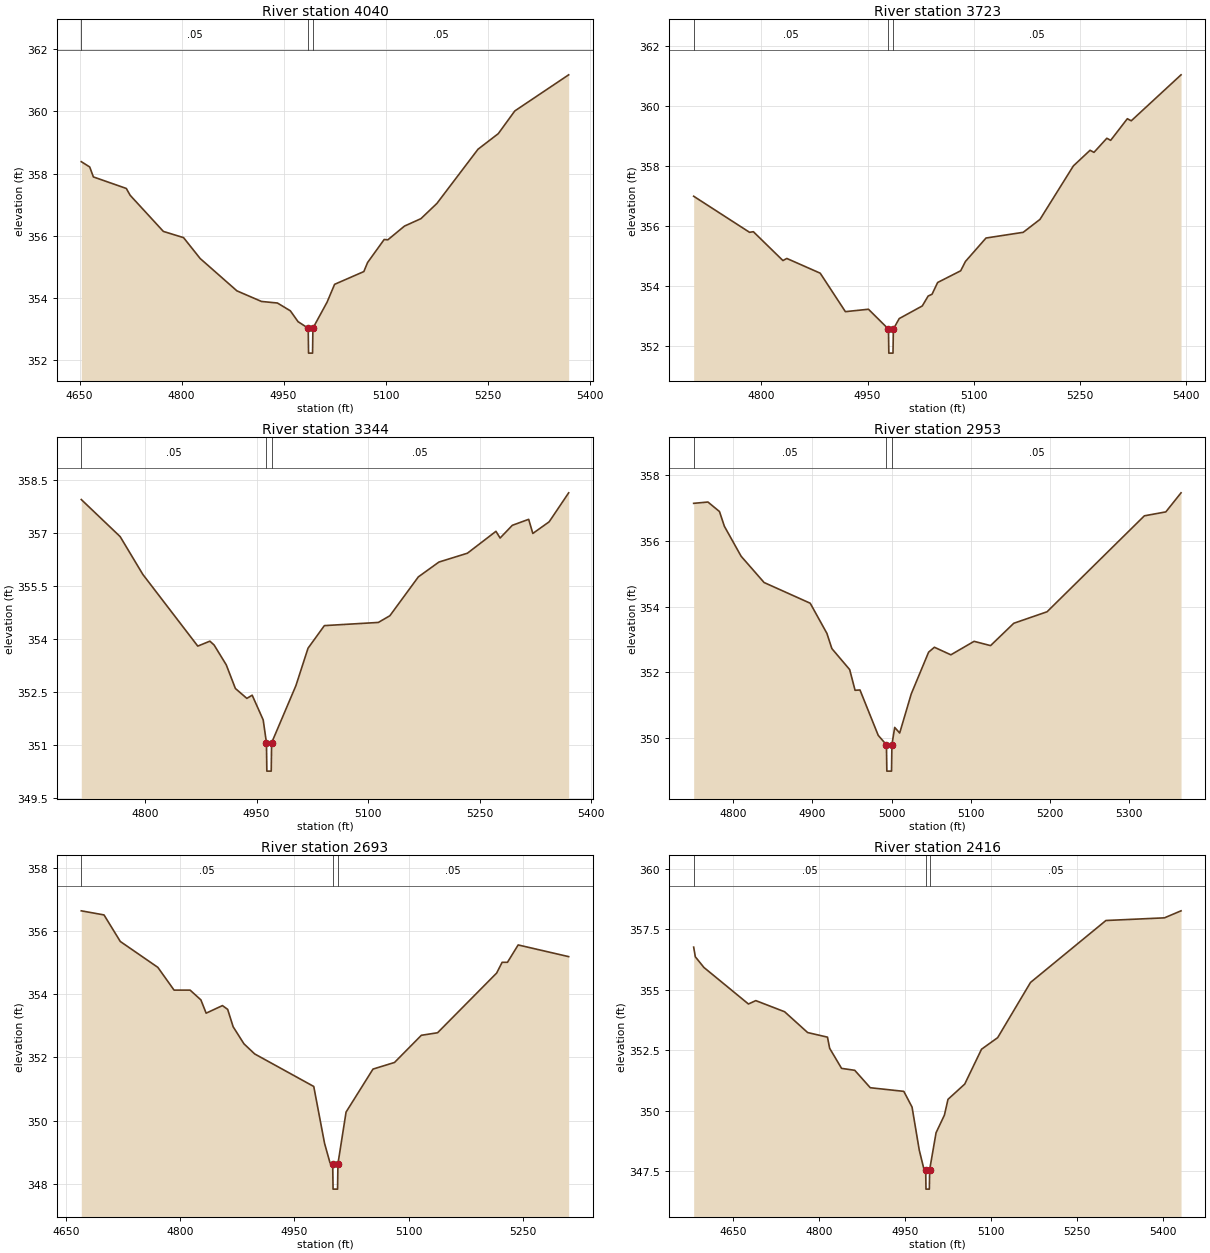
Type RM Length L Ch R = 1,4040,317,317,317
BEGIN DESCRIPTION:
Mapping XS 9aa16845
END DESCRIPTION:
XS GIS Cut Line= 2
      2058161.55     13431124.57      2057494.86     13430861.54
#Sta/Elev= 30
  4652.5  358.38  4664.9  358.21  4670.3  357.89  4718.7  357.52  4724.4  357.30
  4773.2  356.14  4802.9  355.94  4827.3  355.27  4881.4  354.23  4917.5  353.89
  4940.9  353.84  4959.9  353.59  4971.3  353.24  4986.2  353.03  4986.7  352.23
  4992.6  352.23  4993.1  353.03  5014.0  353.87  5025.0  354.44  5068.0  354.85
  5073.5  355.14  5097.9  355.88  5103.3  355.87  5127.7  356.31  5152.0  356.55
  5175.5  357.04  5235.9  358.78  5265.7  359.28  5290.0  360.01  5369.2  361.17
#Mann=3,-1,0
  4652.5    0.05       0  4986.2    0.03       0  4993.1    0.05       0
Bank Sta=4986.2,4993.1
Exp/Cntr=0.3,0.1

Type RM Length L Ch R = 1,3723,379,379,379
BEGIN DESCRIPTION:
Mapping XS af952ec8
END DESCRIPTION:
XS GIS Cut Line= 2
      2058242.29     13430851.14      2057608.47     13430580.98
#Sta/Elev= 30
  4704.2  356.99  4783.2  355.79  4788.6  355.81  4830.4  354.85  4835.9  354.92
  4883.1  354.43  4918.7  353.15  4951.3  353.23  4979.6  352.57  4980.1  351.77
  4986.0  351.77  4986.5  352.57  4994.8  352.92  5027.4  353.34  5035.7  353.67
  5041.2  353.73  5049.1  354.12  5081.7  354.51  5088.4  354.82  5117.5  355.60
  5170.1  355.79  5193.8  356.22  5241.0  358.00  5264.6  358.52  5270.1  358.45
  5288.3  358.92  5293.7  358.85  5317.3  359.57  5322.8  359.50  5393.2  361.03
#Mann=3,-1,0
  4704.2    0.05       0  4979.6    0.03       0  4986.5    0.05       0
Bank Sta=4979.6,4986.5
Exp/Cntr=0.3,0.1

Type RM Length L Ch R = 1,3344,391,391,391
BEGIN DESCRIPTION:
Mapping XS f787d803
END DESCRIPTION:
XS GIS Cut Line= 2
      2058328.20     13430533.42      2057748.73     13430226.79
#Sta/Elev= 30
  4714.2  357.94  4766.5  356.89  4797.0  355.82  4870.9  353.79  4887.2  353.93
  4892.9  353.82  4909.2  353.26  4921.5  352.59  4936.9  352.31  4944.1  352.40
  4958.9  351.70  4963.3  351.05  4963.8  350.25  4969.7  350.25  4970.2  351.05
  5002.9  352.67  5019.2  353.73  5041.2  354.37  5113.8  354.46  5129.3  354.65
  5167.6  355.75  5195.3  356.17  5233.6  356.42  5272.0  357.04  5277.6  356.85
  5294.0  357.21  5316.0  357.38  5321.6  356.98  5343.6  357.31  5369.8  358.13
#Mann=3,-1,0
  4714.2    0.05       0  4963.3    0.03       0  4970.2    0.05       0
Bank Sta=4963.3,4970.2
Exp/Cntr=0.3,0.1

Type RM Length L Ch R = 1,2953,260,260,260
BEGIN DESCRIPTION:
Mapping XS dde47640
END DESCRIPTION:
XS GIS Cut Line= 2
      2058513.13     13430301.67      2058019.18     13429935.11
#Sta/Elev= 30
  4750.2  357.14  4768.2  357.18  4782.8  356.89  4789.0  356.44  4810.1  355.53
  4839.1  354.73  4897.3  354.10  4918.4  353.18  4924.6  352.72  4947.1  352.08
  4953.9  351.45  4960.1  351.46  4983.1  350.08  4993.5  349.79  4994.0  348.99
  4999.9  348.99  5000.4  349.79  5003.9  350.32  5010.2  350.15  5024.8  351.34
  5046.7  352.61  5054.0  352.76  5074.8  352.53  5104.1  352.94  5124.9  352.81
  5154.2  353.49  5196.2  353.84  5319.0  356.76  5346.1  356.88  5365.3  357.46
#Mann=3,-1,0
  4750.2    0.05       0  4993.5    0.03       0  5000.4    0.05       0
Bank Sta=4993.5,5000.4
Exp/Cntr=0.3,0.1

Type RM Length L Ch R = 1,2693,277,277,277
BEGIN DESCRIPTION:
Mapping XS 18e9ab06
END DESCRIPTION:
XS GIS Cut Line= 2
      2058729.26     13430213.12      2058283.95     13429752.19
#Sta/Elev= 30
  4669.7  356.64  4699.6  356.51  4721.0  355.67  4770.4  354.85  4791.7  354.13
  4812.8  354.13  4827.0  353.82  4833.9  353.40  4855.3  353.64  4862.2  353.52
  4869.4  352.97  4883.6  352.43  4897.7  352.11  4975.4  351.08  4989.6  349.28
  4996.8  348.66  5000.3  348.63  5000.8  347.83  5006.7  347.83  5007.2  348.63
  5017.9  350.27  5053.3  351.63  5081.6  351.84  5116.9  352.70  5138.2  352.78
  5215.9  354.67  5223.1  355.01  5230.1  355.01  5244.2  355.56  5310.6  355.19
#Mann=3,-1,0
  4669.7    0.05       0  5000.3    0.03       0  5007.2    0.05       0
Bank Sta=5000.3,5007.2
Exp/Cntr=0.3,0.1

Type RM Length L Ch R = 1,2416,320,320,320
BEGIN DESCRIPTION:
Mapping XS 8ac7dd38
END DESCRIPTION:
XS GIS Cut Line= 4
      2058860.32     13430122.81      2058836.01     13429893.66
      2058526.99     13429664.49      2058319.34     13429553.75
#Sta/Elev= 30
  4580.6  356.76  4583.5  356.36  4598.5  355.92  4676.2  354.41  4689.0  354.55
  4739.3  354.09  4779.5  353.23  4814.1  353.04  4817.9  352.58  4838.7  351.75
  4861.7  351.67  4888.8  350.95  4947.3  350.80  4961.7  350.15  4974.3  348.37
  4982.7  347.56  4985.5  347.56  4986.0  346.76  4991.9  346.76  4992.4  347.56
  5003.6  349.09  5018.2  349.82  5024.4  350.47  5053.6  351.10  5082.9  352.54
  5111.1  353.02  5168.4  355.30  5300.0  357.86  5402.1  357.97  5431.1  358.26
#Mann=3,-1,0
  4580.6    0.05       0  4985.5    0.03       0  4992.4    0.05       0
Bank Sta=4985.5,4992.4
Exp/Cntr=0.3,0.1

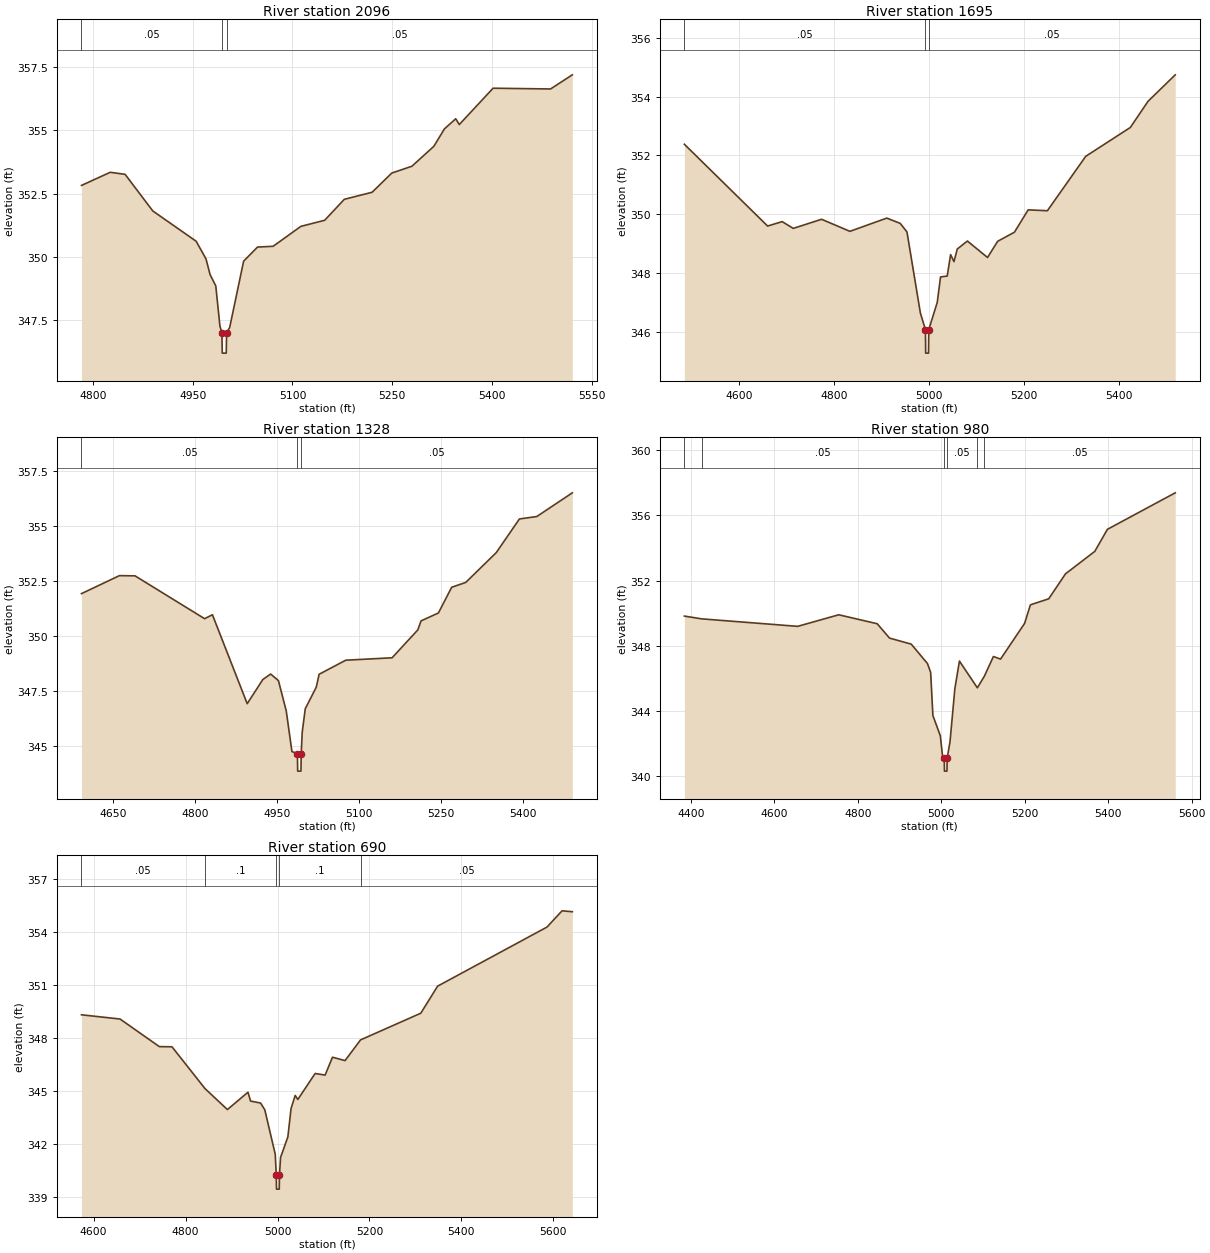
Type RM Length L Ch R = 1,2096,401,401,401
BEGIN DESCRIPTION:
Mapping XS 7deabee5
END DESCRIPTION:
XS GIS Cut Line= 4
      2059086.60     13429734.69      2059010.68     13429673.96
      2058704.07     13429456.16      2058450.93     13429379.87
#Sta/Elev= 30
  4782.9  352.82  4826.1  353.34  4848.5  353.26  4890.1  351.81  4955.3  350.61
  4970.1  349.91  4976.2  349.29  4984.8  348.84  4991.0  347.25  4994.0  346.98
  4994.5  346.18  5000.5  346.18  5001.0  346.98  5005.7  347.20  5026.6  349.82
  5047.5  350.38  5070.9  350.41  5112.7  351.20  5148.4  351.44  5177.9  352.27
  5219.7  352.55  5249.3  353.31  5279.5  353.58  5312.5  354.37  5328.4  355.06
  5345.4  355.46  5350.7  355.23  5401.5  356.67  5487.9  356.64  5520.6  357.20
#Mann=3,-1,0
  4782.9    0.05       0  4994.0    0.03       0  5001.0    0.05       0
Bank Sta=4994,5001
Exp/Cntr=0.3,0.1

Type RM Length L Ch R = 1,1695,367,367,367
BEGIN DESCRIPTION:
Mapping XS 03fcb755
END DESCRIPTION:
XS GIS Cut Line= 4
      2059657.37     13429430.91      2059373.97     13429546.26
      2059093.14     13429261.63      2058768.24     13429216.81
#Sta/Elev= 30
  4484.0  352.38  4659.3  349.60  4690.0  349.75  4713.3  349.52  4773.0  349.83
  4832.6  349.42  4910.3  349.87  4938.6  349.69  4952.8  349.40  4981.1  346.64
  4991.7  346.08  4992.2  345.28  4998.2  345.28  4998.7  346.08  5016.5  347.00
  5023.5  347.87  5037.6  347.90  5044.7  348.63  5051.8  348.39  5058.8  348.82
  5080.1  349.09  5122.5  348.53  5143.7  349.08  5179.1  349.39  5208.1  350.15
  5248.5  350.12  5329.3  351.97  5423.2  352.95  5460.5  353.84  5517.8  354.74
#Mann=3,-1,0
  4484.0    0.05       0  4991.7    0.03       0  4998.7    0.05       0
Bank Sta=4991.7,4998.7
Exp/Cntr=0.3,0.1

Type RM Length L Ch R = 1,1328,348,348,348
BEGIN DESCRIPTION:
UNT 062 in RCW 3.0
END DESCRIPTION:
XS GIS Cut Line= 3
      2059721.46     13429376.32      2059425.00     13429125.00
      2058943.61     13428956.14
#Sta/Elev= 30
  4592.0  351.92  4661.5  352.74  4690.1  352.73  4817.5  350.78  4831.8  350.96
  4895.5  346.91  4924.1  348.01  4938.4  348.26  4952.7  347.96  4967.0  346.58
  4977.4  344.73  4987.4  344.64  4987.9  343.84  4993.9  343.84  4994.4  344.64
  4996.2  345.61  5001.8  346.68  5021.9  347.66  5027.2  348.25  5076.0  348.89
  5160.8  349.00  5207.9  350.27  5213.8  350.68  5245.6  351.04  5269.9  352.21
  5295.6  352.43  5351.6  353.79  5393.9  355.32  5425.7  355.43  5490.8  356.51
#Mann=3,-1,0
  4592.0    0.05       0  4987.4    0.03       0  4994.4    0.05       0
Bank Sta=4987.4,4994.4
Exp/Cntr=0.3,0.1

Type RM Length L Ch R = 1,980,290,290,290
BEGIN DESCRIPTION:
Mapping XS 0341502f
END DESCRIPTION:
XS GIS Cut Line= 4
      2059947.13     13429185.34      2059891.57     13429036.02
      2059290.87     13428768.66      2058933.19     13428803.39
#Sta/Elev= 30
  4384.5  349.82  4425.8  349.65  4656.0  349.19  4754.4  349.90  4846.6  349.35
  4876.1  348.47  4928.1  348.10  4967.0  346.91  4974.6  346.37  4980.0  343.72
  4997.8  342.48  5003.3  341.19  5007.2  341.11  5007.7  340.31  5013.7  340.31
  5014.2  341.11  5021.0  342.11  5032.6  345.36  5043.6  347.06  5086.5  345.42
  5103.1  346.12  5125.0  347.34  5142.1  347.18  5199.7  349.37  5213.7  350.51
  5257.5  350.88  5297.7  352.41  5368.0  353.79  5398.1  355.14  5560.7  357.38
#Mann=6,-1,0
  4384.5     0.1       0  4425.8    0.05       0  5007.2    0.03       0
  5014.2    0.05       0  5086.5     0.1       0  5103.1    0.05       0
Bank Sta=5007.2,5014.2
Exp/Cntr=0.3,0.1

Type RM Length L Ch R = 1,690,350,350,350
BEGIN DESCRIPTION:
Mapping XS 62f1d30d
END DESCRIPTION:
XS GIS Cut Line= 4
      2059943.62     13428924.88      2059686.71     13428702.69
      2059388.10     13428536.02      2059002.64     13428563.80
#Sta/Elev= 30
  4573.4  349.30  4657.4  349.06  4742.9  347.50  4770.4  347.49  4842.1  345.13
  4891.0  343.94  4935.7  344.92  4941.4  344.42  4963.1  344.31  4972.3  343.93
  4995.1  341.41  4997.3  340.24  4997.8  339.44  5003.8  339.44  5004.3  340.24
  5006.6  341.23  5022.5  342.39  5029.5  344.00  5038.5  344.74  5044.2  344.51
  5081.9  345.98  5103.6  345.89  5119.6  346.90  5147.0  346.71  5180.7  347.88
  5311.8  349.39  5348.4  350.92  5586.3  354.26  5619.1  355.18  5641.5  355.13
#Mann=5,-1,0
  4573.4    0.05       0  4842.1     0.1       0  4997.3    0.07       0
  5004.3     0.1       0  5180.7    0.05       0
Bank Sta=4997.3,5004.3
Exp/Cntr=0.3,0.1