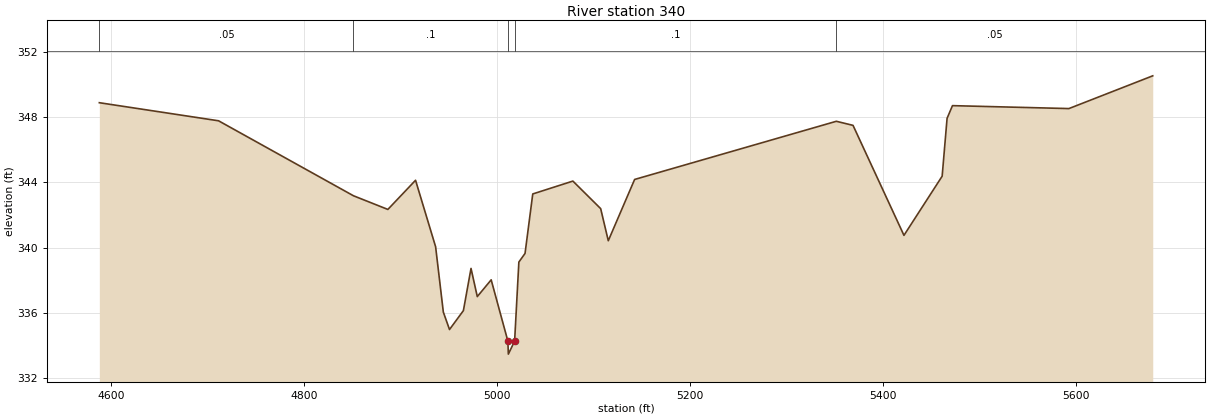
HEC-RAS study UNT 062 in RCW.prj: UNT 062 in RCW Base Level Engineering

--- UNT 062 in RCW.g01 (geometry) --- (continued)

Type RM Length L Ch R = 1,340,0,0,0
BEGIN DESCRIPTION:
UNT 062 in RCW 1.0
END DESCRIPTION:
XS GIS Cut Line= 4
      2059988.78     13428831.14      2059867.26     13428539.49
      2059689.74     13428320.29      2059198.55     13428372.67
#Sta/Elev= 30
  4587.6  348.89  4711.2  347.78  4851.0  343.18  4886.7  342.34  4915.4  344.13
  4936.2  340.05  4944.2  336.04  4950.6  334.97  4965.0  336.13  4972.9  338.72
  4979.4  336.99  4993.8  338.02  5011.1  334.26  5011.6  333.46  5018.1  334.26
  5022.5  339.11  5028.9  339.64  5036.9  343.29  5078.5  344.08  5107.3  342.39
  5115.2  340.42  5142.5  344.18  5351.6  347.75  5368.9  347.50  5421.7  340.75
  5461.3  344.38  5466.4  347.93  5472.0  348.71  5592.7  348.53  5679.6  350.54
#Mann=5,-1,0
  4587.6    0.05       0  4851.0     0.1       0  5011.1    0.07       0
  5018.1     0.1       0  5351.6    0.05       0
Bank Sta=5011.1,5018.1
Exp/Cntr=0.3,0.1

Chan Stop Cuts=-1