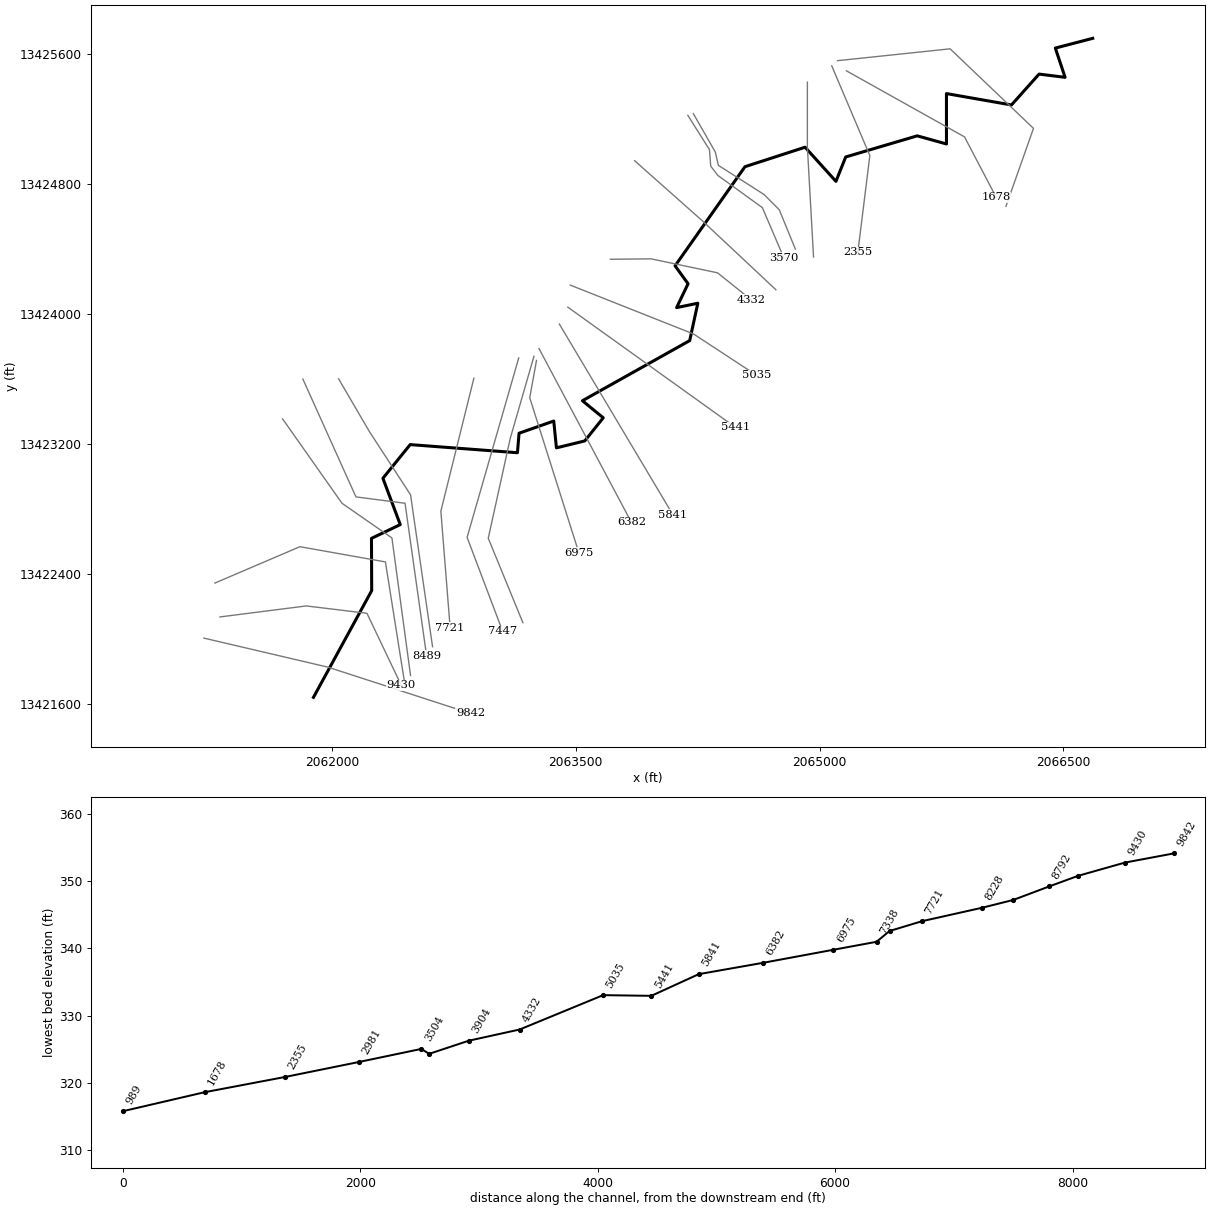
--- UNT 065 in RCW.prj (project) ---

Proj Title=UNT 065 in RCW Base Level Engineering
Current Plan=p01
Default Exp/Contr=0.3,0.1
English Units
Geom File=g01
Flow File=f01
Plan File=p01
BEGIN DESCRIPTION:
UNT 065 in RCW
END DESCRIPTION:

--- UNT 065 in RCW.p01 (plan) ---

Plan Title=Multiple Run
Short Identifier=Multiple
Geom File=g01
Flow File=f01
Subcritical Flow
K Sum by GR= 0
Std Step Tol= 0.01
Critical Tol= 0.01
Num of Std Step Trials= 20
Max Error Tol= 0.3
Flow Tol Ratio= 0.001
Split Flow NTrial= 30
Split Flow Tol= 0.02
Split Flow Ratio= 0.02
Log Output Level= 0
Friction Slope Method= 1
Unsteady Friction Slope Method= 2
Unsteady Bridges Friction Slope Method= 1
Parabolic Critical Depth
Global Vel Dist=  1 , 1 , 1
Global Log Level= 0
CheckData=True
Encroach Param= -1, 0, 0, 0
BEGIN DESCRIPTION:
Multiple Run
END DESCRIPTION:

--- UNT 065 in RCW.f01 (steady flow) ---

Flow Title=Multiple
Number of Profiles=7
Profile Names=10-year,25-year,50-year,1pct_min,100-year,1pct_plu,500-year
River Rch & RM= UNT 065 in RCW,Reach-1,9842
     183     252     308     188     376     749     567
River Rch & RM= UNT 065 in RCW,Reach-1,8792
     242     336     415     255     509    1017     780
River Rch & RM= UNT 065 in RCW,Reach-1,1678
     284     399     495     306     611    1219     946
Boundary for River Rch & Prof#=UNT 065 in RCW,Reach-1,1
Up Type=0
Dn Type=3
Dn Slope=0.005
Boundary for River Rch & Prof#=UNT 065 in RCW,Reach-1,2
Up Type=0
Dn Type=3
Dn Slope=0.005
Boundary for River Rch & Prof#=UNT 065 in RCW,Reach-1,3
Up Type=0
Dn Type=3
Dn Slope=0.005
Boundary for River Rch & Prof#=UNT 065 in RCW,Reach-1,4
Up Type=0
Dn Type=3
Dn Slope=0.005
Boundary for River Rch & Prof#=UNT 065 in RCW,Reach-1,5
Up Type=0
Dn Type=3
Dn Slope=0.005
Boundary for River Rch & Prof#=UNT 065 in RCW,Reach-1,6
Up Type=0
Dn Type=3
Dn Slope=0.005
Boundary for River Rch & Prof#=UNT 065 in RCW,Reach-1,7
Up Type=0
Dn Type=3
Dn Slope=0.005

--- UNT 065 in RCW.g01 (geometry) ---

Geom Title=Existing Conditions

River Reach=UNT 065 in RCW,Reach-1
Reach XY= 30
      2061885.80     13421639.54      2062243.99     13422295.98
      2062242.68     13422617.59      2062419.77     13422702.23
      2062313.00     13422987.39      2062480.80     13423194.54
      2063140.80     13423144.54      2063150.80     13423264.54
      2063364.21     13423339.57      2063380.80     13423174.54
      2063555.18     13423217.17      2063668.89     13423359.54
      2063540.80     13423464.54      2064200.80     13423834.54
      2064250.80     13424064.54      2064120.28     13424037.49
      2064190.80     13424184.54      2064110.80     13424294.54
      2064540.80     13424904.54      2064910.80     13425024.54
      2065100.80     13424814.54      2065160.80     13424964.54
      2065600.80     13425094.54      2065780.80     13425044.54
      2065780.80     13425354.54      2066180.80     13425284.54
      2066350.80     13425474.54      2066510.80     13425454.54
      2066450.80     13425634.54      2066680.80     13425694.54

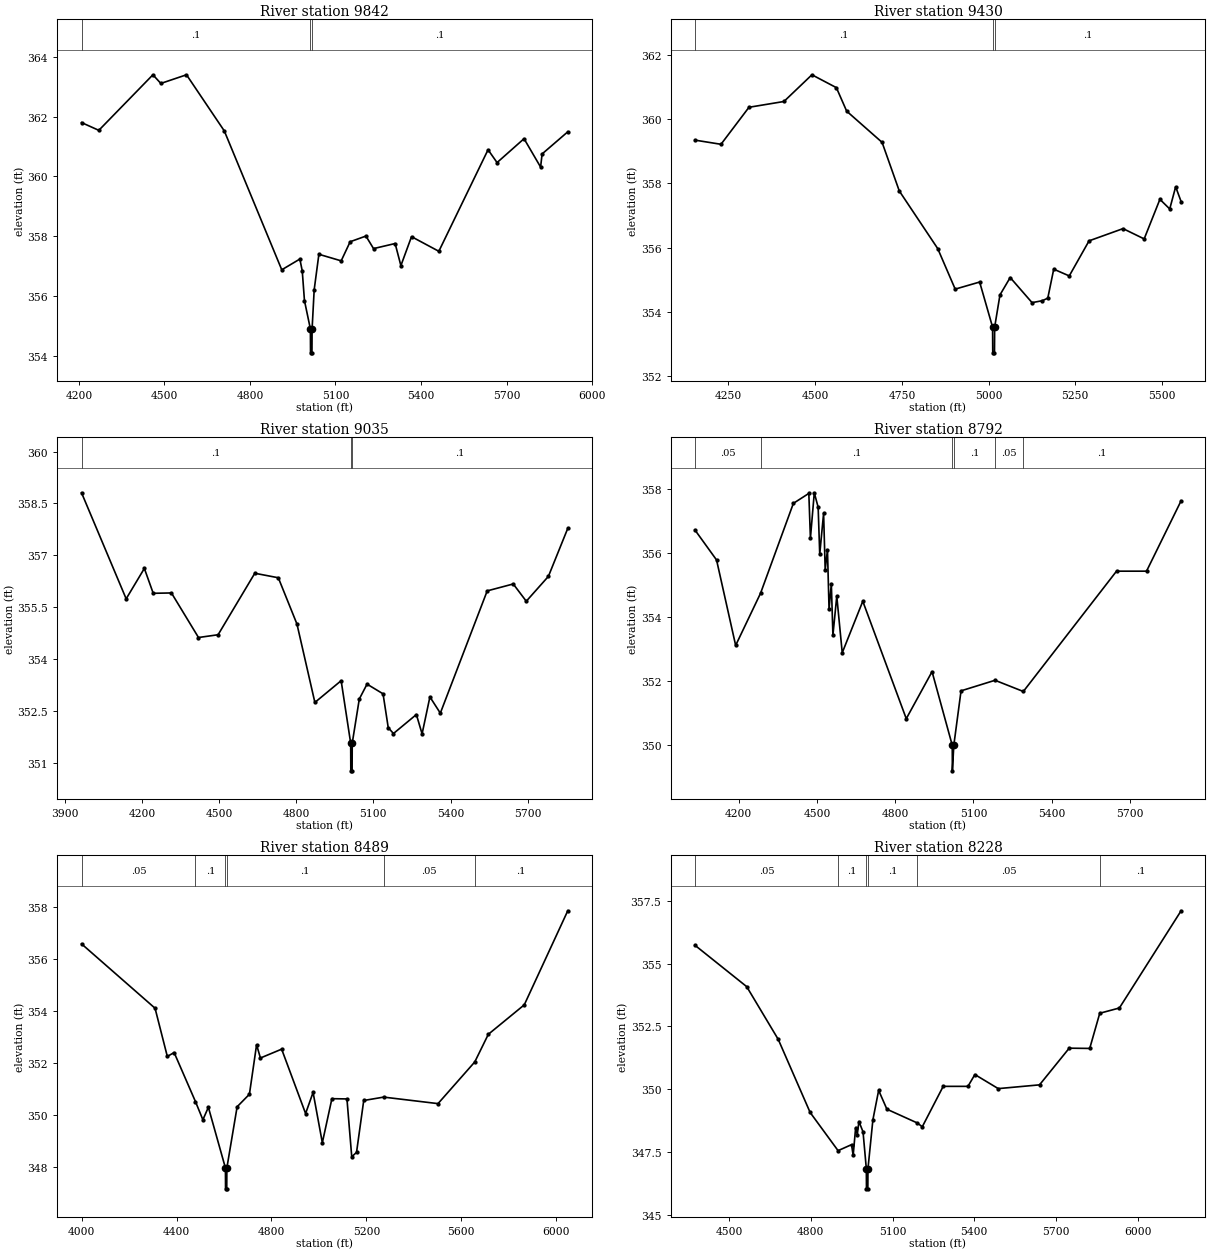
Type RM Length L Ch R = 1,9842,412,412,412
BEGIN DESCRIPTION:
UNT 065 in RCW 15.0
END DESCRIPTION:
XS GIS Cut Line= 3
      2061211.27     13422003.89      2061975.00     13421825.00
      2062850.90     13421540.67
#Sta/Elev= 30
  4209.5  361.80  4270.1  361.54  4459.8  363.40  4487.6  363.11  4577.6  363.40
  4710.2  361.52  4911.7  356.87  4975.2  357.23  4983.6  356.83  4991.3  355.84
  5012.1  354.89  5012.6  354.09  5017.6  354.09  5018.1  354.89  5025.4  356.20
  5041.9  357.39  5120.1  357.17  5151.6  357.81  5206.9  358.00  5233.6  357.58
  5309.3  357.75  5329.5  357.01  5366.8  357.98  5462.6  357.49  5635.2  360.89
  5666.8  360.46  5761.4  361.26  5819.5  360.31  5824.8  360.75  5914.8  361.49
#Mann=3,-1,0
  4209.5     0.1       0  5012.1    0.07       0  5018.1     0.1       0
Bank Sta=5012.1,5018.1
Exp/Cntr=0.3,0.1

Type RM Length L Ch R = 1,9430,395,395,395
BEGIN DESCRIPTION:
Mapping XS ba94a3cb
END DESCRIPTION:
XS GIS Cut Line= 4
      2061310.26     13422134.11      2061841.46     13422201.81
      2062214.82     13422156.55      2062425.77     13421713.83
#Sta/Elev= 30
  4153.1  359.34  4228.4  359.21  4309.1  360.36  4409.9  360.54  4490.6  361.37
  4561.1  360.97  4590.8  360.24  4692.9  359.27  4742.5  357.76  4853.3  355.97
  4903.7  354.71  4974.2  354.93  5011.5  353.53  5012.0  352.73  5017.0  352.73
  5017.5  353.53  5032.8  354.53  5062.3  355.07  5125.3  354.29  5155.0  354.35
  5170.7  354.43  5187.8  355.33  5232.6  355.12  5289.7  356.21  5387.7  356.59
  5448.6  356.27  5494.0  357.50  5522.3  357.20  5539.4  357.89  5555.1  357.43
#Mann=3,-1,0
  4153.1     0.1       0  5011.5    0.07       0  5017.5     0.1       0
Bank Sta=5011.5,5017.5
Exp/Cntr=0.3,0.1

Type RM Length L Ch R = 1,9035,243,243,243
BEGIN DESCRIPTION:
Mapping XS 83e28f78
END DESCRIPTION:
XS GIS Cut Line= 4
      2061278.95     13422342.43      2061802.40     13422566.39
      2062328.44     13422472.64      2062451.80     13421695.65
#Sta/Elev= 30
  3965.5  358.81  4139.0  355.74  4209.7  356.62  4244.2  355.90  4315.0  355.91
  4420.2  354.62  4496.4  354.70  4639.1  356.48  4730.5  356.35  4803.0  355.01
  4872.7  352.74  4974.8  353.37  5011.9  351.56  5012.4  350.76  5017.4  350.76
  5017.9  351.56  5045.4  352.84  5075.5  353.27  5137.7  352.99  5157.9  352.01
  5178.2  351.84  5267.3  352.39  5289.5  351.83  5319.9  352.90  5360.4  352.43
  5542.7  355.97  5643.9  356.17  5694.6  355.67  5780.6  356.39  5855.9  357.78
#Mann=3,-1,0
  3965.5     0.1       0  5011.9    0.07       0  5017.9     0.1       0
Bank Sta=5011.9,5017.9
Exp/Cntr=0.3,0.1

Type RM Length L Ch R = 1,8792,303,303,303
BEGIN DESCRIPTION:
Mapping XS 8b54ed98
END DESCRIPTION:
XS GIS Cut Line= 4
      2061695.63     13423352.84      2062061.18     13422833.63
      2062368.47     13422620.09      2062483.06     13421773.70
#Sta/Elev= 30
  4032.3  356.72  4115.4  355.78  4188.6  353.11  4284.0  354.74  4409.8  357.55
  4469.0  357.86  4475.1  356.46  4489.9  357.88  4504.7  357.43  4510.8  355.96
  4525.6  357.24  4531.7  355.47  4540.4  356.10  4546.5  354.24  4555.2  355.04
  4561.3  353.43  4576.1  354.65  4597.0  352.88  4675.8  354.49  4842.4  350.82
  4941.2  352.29  5018.6  349.99  5019.1  349.19  5024.6  349.99  5052.3  351.69
  5182.5  352.02  5291.0  351.67  5648.1  355.43  5763.1  355.43  5895.6  357.63
#Mann=6,-1,0
  4032.3    0.05       0  4284.0     0.1       0  5018.6    0.07       0
  5024.6     0.1       0  5182.5    0.05       0  5291.0     0.1       0
Bank Sta=5018.6,5024.6
Exp/Cntr=0.3,0.1

Type RM Length L Ch R = 1,8489,261,261,261
BEGIN DESCRIPTION:
Mapping XS 45207a24
END DESCRIPTION:
XS GIS Cut Line= 4
      2061820.63     13423597.63      2062147.11     13422872.70
      2062449.20     13422833.63      2062582.01     13421893.53
#Sta/Elev= 30
  3999.6  356.58  4309.4  354.11  4361.1  352.26  4389.8  352.41  4479.6  350.53
  4511.0  349.83  4534.1  350.31  4606.0  347.98  4606.5  347.18  4611.5  347.18
  4612.0  347.98  4655.3  350.33  4707.1  350.81  4737.3  352.71  4753.4  352.20
  4842.9  352.54  4943.8  350.07  4975.4  350.88  5014.4  348.95  5054.7  350.64
  5118.1  350.63  5138.3  348.41  5158.5  348.58  5188.8  350.57  5272.9  350.70
  5501.9  350.45  5656.8  352.05  5713.9  353.11  5865.4  354.24  6048.7  357.85
#Mann=6,-1,0
  3999.6    0.05       0  4479.6     0.1       0  4606.0    0.07       0
  4612.0     0.1       0  5272.9    0.05       0  5656.8     0.1       0
Bank Sta=4606,4612
Exp/Cntr=0.3,0.1

Type RM Length L Ch R = 1,8228,507,507,507
BEGIN DESCRIPTION:
Mapping XS 5e08ff17
END DESCRIPTION:
XS GIS Cut Line= 4
      2062040.37     13423599.22      2062230.45     13423273.74
      2062483.05     13422885.72      2062618.47     13421950.79
#Sta/Elev= 30
  4374.5  355.73  4564.7  354.08  4680.5  351.98  4797.6  349.07  4900.1  347.55
  4949.5  347.79  4955.5  347.36  4964.6  348.47  4970.6  348.19  4976.6  348.71
  4991.7  348.30  5003.8  346.83  5004.3  346.03  5009.3  346.03  5009.8  346.83
  5027.9  348.78  5049.0  349.95  5079.3  349.20  5191.4  348.65  5209.1  348.50
  5285.9  350.11  5376.8  350.11  5402.2  350.58  5488.0  350.02  5639.5  350.17
  5748.4  351.63  5823.7  351.62  5860.5  353.02  5932.6  353.23  6159.1  357.10
#Mann=6,-1,0
  4374.5    0.05       0  4900.1     0.1       0  5003.8    0.07       0
  5009.8     0.1       0  5191.4    0.05       0  5860.5     0.1       0
Bank Sta=5003.8,5009.8
Exp/Cntr=0.3,0.1

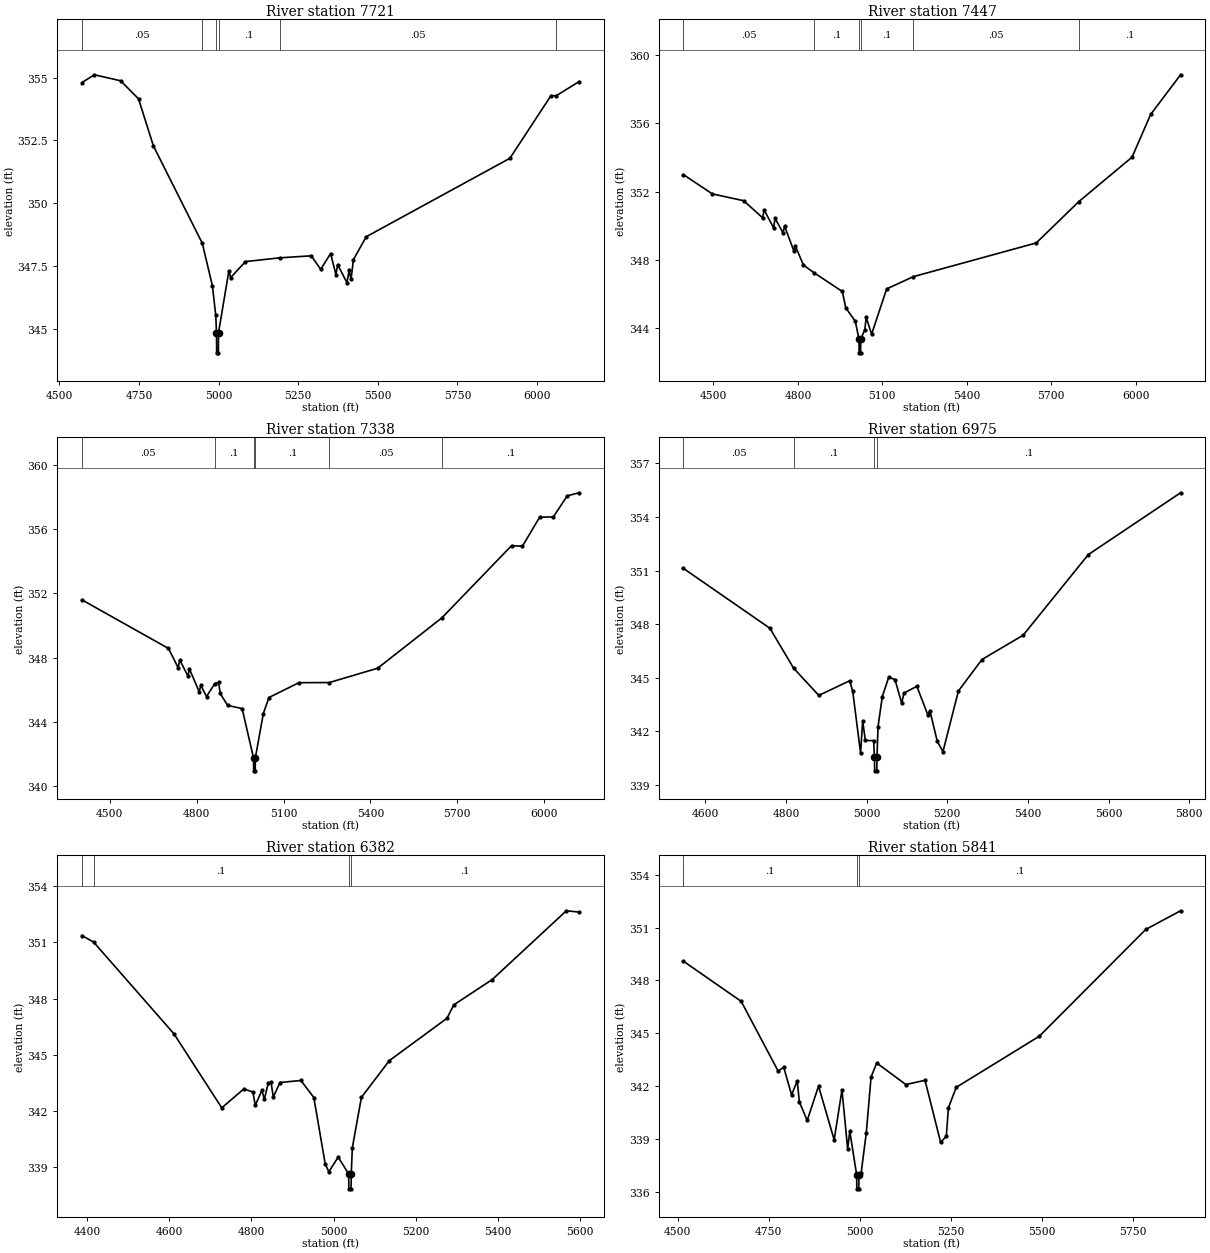
Type RM Length L Ch R = 1,7721,274,274,274
BEGIN DESCRIPTION:
Mapping XS 6e18f4de
END DESCRIPTION:
XS GIS Cut Line= 3
      2062872.72     13423602.87      2062669.58     13422785.14
      2062726.73     13422068.20
#Sta/Elev= 30
  4570.6  354.81  4609.6  355.12  4692.1  354.88  4748.3  354.16  4795.1  352.28
  4948.6  348.40  4980.6  346.69  4990.9  345.52  4993.2  344.83  4993.7  344.03
  4999.0  344.03  4999.5  344.83  5032.1  347.30  5037.7  347.03  5084.2  347.67
  5192.7  347.82  5290.9  347.90  5320.6  347.36  5351.5  347.99  5368.5  347.15
  5373.6  347.55  5403.0  346.83  5409.8  347.32  5415.8  346.96  5423.4  347.75
  5463.5  348.66  5914.9  351.79  6044.0  354.29  6059.9  354.28  6132.4  354.85
#Mann=6,-1,0
  4570.6    0.05       0  4948.6     0.1       0  4993.2    0.07       0
  4999.5     0.1       0  5192.7    0.05       0  6059.9     0.1       0
Bank Sta=4993.2,4999.5
Exp/Cntr=0.3,0.1

Type RM Length L Ch R = 1,7447,109,109,109
BEGIN DESCRIPTION:
Mapping XS 550e5780
END DESCRIPTION:
XS GIS Cut Line= 3
      2063148.76     13423727.87      2062831.04     13422623.68
      2063049.79     13422045.57
#Sta/Elev= 30
  4393.0  353.00  4495.9  351.87  4607.4  351.47  4674.8  350.47  4680.0  350.94
  4713.7  349.88  4718.9  350.44  4747.4  349.59  4752.6  349.99  4786.3  348.51
  4791.5  348.80  4819.9  347.70  4858.9  347.24  4957.9  346.16  4970.3  345.20
  5004.0  344.42  5017.2  343.37  5017.7  342.57  5023.0  342.57  5023.5  343.37
  5037.7  343.92  5042.9  344.64  5062.0  343.66  5115.5  346.31  5210.7  347.03
  5647.1  349.00  5798.6  351.42  5987.7  354.02  6053.8  356.52  6160.1  358.84
#Mann=6,-1,0
  4393.0    0.05       0  4858.9     0.1       0  5017.2    0.07       0
  5023.5     0.1       0  5210.7    0.05       0  5798.6     0.1       0
Bank Sta=5017.2,5023.5
Exp/Cntr=0.3,0.1

Type RM Length L Ch R = 1,7338,363,363,363
BEGIN DESCRIPTION:
Mapping XS 15906d6e
END DESCRIPTION:
XS GIS Cut Line= 4
      2063242.50     13423738.27      2063096.67     13423233.06
      2062961.25     13422618.47      2063174.31     13422098.82
#Sta/Elev= 30
  4404.0  351.60  4702.8  348.58  4736.4  347.37  4741.6  347.87  4770.0  346.86
  4775.2  347.30  4808.9  345.88  4814.1  346.29  4834.1  345.59  4862.5  346.39
  4875.8  346.48  4881.4  345.78  4907.0  345.04  4957.1  344.84  4996.4  341.77
  4996.9  340.97  5002.2  340.97  5002.7  341.77  5030.2  344.53  5049.7  345.53
  5153.1  346.45  5258.0  346.46  5425.0  347.35  5647.2  350.49  5887.2  354.97
  5924.9  354.94  5984.4  356.74  6031.7  356.76  6079.7  358.07  6120.8  358.26
#Mann=6,-1,0
  4404.0    0.05       0  4862.5     0.1       0  4996.4    0.07       0
  5002.7     0.1       0  5258.0    0.05       0  5647.2     0.1       0
Bank Sta=4996.4,5002.7
Exp/Cntr=0.3,0.1

Type RM Length L Ch R = 1,6975,593,593,593
BEGIN DESCRIPTION:
Mapping XS 22f30d79
END DESCRIPTION:
XS GIS Cut Line= 3
      2063258.13     13423712.27      2063216.46     13423483.06
      2063518.54     13422529.95
#Sta/Elev= 30
  4545.6  351.12  4760.1  347.77  4818.8  345.54  4881.4  344.01  4957.9  344.83
  4965.4  344.26  4985.0  340.79  4990.2  342.59  4996.8  341.49  5017.3  341.48
  5019.4  340.59  5019.9  339.79  5025.2  339.79  5025.7  340.59  5028.3  342.26
  5038.8  343.94  5054.8  345.03  5070.3  344.90  5087.1  343.56  5092.3  344.14
  5124.6  344.52  5151.7  342.92  5156.9  343.15  5175.2  341.44  5189.2  340.86
  5227.6  344.26  5286.0  346.02  5388.1  347.38  5549.6  351.89  5778.4  355.35
#Mann=4,-1,0
  4545.6    0.05       0  4818.8     0.1       0  5019.4    0.07       0
  5025.7     0.1       0
Bank Sta=5019.4,5025.7
Exp/Cntr=0.3,0.1

Type RM Length L Ch R = 1,6382,541,541,541
BEGIN DESCRIPTION:
Mapping XS e134f139
END DESCRIPTION:
XS GIS Cut Line= 2
      2063273.73     13423785.17      2063841.46     13422717.42
#Sta/Elev= 30
  4388.1  351.36  4416.4  351.01  4611.8  346.12  4728.1  342.17  4781.9  343.18
  4803.9  343.01  4809.6  342.30  4825.9  343.11  4831.6  342.62  4841.3  343.49
  4847.9  343.53  4853.5  342.75  4869.8  343.52  4920.6  343.63  4952.1  342.72
  4979.7  339.18  4988.6  338.76  5011.2  339.54  5036.8  338.65  5037.3  337.85
  5042.6  337.85  5043.1  338.65  5045.7  340.04  5067.8  342.73  5135.8  344.69
  5276.1  346.95  5292.4  347.66  5385.9  349.01  5566.2  352.68  5597.4  352.61
#Mann=4,-1,0
  4388.1    0.05       0  4416.4     0.1       0  5036.8    0.07       0
  5043.1     0.1       0
Bank Sta=5036.8,5043.1
Exp/Cntr=0.3,0.1

Type RM Length L Ch R = 1,5841,400,400,400
BEGIN DESCRIPTION:
Mapping XS 041bfcfa
END DESCRIPTION:
XS GIS Cut Line= 2
      2063398.77     13423936.15      2064096.66     13422764.32
#Sta/Elev= 30
  4515.9  349.09  4674.5  346.81  4775.7  342.86  4791.3  343.06  4812.7  341.51
  4828.3  342.29  4834.1  341.10  4855.6  340.05  4886.7  342.00  4929.6  338.95
  4951.0  341.78  4966.6  338.44  4972.4  339.44  4991.2  336.97  4991.7  336.17
  4997.1  336.17  4997.6  336.97  5003.6  337.07  5017.7  339.35  5030.8  342.52
  5046.4  343.31  5126.2  342.09  5178.8  342.33  5221.6  338.81  5237.2  339.15
  5243.0  340.77  5264.4  341.93  5492.3  344.83  5784.3  350.89  5879.8  351.95
#Mann=3,-1,0
  4515.9     0.1       0  4991.2    0.07       0  4997.6     0.1       0
Bank Sta=4991.2,4997.6
Exp/Cntr=0.3,0.1

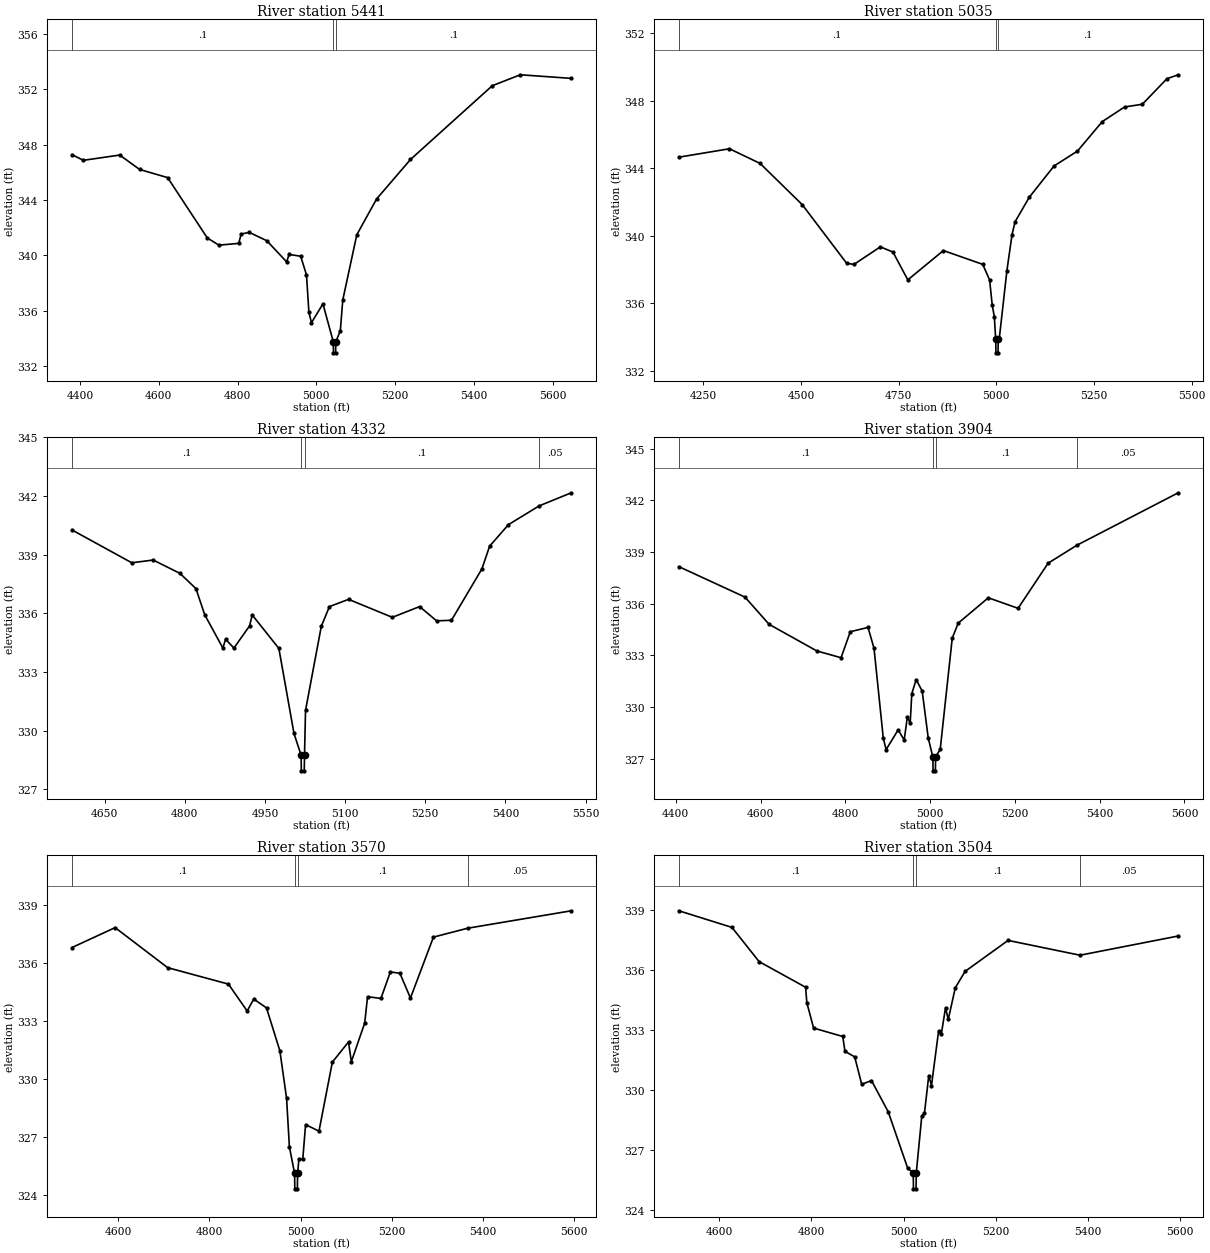
Type RM Length L Ch R = 1,5441,406,406,406
BEGIN DESCRIPTION:
Mapping XS 12266c8a
END DESCRIPTION:
XS GIS Cut Line= 2
      2063450.87     13424040.32      2064481.03     13423301.52
#Sta/Elev= 30
  4379.6  347.27  4408.8  346.86  4500.9  347.24  4551.3  346.20  4622.5  345.61
  4723.2  341.25  4752.7  340.73  4803.0  340.86  4809.2  341.54  4830.1  341.65
  4874.3  341.05  4924.6  339.52  4930.8  340.06  4960.2  339.93  4975.0  338.58
  4981.1  335.87  4987.7  335.13  5016.7  336.49  5043.0  333.75  5043.5  332.95
  5048.9  332.95  5049.4  333.75  5060.9  334.55  5067.1  336.77  5102.7  341.48
  5153.0  344.07  5239.0  346.92  5446.6  352.25  5517.8  353.04  5647.3  352.78
#Mann=3,-1,0
  4379.6     0.1       0  5043.0    0.07       0  5049.4     0.1       0
Bank Sta=5043,5049.4
Exp/Cntr=0.3,0.1

Type RM Length L Ch R = 1,5035,703,703,703
BEGIN DESCRIPTION:
UNT 065 in RCW 9.0
END DESCRIPTION:
XS GIS Cut Line= 3
      2063465.63     13424176.19      2064225.00     13423875.00
      2064610.70     13423621.99
#Sta/Elev= 30
  4187.6  344.66  4317.1  345.16  4395.5  344.29  4503.5  341.84  4617.2  338.36
  4635.9  338.30  4703.3  339.34  4735.6  339.03  4773.6  337.38  4864.7  339.12
  4965.4  338.30  4983.0  337.37  4989.7  335.87  4995.0  335.20  4998.6  333.85
  4999.1  333.05  5004.5  333.05  5005.0  333.85  5007.5  333.85  5027.2  337.92
  5040.4  340.07  5048.2  340.83  5084.4  342.28  5148.0  344.14  5207.8  345.02
  5271.2  346.77  5328.5  347.64  5373.8  347.80  5437.0  349.32  5465.8  349.55
#Mann=3,-1,0
  4187.6     0.1       0  4998.6    0.07       0  5005.0     0.1       0
Bank Sta=4998.6,5005
Exp/Cntr=0.3,0.1

Type RM Length L Ch R = 1,4332,428,428,428
BEGIN DESCRIPTION:
Mapping XS d9355021
END DESCRIPTION:
XS GIS Cut Line= 4
      2063713.02     13424335.05      2063962.99     13424337.66
      2064371.84     13424251.72      2064580.12     13424085.10
#Sta/Elev= 30
  4588.8  340.27  4700.8  338.59  4740.8  338.73  4790.8  338.05  4820.8  337.27
  4837.3  335.93  4871.2  334.23  4876.3  334.68  4891.9  334.23  4921.1  335.36
  4926.2  335.92  4976.0  334.21  5004.3  329.86  5017.6  328.75  5018.1  327.95
  5023.5  327.95  5024.0  328.75  5025.9  331.04  5055.4  335.34  5070.6  336.35
  5106.5  336.72  5188.3  335.80  5239.4  336.35  5271.2  335.62  5299.0  335.65
  5356.0  338.28  5370.4  339.44  5405.6  340.54  5463.1  341.50  5523.3  342.17
#Mann=4,-1,0
  4588.8     0.1       0  5017.6    0.07       0  5024.0     0.1       0
  5463.1    0.05       0
Bank Sta=5017.6,5024
Exp/Cntr=0.3,0.1

Type RM Length L Ch R = 1,3904,334,334,334
BEGIN DESCRIPTION:
UNT 065 in RCW 8.0
END DESCRIPTION:
XS GIS Cut Line= 3
      2063861.44     13424941.81      2064275.00     13424575.00
      2064731.24     13424147.53
#Sta/Elev= 30
  4407.4  338.15  4563.4  336.38  4620.2  334.80  4733.1  333.25  4790.0  332.86
  4811.8  334.37  4853.6  334.62  4867.8  333.40  4889.5  328.21  4896.2  327.52
  4924.7  328.67  4938.9  328.08  4946.4  329.41  4953.1  329.07  4956.9  330.78
  4967.3  331.59  4981.4  330.92  4995.6  328.20  5006.5  327.09  5007.0  326.29
  5012.5  326.29  5013.0  327.09  5023.9  327.54  5052.3  334.00  5066.4  334.87
  5137.3  336.34  5207.6  335.73  5278.4  338.35  5346.1  339.39  5585.4  342.44
#Mann=4,-1,0
  4407.4     0.1       0  5006.5    0.07       0  5013.0     0.1       0
  5346.1    0.05       0
Bank Sta=5006.5,5013
Exp/Cntr=0.3,0.1

Type RM Length L Ch R = 1,3570,66,66,66
BEGIN DESCRIPTION:
Mapping XS 9e2d04a0
END DESCRIPTION:
XS GIS Cut Line= 6
      2064189.57     13425220.45      2064322.36     13425009.53
      2064330.18     13424907.97      2064374.45     13424850.68
      2064647.88     13424652.76      2064780.34     13424343.70
#Sta/Elev= 30
  4497.8  336.81  4592.7  337.84  4708.1  335.77  4841.7  334.92  4882.8  333.53
  4897.3  334.15  4925.3  333.69  4954.7  331.47  4969.4  329.02  4975.6  326.51
  4987.0  325.14  4987.5  324.34  4993.1  324.34  4993.6  325.14  4996.5  325.87
  5005.0  325.88  5011.2  327.66  5040.6  327.32  5070.0  330.89  5105.5  331.93
  5111.7  330.91  5141.1  332.91  5147.3  334.27  5176.7  334.18  5197.5  335.55
  5218.4  335.48  5241.6  334.20  5292.1  337.35  5367.7  337.81  5595.1  338.71
#Mann=4,-1,0
  4497.8     0.1       0  4987.0    0.07       0  4993.6     0.1       0
  5367.7    0.05       0
Bank Sta=4987,4993.6
Exp/Cntr=0.3,0.1

Type RM Length L Ch R = 1,3504,523,523,523
BEGIN DESCRIPTION:
Mapping XS a378fcc1
END DESCRIPTION:
XS GIS Cut Line= 6
      2064223.39     13425230.92      2064358.82     13424993.91
      2064377.05     13424913.18      2064658.30     13424733.49
      2064752.05     13424639.74      2064851.01     13424397.55
#Sta/Elev= 30
  4512.2  338.96  4627.4  338.13  4686.4  336.42  4787.2  335.14  4789.9  334.37
  4804.6  333.10  4867.9  332.68  4872.6  331.94  4893.8  331.66  4909.0  330.29
  4930.2  330.48  4966.5  328.92  5008.8  326.10  5020.8  325.87  5021.3  325.07
  5026.9  325.07  5027.4  325.87  5039.3  328.69  5045.2  328.86  5054.5  330.73
  5060.4  330.23  5075.7  332.93  5081.6  332.78  5090.9  334.12  5096.8  333.53
  5112.0  335.11  5133.2  335.93  5226.6  337.48  5382.7  336.74  5595.9  337.70
#Mann=4,-1,0
  4512.2     0.1       0  5020.8    0.07       0  5027.4     0.1       0
  5382.7    0.05       0
Bank Sta=5020.8,5027.4
Exp/Cntr=0.3,0.1

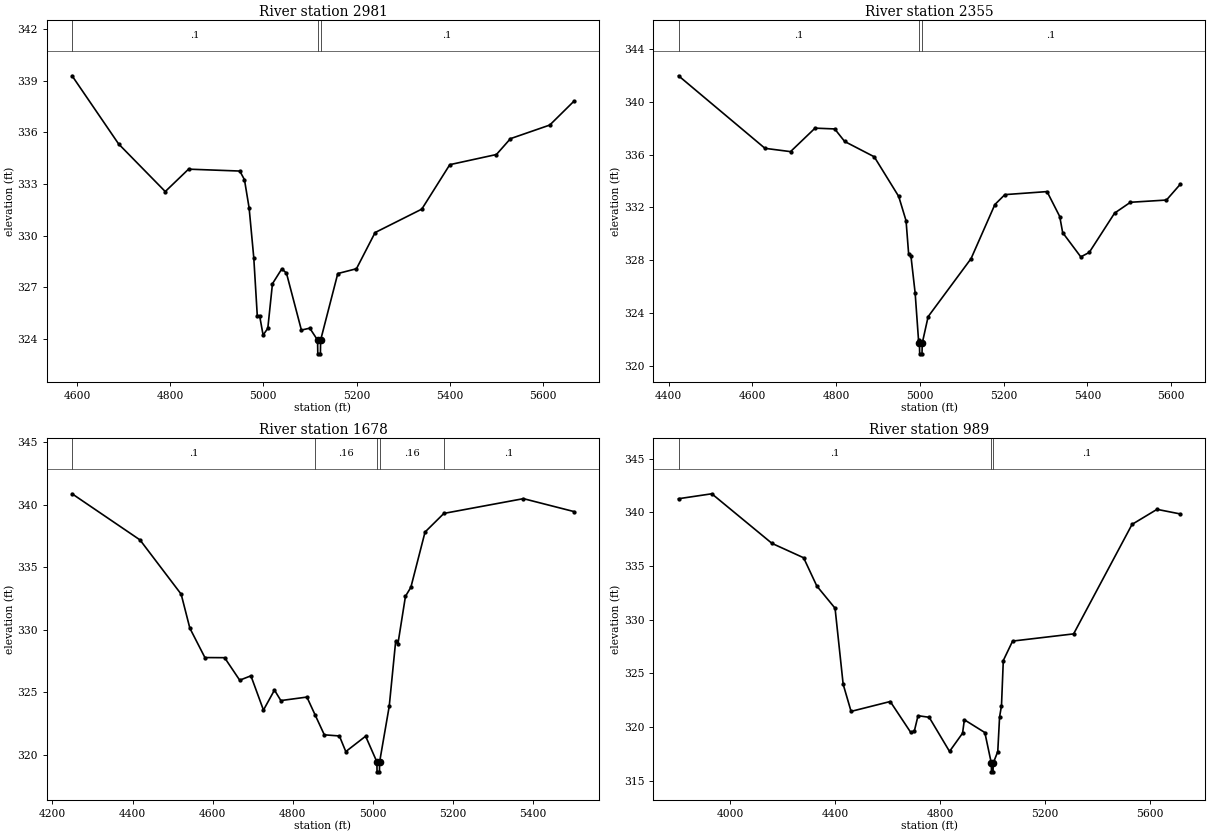
Type RM Length L Ch R = 1,2981,626,626,626
BEGIN DESCRIPTION:
UNT 065 in RCW 6.0
END DESCRIPTION:
XS GIS Cut Line= 3
      2064925.00     13425425.02      2064925.00     13425025.00
      2064962.93     13424349.08
#Sta/Elev= 30
  4589.5  339.28  4689.5  335.32  4789.5  332.56  4839.5  333.86  4949.5  333.75
  4959.5  333.25  4969.5  331.61  4979.5  328.72  4987.0  325.36  4992.0  325.36
  4999.5  324.23  5009.6  324.62  5019.6  327.21  5039.6  328.07  5049.6  327.83
  5081.7  324.52  5099.7  324.63  5116.4  323.94  5116.9  323.14  5122.5  323.14
  5123.0  323.94  5159.8  327.80  5199.9  328.08  5239.9  330.18  5340.1  331.54
  5400.2  334.12  5500.3  334.71  5530.4  335.63  5614.8  336.42  5666.5  337.80
#Mann=3,-1,0
  4589.5     0.1       0  5116.4    0.07       0  5123.0     0.1       0
Bank Sta=5116.4,5123
Exp/Cntr=0.3,0.1

Type RM Length L Ch R = 1,2355,677,677,677
BEGIN DESCRIPTION:
UNT 065 in RCW 5.0
END DESCRIPTION:
XS GIS Cut Line= 3
      2065075.00     13425525.00      2065309.34     13424973.08
      2065235.66     13424379.25
#Sta/Elev= 30
  4423.7  341.98  4630.1  336.48  4691.1  336.23  4749.6  338.01  4796.6  337.95
  4820.3  337.00  4890.9  335.84  4949.4  332.83  4966.9  330.99  4973.1  328.46
  4978.5  328.33  4988.6  325.51  4996.7  321.92  4998.9  321.70  4999.4  320.90
  5005.0  320.90  5005.5  321.70  5019.6  323.72  5122.1  328.12  5179.0  332.22
  5202.8  332.97  5303.5  333.20  5333.8  331.31  5340.8  330.09  5384.1  328.25
  5404.3  328.59  5464.8  331.57  5502.6  332.39  5588.6  332.56  5621.7  333.76
#Mann=3,-1,0
  4423.7     0.1       0  4998.9    0.07       0  5005.5     0.1       0
Bank Sta=4998.9,5005.5
Exp/Cntr=0.3,0.1

Type RM Length L Ch R = 1,1678,689,689,689
BEGIN DESCRIPTION:
UNT 065 in RCW 4.0
END DESCRIPTION:
XS GIS Cut Line= 3
      2065165.22     13425494.57      2065891.81     13425088.31
      2066087.14     13424715.88
#Sta/Elev= 30
  4248.9  340.88  4418.5  337.19  4521.3  332.85  4543.0  330.13  4580.6  327.78
  4629.8  327.77  4667.5  325.97  4695.5  326.32  4726.8  323.58  4754.3  325.18
  4770.2  324.34  4835.3  324.62  4855.4  323.22  4878.8  321.60  4916.4  321.51
  4932.4  320.26  4981.9  321.49  5010.0  319.44  5010.5  318.64  5016.4  318.64
  5016.9  319.44  5040.9  323.89  5056.9  329.07  5062.6  328.88  5081.4  332.68
  5094.9  333.40  5130.3  337.82  5177.4  339.31  5376.0  340.49  5501.9  339.46
#Mann=5,-1,0
  4248.9     0.1       0  4855.4    0.16       0  5010.0    0.07       0
  5016.9    0.16       0  5177.4     0.1       0
Bank Sta=5010,5016.9
Exp/Cntr=0.3,0.1

Type RM Length L Ch R = 1,989,0,0,0
BEGIN DESCRIPTION:
UNT 065 in RCW 1.0
END DESCRIPTION:
XS GIS Cut Line= 4
      2065110.55     13425557.06      2065803.27     13425629.98
      2066316.29     13425140.39      2066147.01     13424661.20
#Sta/Elev= 30
  3803.1  341.26  3930.0  341.72  4159.5  337.10  4280.2  335.76  4330.5  333.13
  4400.1  331.06  4431.0  323.98  4461.2  321.45  4610.6  322.37  4688.3  319.51
  4702.4  319.61  4716.6  321.05  4759.1  320.90  4836.7  317.72  4886.4  319.42
  4893.3  320.67  4971.4  319.48  4996.2  316.62  4996.7  315.82  5002.7  315.82
  5003.2  316.62  5020.7  317.71  5027.6  320.93  5034.9  321.99  5041.8  326.19
  5077.3  328.00  5310.0  328.67  5532.9  338.87  5628.1  340.27  5717.0  339.84
#Mann=3,-1,0
  3803.1     0.1       0  4996.2    0.07       0  5003.2     0.1       0
Bank Sta=4996.2,5003.2
Exp/Cntr=0.3,0.1

Chan Stop Cuts=-1