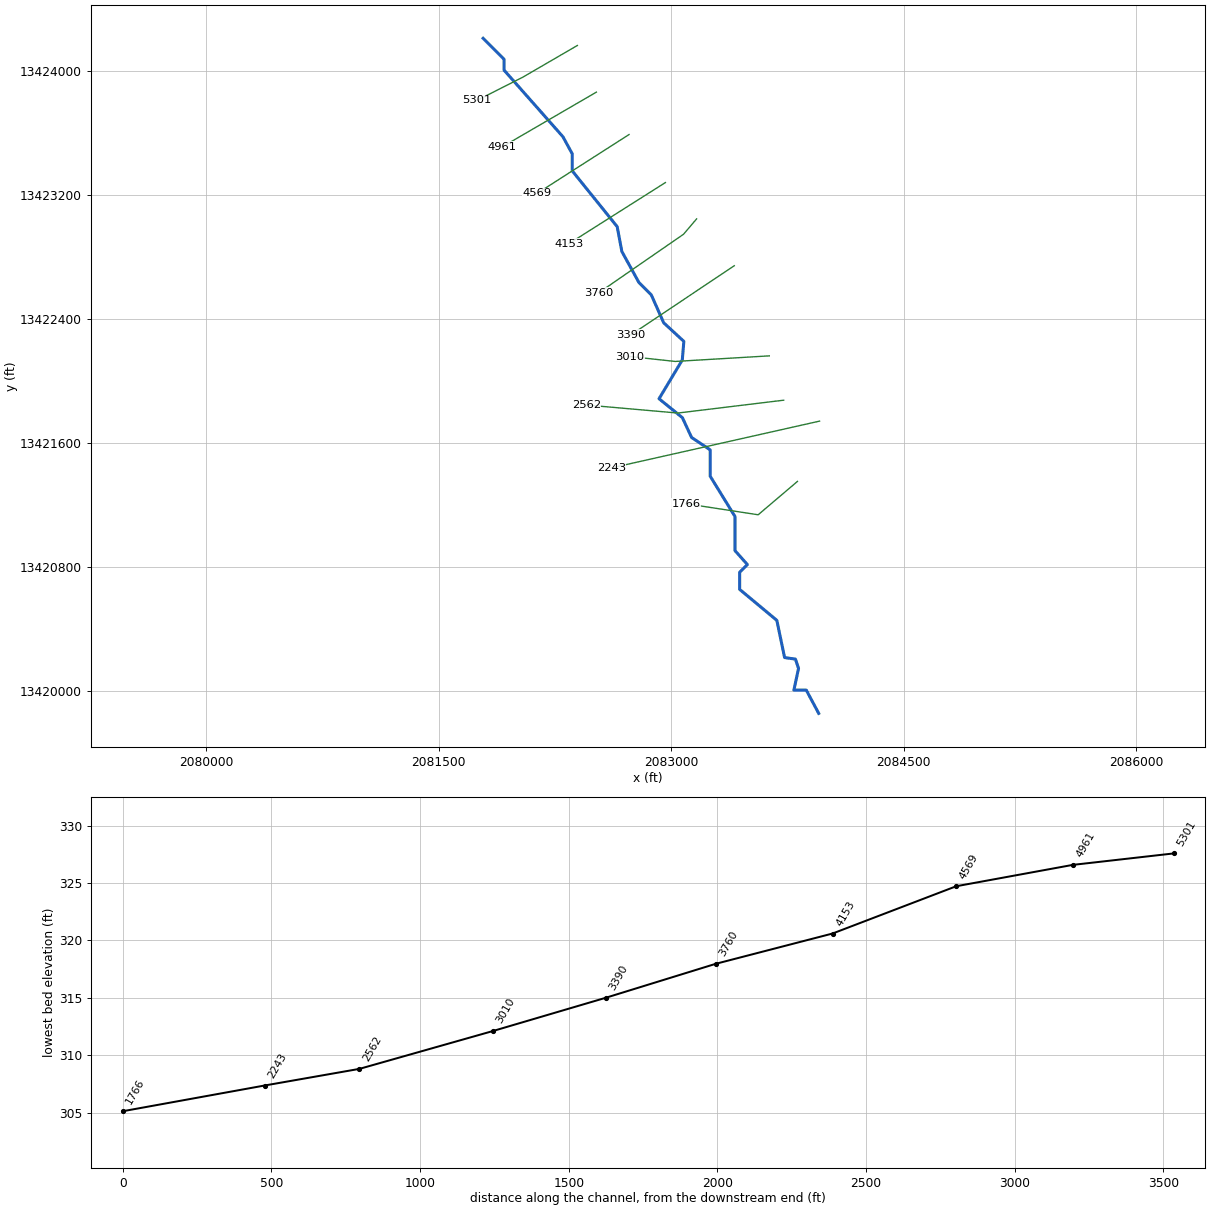
--- UNT 066 in RCW.prj (project) ---

Proj Title=UNT 066 in RCW Base Level Engineering
Current Plan=p01
Default Exp/Contr=0.3,0.1
English Units
Geom File=g01
Flow File=f01
Plan File=p01
Y Axis Title=Elevation
X Axis Title(PF)=Main Channel Distance
X Axis Title(XS)=Station
BEGIN DESCRIPTION:
UNT 066 in RCW
END DESCRIPTION:
DSS Export Rating Curves= 0
DSS Export Rating Curve Sorted= 0
DSS Export Volume Flow Curves= 0
DXF OffsetX= 0
DXF OffsetY= 0
DXF ScaleX= 1
DXF ScaleY= 10

--- UNT 066 in RCW.p01 (plan) ---

Plan Title=Multiple Run
Short Identifier=Multiple
Geom File=g01
Flow File=f01
Subcritical Flow
K Sum by GR= 0
Std Step Tol= 0.01
Critical Tol= 0.01
Num of Std Step Trials= 20
Max Error Tol= 0.3
Flow Tol Ratio= 0.001
Split Flow NTrial= 30
Split Flow Tol= 0.02
Split Flow Ratio= 0.02
Log Output Level= 0
Friction Slope Method= 1
Unsteady Friction Slope Method= 2
Unsteady Bridges Friction Slope Method= 1
Parabolic Critical Depth
Global Vel Dist=  1 , 1 , 1
Global Log Level= 0
CheckData=True
Encroach Param= -1, 0, 0, 0
BEGIN DESCRIPTION:
Multiple Run
END DESCRIPTION:

--- UNT 066 in RCW.f01 (steady flow) ---

Flow Title=Multiple
Number of Profiles=7
Profile Names=10-year,25-year,50-year,1pct_min,100-year,1pct_plu,500-year
River Rch & RM= UNT 066 in RCW,Reach-1,5301
      80     100     115      66     132     263     175
River Rch & RM= UNT 066 in RCW,Reach-1,2562
     122     159     187     110     220     438     307
Boundary for River Rch & Prof#=UNT 066 in RCW,Reach-1,1
Up Type=0
Dn Type=3
Dn Slope=0.005
Boundary for River Rch & Prof#=UNT 066 in RCW,Reach-1,2
Up Type=0
Dn Type=3
Dn Slope=0.005
Boundary for River Rch & Prof#=UNT 066 in RCW,Reach-1,3
Up Type=0
Dn Type=3
Dn Slope=0.005
Boundary for River Rch & Prof#=UNT 066 in RCW,Reach-1,4
Up Type=0
Dn Type=3
Dn Slope=0.005
Boundary for River Rch & Prof#=UNT 066 in RCW,Reach-1,5
Up Type=0
Dn Type=3
Dn Slope=0.005
Boundary for River Rch & Prof#=UNT 066 in RCW,Reach-1,6
Up Type=0
Dn Type=3
Dn Slope=0.005
Boundary for River Rch & Prof#=UNT 066 in RCW,Reach-1,7
Up Type=0
Dn Type=3
Dn Slope=0.005

--- UNT 066 in RCW.g01 (geometry) ---

Geom Title=Existing Conditions
Program Version=5.05

River Reach=UNT 066 in RCW  ,Reach-1
Reach XY= 30
       2081785.8     13424209.54       2081920.8     13424074.54
       2081920.8     13424004.54       2082300.8     13423574.54
       2082360.8     13423464.54       2082360.8     13423354.54
       2082650.8     13422994.54       2082680.8     13422834.54
       2082790.8     13422634.54       2082870.8     13422554.54
       2082950.8     13422374.54       2083080.8     13422254.54
       2083070.8     13422134.54       2082920.8     13421884.54
      2083071.26     13421762.56       2083130.8     13421634.54
       2083250.8     13421554.54       2083250.8     13421384.54
       2083410.8     13421124.54       2083410.8     13420904.54
       2083490.8     13420814.54       2083440.8     13420764.54
       2083440.8     13420654.54       2083680.8     13420454.54
       2083730.8     13420214.54       2083800.8     13420204.54
       2083820.8     13420144.54       2083790.8     13420004.54
       2083870.8     13420004.54       2083950.8     13419854.54

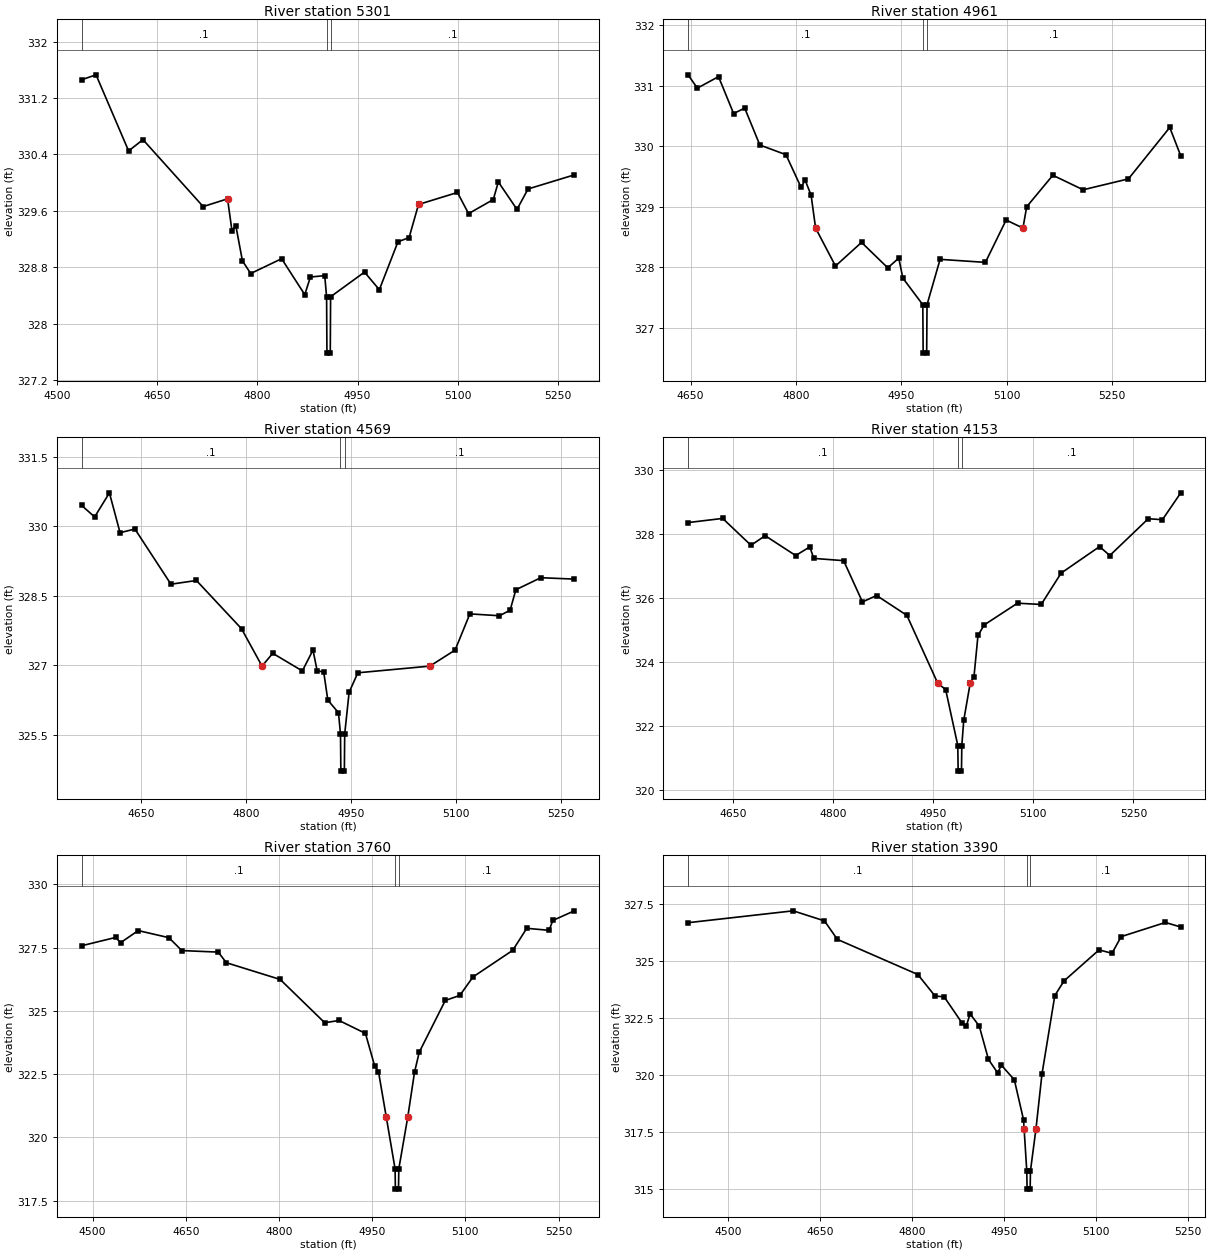
Type RM Length L Ch R = 1 ,5301    ,340,340,340
BEGIN DESCRIPTION:
UNT 066 in RCW 10.0
END DESCRIPTION:
XS GIS Cut Line= 3
      2082394.08      13424163.6      2082041.67     13423958.75
      2081746.72     13423809.47
#Sta/Elev= 30
  4536.5  331.46  4558.2  331.53    4607  330.45  4628.5  330.61  4718.7  329.66
  4755.2  329.77  4761.8  329.32  4767.6  329.39  4777.5  328.89  4789.9  328.71
  4836.2  328.92  4870.9  328.41  4879.3  328.66  4900.8  328.68  4903.6  328.38
  4904.1  327.58  4909.1  327.58  4909.6  328.38  4960.4  328.73  4982.6  328.48
  5010.5  329.16  5027.2  329.22  5041.3  329.69  5099.6  329.86  5116.3  329.56
  5153.3  329.76  5160.9  330.01  5188.8  329.62  5205.4  329.91  5274.7  330.11
#Mann= 3 ,-1 , 0
  4536.5      .1       0  4903.6     .07       0  4909.6      .1       0
Bank Sta=4755.2,5041.3
XS Rating Curve= 0 ,0
Exp/Cntr=0.3,0.1

Type RM Length L Ch R = 1 ,4961    ,392,392,392
BEGIN DESCRIPTION:
Mapping XS 777b8b04
END DESCRIPTION:
XS GIS Cut Line= 2
      2082516.51      13423862.4       2081910.1     13423509.96
#Sta/Elev= 30
  4646.4  331.18  4659.7  330.96  4689.8  331.15  4711.3  330.54  4727.1  330.63
  4748.6  330.02  4785.8  329.86  4807.3  329.32  4813.1  329.44  4821.6  329.19
 4827.99328.6473  4856.3  328.02  4893.4  328.41  4930.7  327.99  4946.4  328.15
  4952.2  327.82  4980.6  327.38  4981.1  326.58  4986.1  326.58  4986.6  327.38
  5005.2  328.13  5069.7  328.08  5099.2  328.78 5123.12328.6472  5128.5     329
  5165.7  329.52  5208.8  329.28  5273.3  329.46  5332.1  330.31  5347.8  329.84
#Mann= 3 ,-1 , 0
  4646.4      .1       0  4980.6     .07       0  4986.6      .1       0
Bank Sta=4827.99,5123.12
XS Rating Curve= 0 ,0
Exp/Cntr=0.3,0.1

Type RM Length L Ch R = 1 ,4569    ,416,416,416
BEGIN DESCRIPTION:
Mapping XS 885176ef
END DESCRIPTION:
XS GIS Cut Line= 2
      2082727.43     13423588.95      2082134.65     13423209.37
#Sta/Elev= 30
  4564.9  330.45  4583.6   330.2  4604.7  330.72  4619.9  329.86  4641.1  329.94
  4692.6  328.75    4729  328.83  4793.4  327.79  4822.7326.9841    4838  327.26
  4880.3  326.88  4895.5  327.33  4901.5  326.88  4910.8  326.86  4916.7  326.25
  4931.9  325.98  4934.8  325.52  4935.3  324.72  4940.3  324.72  4940.8  325.52
  4947.1  326.42  4959.6  326.84  5062.5326.9841  5098.5  327.33  5119.6  328.11
  5161.9  328.07  5177.1  328.19  5185.3  328.63  5220.9  328.89  5268.8  328.86
#Mann= 3 ,-1 , 0
  4564.9      .1       0  4934.8     .07       0  4940.8      .1       0
Bank Sta=4822.7,5062.5
XS Rating Curve= 0 ,0
Exp/Cntr=0.3,0.1

Type RM Length L Ch R = 1 ,4153    ,393,393,393
BEGIN DESCRIPTION:
Mapping XS 080b913b
END DESCRIPTION:
XS GIS Cut Line= 2
      2082961.82     13423279.06      2082338.42     13422884.25
#Sta/Elev= 30
  4582.9  328.37  4634.8   328.5  4677.2  327.66  4698.4  327.96  4744.1  327.34
  4765.3  327.61  4771.2  327.25  4815.9  327.18  4844.1  325.89  4865.3  326.09
  4910.6  325.47  4956.8323.3493  4968.7  323.15  4986.9   321.4  4987.4   320.6
  4992.4   320.6  4992.9   321.4  4995.8  322.19 5005.46323.3492  5011.1  323.55
  5017.1  324.84  5026.4  325.17  5076.3  325.85  5111.8  325.81  5141.6  326.79
  5199.2  327.62  5214.5  327.34  5272.1  328.49  5293.3  328.46  5320.8   329.3
#Mann= 3 ,-1 , 0
  4582.9      .1       0  4986.9     .07       0  4992.9      .1       0
Bank Sta=4956.8,5005.46
XS Rating Curve= 0 ,0
Exp/Cntr=0.3,0.1

Type RM Length L Ch R = 1 ,3760    ,370,370,370
BEGIN DESCRIPTION:
UNT 066 in RCW 7.0
END DESCRIPTION:
XS GIS Cut Line= 3
      2083163.21      13423044.7        2083079.     13422945.73
      2082533.46     13422569.05
#Sta/Elev= 30
  4482.3  327.57  4537.3   327.9    4545  327.69  4573.5  328.17  4622.8  327.89
  4643.7  327.38  4702.2  327.32  4715.4   326.9  4801.9  326.24  4873.6  324.53
  4896.6  324.62  4939.1  324.11    4954  322.82  4960.1   322.6 4972.59320.8108
  4986.8  318.76  4987.3  317.96  4992.3  317.96  4992.8  318.76 5007.24320.8114
  5018.1  322.58  5025.7  323.37  5067.6  325.41    5091  325.61  5112.2  326.34
  5176.1  327.39  5198.7  328.26  5234.6  328.18  5240.6  328.57  5275.2  328.95
#Mann= 3 ,-1 , 0
  4482.3      .1       0  4986.8     .07       0  4992.8      .1       0
Bank Sta=4972.59,5007.24
XS Rating Curve= 0 ,0
Exp/Cntr=0.3,0.1

Type RM Length L Ch R = 1 ,3390    ,380,380,380
BEGIN DESCRIPTION:
Mapping XS 08fe9d5d
END DESCRIPTION:
XS GIS Cut Line= 2
      2083406.22     13422742.58      2082738.92     13422296.27
#Sta/Elev= 30
  4435.2  326.67  4606.4  327.19  4657.5  326.75  4678.5  325.94  4809.6   324.4
  4837.6  323.46  4852.6  323.42  4881.8  322.27  4888.7  322.15  4894.7  322.68
  4909.7  322.14  4924.7  320.68  4939.7  320.09  4945.7  320.43  4966.8  319.79
  4981.8  318.04 4982.75317.6384  4987.1   315.8  4987.6     315  4992.6     315
  4993.1   315.8 5002.07317.6371  5011.8  320.03  5032.8  323.48  5047.8  324.12
  5104.9  325.48  5125.9  325.33  5140.9  326.06    5213  326.68    5238  326.48
#Mann= 3 ,-1 , 0
  4435.2      .1       0  4987.1     .07       0  4993.1      .1       0
Bank Sta=4982.75,5002.07
XS Rating Curve= 0 ,0
Exp/Cntr=0.3,0.1

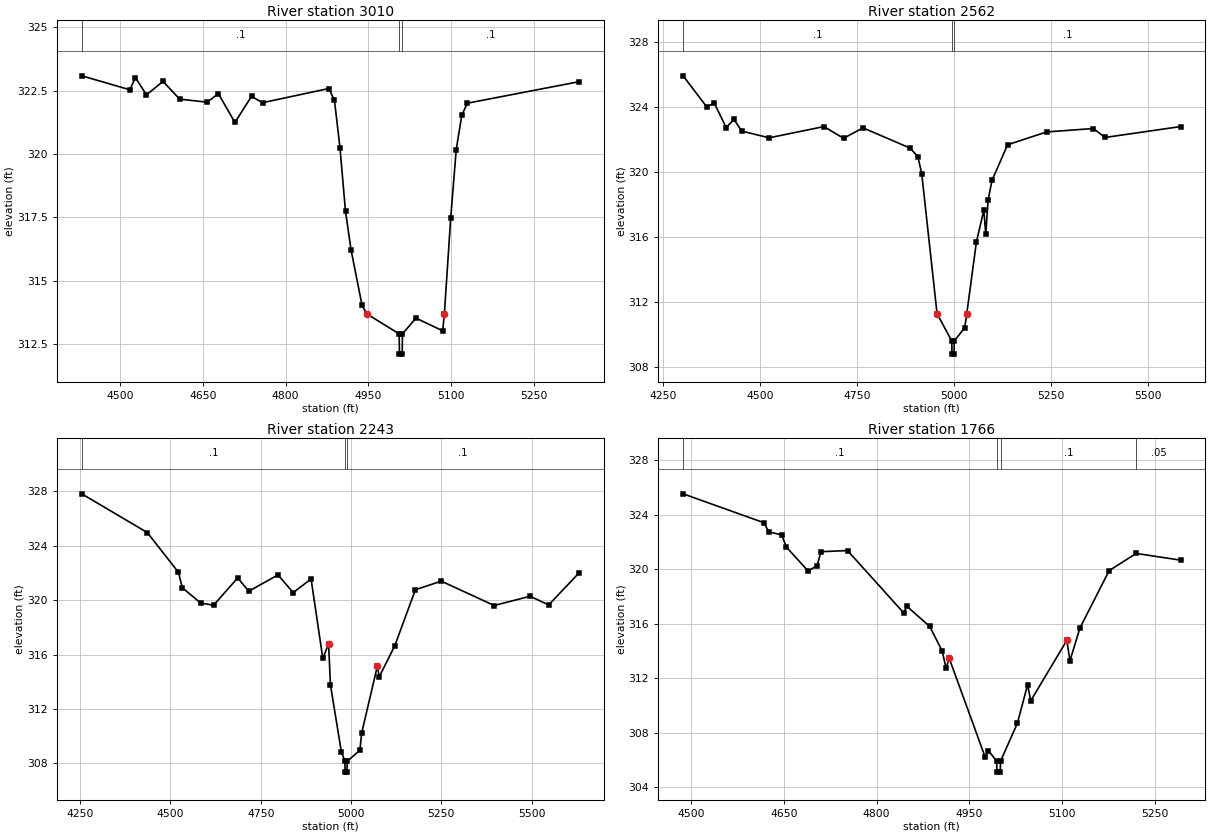
Type RM Length L Ch R = 1 ,3010    ,448,448,448
BEGIN DESCRIPTION:
UNT 066 in RCW 6.0
END DESCRIPTION:
XS GIS Cut Line= 3
      2083631.95     13422161.01        2083025.       13422125.
      2082733.53     13422156.66
#Sta/Elev= 30
  4430.6  323.08  4517.7  322.53  4527.7  323.01  4547.8  322.33  4577.8  322.86
  4607.9  322.16  4657.9  322.04    4678  322.38    4708  321.24  4738.1  322.27
  4758.1  322.02  4878.3  322.58  4888.4  322.11  4898.4  320.24  4908.4  317.73
  4918.4  316.22  4938.4  314.02 4947.03313.6868  5005.6   312.9  5006.1   312.1
  5011.1   312.1  5011.6   312.9  5036.1  313.52  5084.4  313.02 5087.52313.6877
    5099  317.47    5109  320.17  5119.1  321.53  5129.1     322  5331.8  322.85
#Mann= 3 ,-1 , 0
  4430.6      .1       0  5005.6     .07       0  5011.6      .1       0
Bank Sta=4947.03,5087.52
XS Rating Curve= 0 ,0
Exp/Cntr=0.3,0.1

Type RM Length L Ch R = 1 ,2562    ,319,319,319
BEGIN DESCRIPTION:
UNT 066 in RCW 5.0
END DESCRIPTION:
XS GIS Cut Line= 3
      2083725.05     13421875.01      2083041.67     13421792.08
      2082451.25     13421844.09
#Sta/Elev= 30
  4302.6  325.92  4363.1  324.02  4383.2  324.23  4413.5  322.74  4433.6  323.24
  4453.7  322.52  4524.3  322.11  4665.3   322.8  4715.7  322.08    4766  322.72
  4886.9  321.48    4907  320.96  4917.1  319.91 4956.56311.3037  4994.5  309.61
    4995  308.81  5000.3  308.81  5000.8  309.61  5027.8  310.44  5033.2311.3041
  5057.9   315.7  5077.1  317.66  5082.1  316.17    5088  318.28  5098.1  319.49
  5138.2  321.68  5238.6  322.47  5359.1  322.68  5389.2  322.13  5583.7   322.8
#Mann= 3 ,-1 , 0
  4302.6      .1       0  4994.5     .07       0  5000.8      .1       0
Bank Sta=4956.56,5033.2
XS Rating Curve= 0 ,0
Exp/Cntr=0.3,0.1

Type RM Length L Ch R = 1 ,2243    ,477,477,477
BEGIN DESCRIPTION:
Mapping XS d30a58bd
END DESCRIPTION:
XS GIS Cut Line= 2
      2083956.19       13421740.      2082612.43     13421437.92
#Sta/Elev= 30
  4254.5  327.82    4436  324.97  4522.2  322.05  4532.8  320.92  4583.7  319.79
  4619.4  319.63  4686.2  321.64    4717  320.66  4797.7  321.86  4839.9  320.56
  4889.4  321.56  4921.9  315.72  4937.9  316.79    4943  313.78  4973.2  308.86
  4983.1  308.16  4983.6  307.36  4988.9  307.36  4989.4  308.16  5024.4  308.96
  5029.6  310.25  5072.9  315.15    5078  314.36  5121.3  316.66  5178.2  320.77
  5249.9   321.4  5396.4  319.61  5495.9  320.29  5547.2  319.65  5631.8  322.02
#Mann= 3 ,-1 , 0
  4254.5      .1       0  4983.1     .07       0  4989.4      .1       0
Bank Sta=4937.9,5072.9
XS Rating Curve= 0 ,0
Exp/Cntr=0.3,0.1

Type RM Length L Ch R = 1 ,1766    ,0,0,0
BEGIN DESCRIPTION:
Mapping XS 55acd761
END DESCRIPTION:
XS GIS Cut Line= 3
      2083813.79     13421351.09      2083560.34     13421135.83
       2083094.2     13421207.19
#Sta/Elev= 30
  4487.3  325.52    4618   323.4  4625.7  322.74  4646.6   322.5  4654.3  321.61
  4689.4  319.86  4703.7  320.25  4710.3  321.28  4753.1  321.36  4843.9  316.79
  4848.9  317.28  4885.9   315.8  4906.2  313.99  4912.3  312.73  4917.4  313.47
  4975.7   306.2  4980.8   306.7  4994.1  305.92  4994.6  305.12  4999.9  305.12
  5000.4  305.92  5027.6   308.7  5044.2  311.53  5049.2  310.35  5107.6  314.78
  5112.6  313.28  5128.7  315.68    5176  319.89  5219.7  321.15  5291.4  320.66
#Mann= 4 ,-1 , 0
  4487.3      .1       0  4994.1     .07       0  5000.4      .1       0
  5219.7     .05       0
Bank Sta=4917.4,5107.6
XS Rating Curve= 0 ,0
Exp/Cntr=0.3,0.1
LCMann Table=0

Chan Stop Cuts=-1
Use User Specified Reach Order=0
Composite Channel Slope=5