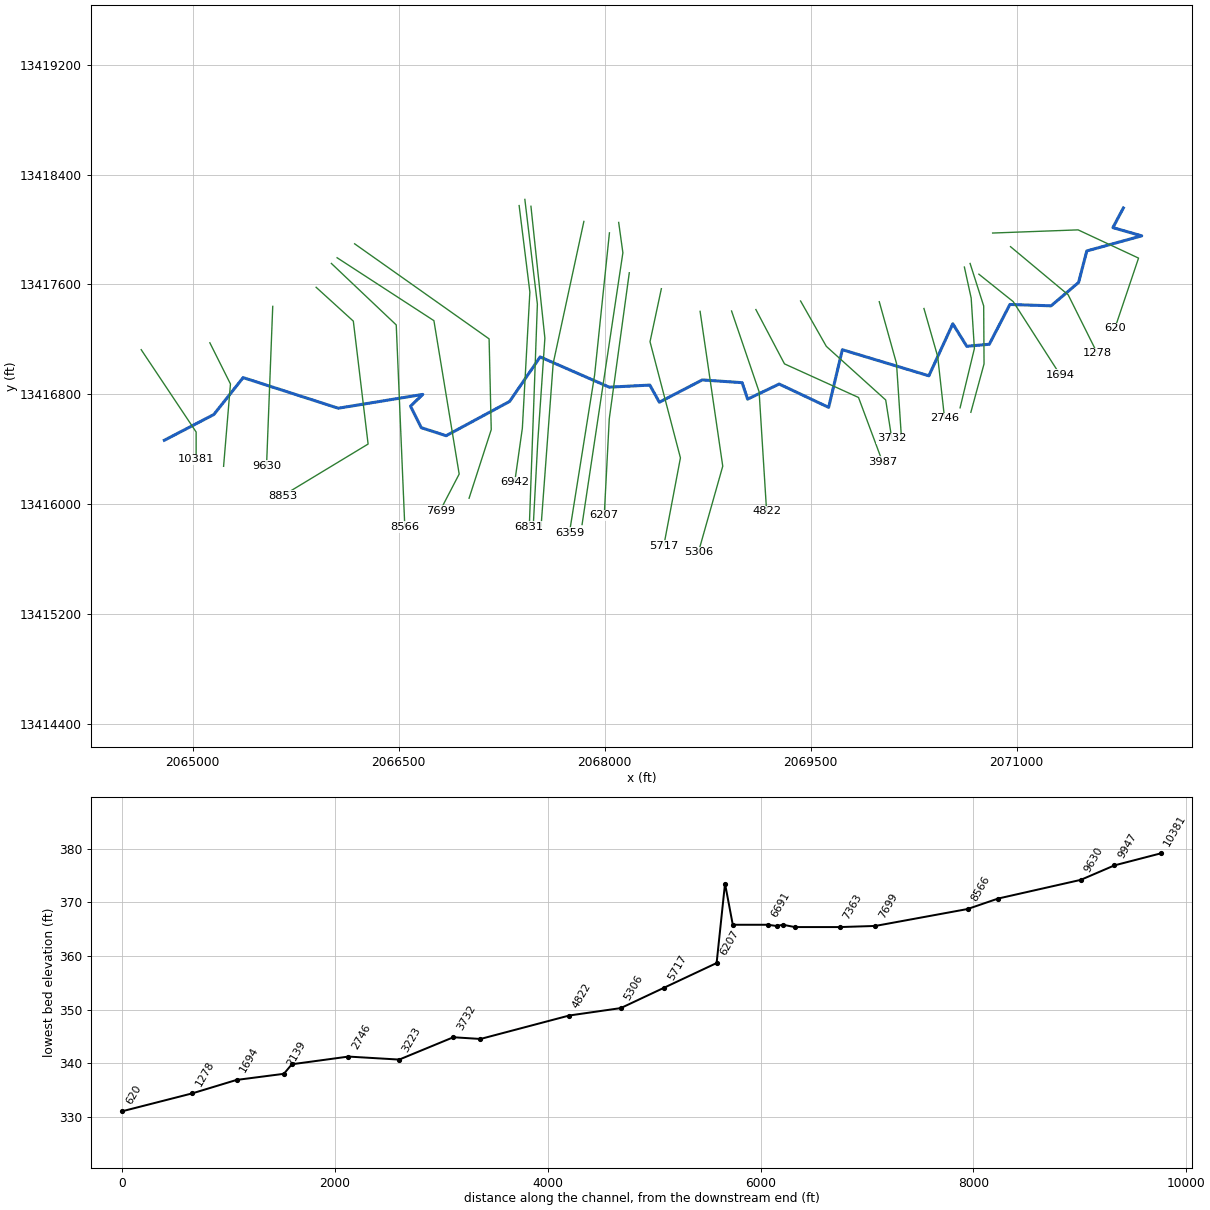
--- UNT 067 in RCW.prj (project) ---

Proj Title=UNT 067 in RCW Base Level Engineering
Current Plan=p01
Default Exp/Contr=0.3,0.1
English Units
Geom File=g01
Flow File=f01
Plan File=p01
Y Axis Title=Elevation
X Axis Title(PF)=Main Channel Distance
X Axis Title(XS)=Station
BEGIN DESCRIPTION:
UNT 067 in RCW
END DESCRIPTION:
DSS Export Rating Curves= 0
DSS Export Rating Curve Sorted= 0
DSS Export Volume Flow Curves= 0
DXF OffsetX= 0
DXF OffsetY= 0
DXF ScaleX= 1
DXF ScaleY= 10

--- UNT 067 in RCW.p01 (plan) ---

Plan Title=Multiple Run
Short Identifier=Multiple
Geom File=g01
Flow File=f01
Subcritical Flow
K Sum by GR= 0
Std Step Tol= 0.01
Critical Tol= 0.01
Num of Std Step Trials= 20
Max Error Tol= 0.3
Flow Tol Ratio= 0.001
Split Flow NTrial= 30
Split Flow Tol= 0.02
Split Flow Ratio= 0.02
Log Output Level= 0
Friction Slope Method= 1
Unsteady Friction Slope Method= 2
Unsteady Bridges Friction Slope Method= 1
Parabolic Critical Depth
Global Vel Dist=  1 , 1 , 1
Global Log Level= 0
CheckData=True
Encroach Param= -1, 0, 0, 0
BEGIN DESCRIPTION:
Multiple Run
END DESCRIPTION:

--- UNT 067 in RCW.f01 (steady flow) ---

Flow Title=Multiple
Number of Profiles=7
Profile Names=10-year,25-year,50-year,1pct_min,100-year,1pct_plu,500-year
River Rch & RM= UNT 067 in RCW,Reach-1,10381
     171     234     285     173     345     689     517
River Rch & RM= UNT 067 in RCW,Reach-1,7699
     274     383     475     293     585    1166     901
River Rch & RM= UNT 067 in RCW,Reach-1,3732
     292     410     508     314     626    1248     965
Boundary for River Rch & Prof#=UNT 067 in RCW,Reach-1,1
Up Type=0
Dn Type=3
Dn Slope=0.005
Boundary for River Rch & Prof#=UNT 067 in RCW,Reach-1,2
Up Type=0
Dn Type=3
Dn Slope=0.005
Boundary for River Rch & Prof#=UNT 067 in RCW,Reach-1,3
Up Type=0
Dn Type=3
Dn Slope=0.005
Boundary for River Rch & Prof#=UNT 067 in RCW,Reach-1,4
Up Type=0
Dn Type=3
Dn Slope=0.005
Boundary for River Rch & Prof#=UNT 067 in RCW,Reach-1,5
Up Type=0
Dn Type=3
Dn Slope=0.005
Boundary for River Rch & Prof#=UNT 067 in RCW,Reach-1,6
Up Type=0
Dn Type=3
Dn Slope=0.005
Boundary for River Rch & Prof#=UNT 067 in RCW,Reach-1,7
Up Type=0
Dn Type=3
Dn Slope=0.005

--- UNT 067 in RCW.g01 (geometry) ---

Geom Title=Existing Conditions
Program Version=5.05

River Reach=UNT 067 in RCW  ,Reach-1
Reach XY= 30
      2064793.61     13416464.82      2065153.85     13416652.32
      2065367.39     13416921.42       2066060.1     13416698.33
      2066675.55     13416799.02      2066586.14     13416713.09
      2066664.16     13416556.62      2066845.36     13416498.03
       2067307.6     13416747.59      2067530.04     13417072.03
      2068033.51     13416851.76      2068328.65     13416866.95
       2068398.1     13416742.17       2068710.8     13416904.54
       2069000.8     13416884.54       2069040.8     13416764.54
       2069270.8     13416874.54       2069630.8     13416704.54
       2069730.8     13417124.54       2070360.8     13416934.54
      2070535.06     13417313.77      2070636.62     13417149.71
       2070800.8     13417164.54       2070950.8     13417454.54
       2071250.8     13417444.54       2071450.8     13417614.54
       2071510.8     13417844.54       2071910.8     13417954.54
       2071700.8     13418014.54      2071777.01     13418157.56

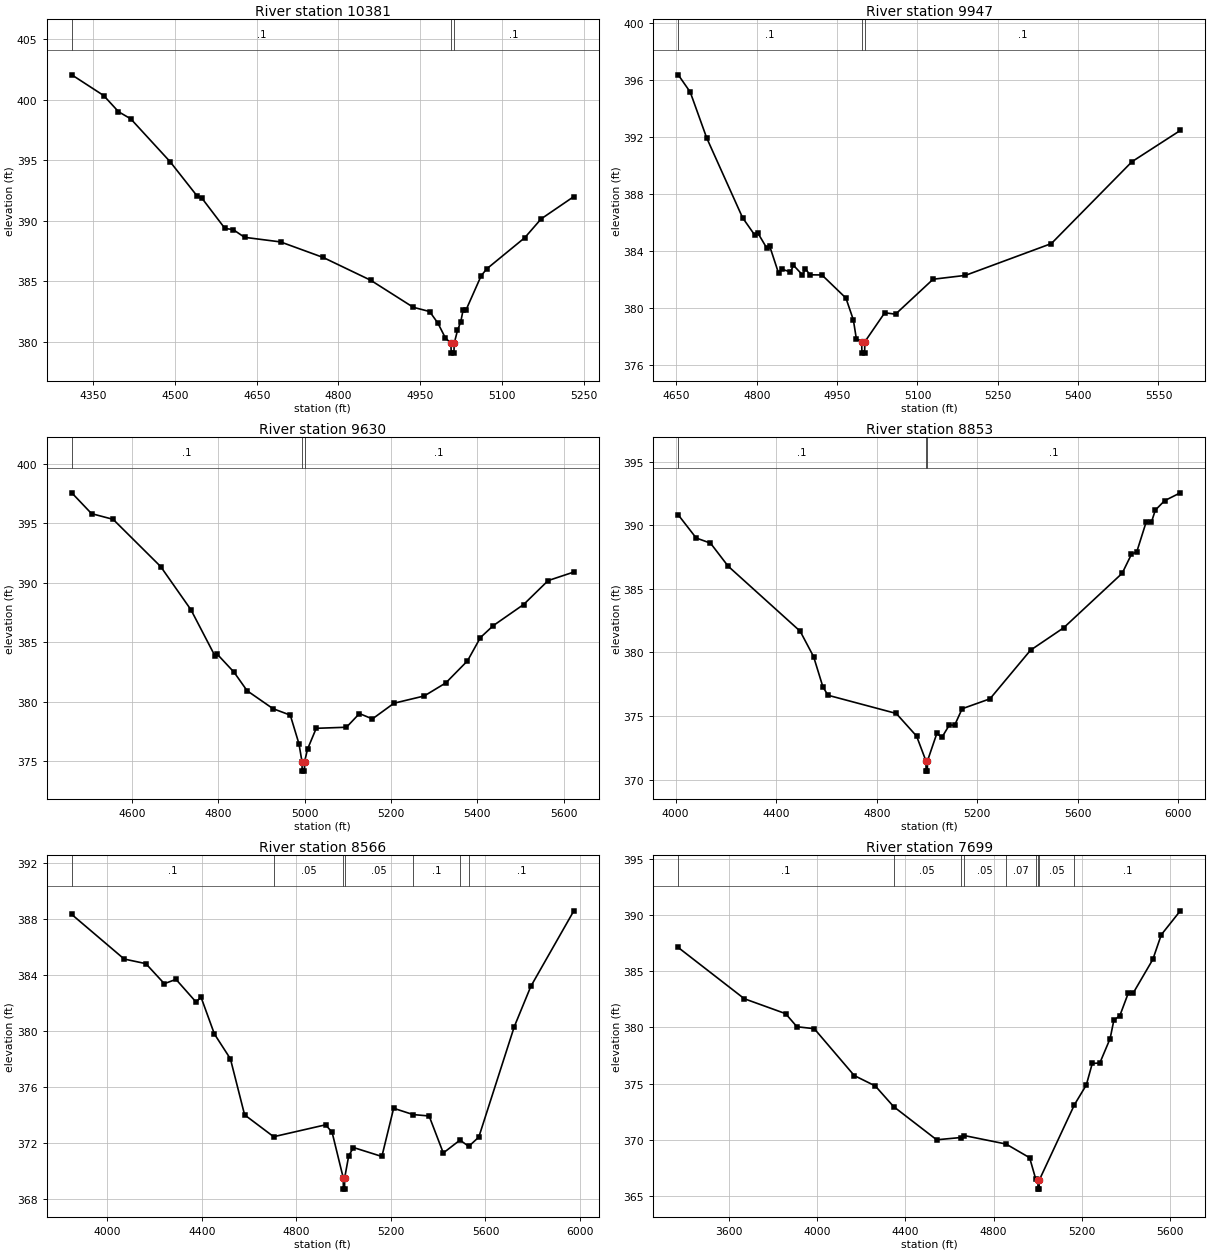
Type RM Length L Ch R = 1 ,10381   ,434,434,434
BEGIN DESCRIPTION:
UNT 067 in RCW 18.0
END DESCRIPTION:
XS GIS Cut Line= 3
      2064624.98     13417125.02        2065025.       13416525.
        2065025.     13416325.04
#Sta/Elev= 30
  4310.7  402.04  4369.3  400.33  4396.4     399  4418.9  398.41    4491  394.88
  4540.6  392.05  4549.6  391.86  4591.7  389.37  4606.7  389.28  4627.7  388.64
  4693.8  388.26  4771.9  386.98  4859.1   385.1  4937.2  382.87  4967.2  382.52
  4982.3  381.57  4995.8  380.37  5006.3  379.89  5006.8  379.09  5011.8  379.09
  5012.3  379.89  5018.3  380.96  5024.3  381.67  5028.8  382.68  5034.3  382.68
  5061.8  385.47  5071.8  386.03  5141.8  388.61  5171.8  390.16  5231.8     392
#Mann= 3 ,-1 , 0
  4310.7      .1       0  5006.3     .07       0  5012.3      .1       0
Bank Sta=5006.3,5012.3
XS Rating Curve= 0 ,0
Exp/Cntr=0.3,0.1

Type RM Length L Ch R = 1 ,9947    ,317,317,317
BEGIN DESCRIPTION:
UNT 067 in RCW 17.0
END DESCRIPTION:
XS GIS Cut Line= 3
      2065124.99     13417175.01        2065275.       13416875.
        2065225.       13416275.
#Sta/Elev= 30
  4653.3  396.37  4675.7  395.16  4706.4  391.95  4773.5  386.35  4795.9  385.15
  4801.5  385.31  4818.2  384.25  4823.8  384.39  4840.6  382.47  4846.2  382.75
  4862.9  382.55  4868.5  383.02  4885.3  382.34  4890.9  382.77  4899.3  382.35
  4921.6  382.34  4966.4  380.72  4980.3  379.19  4985.9  377.86  4995.8  377.66
  4996.3  376.86  5001.3  376.86  5001.8  377.66  5038.9  379.69    5059  379.59
  5129.2  382.04  5189.4  382.31    5350  384.54  5500.5  390.28  5590.8  392.47
#Mann= 3 ,-1 , 0
  4653.3      .1       0  4995.8     .07       0  5001.8      .1       0
Bank Sta=4995.8,5001.8
XS Rating Curve= 0 ,0
Exp/Cntr=0.3,0.1

Type RM Length L Ch R = 1 ,9630    ,777,777,777
BEGIN DESCRIPTION:
Mapping XS 4eca6361
END DESCRIPTION:
XS GIS Cut Line= 2
      2065582.85     13417440.76      2065537.76     13416278.74
#Sta/Elev= 30
  4460.6  397.56  4506.4  395.81  4556.4  395.33  4666.5  391.36  4736.6  387.73
  4791.8  383.88  4796.8  384.02  4836.6  382.47  4866.7  380.92  4926.7  379.41
  4966.7  378.87  4986.8  376.46  4993.8  374.96  4994.3  374.16  4999.3  374.16
  4999.8  374.96  5006.8  376.02  5026.8  377.76  5096.8  377.85  5126.9     379
  5156.9  378.55  5206.9  379.87    5277  380.48    5327  381.58  5377.1  383.43
  5407.1  385.39  5437.1   386.4  5507.2  388.17  5563.9  390.18  5623.5   390.9
#Mann= 3 ,-1 , 0
  4460.6      .1       0  4993.8     .07       0  4999.8      .1       0
Bank Sta=4993.8,4999.8
XS Rating Curve= 0 ,0
Exp/Cntr=0.3,0.1

Type RM Length L Ch R = 1 ,8853    ,287,287,287
BEGIN DESCRIPTION:
Mapping XS b46f2f89
END DESCRIPTION:
XS GIS Cut Line= 4
      2065898.82     13417579.64      2066169.65     13417333.11
      2066277.29     13416437.28       2065653.3     13416059.42
#Sta/Elev= 30
  4010.2  390.81  4081.7  388.99  4138.4  388.59  4208.7  386.78  4495.4  381.67
  4548.9  379.67    4586  377.29  4606.2  376.64  4877.7  375.21  4958.7  373.43
    4996  371.48  4996.5  370.68  5001.5  370.68    5002  371.48  5039.3  373.64
  5059.4  373.33  5089.6  374.32  5109.8  374.27    5140  375.58  5250.8  376.36
  5412.2  380.18  5544.1  381.94  5776.8  386.22  5813.7  387.71    5835  387.91
  5871.9  390.22  5893.2  390.23  5908.7  391.18  5945.5  391.92  6008.2  392.54
#Mann= 3 ,-1 , 0
  4010.2      .1       0    4996     .07       0    5002      .1       0
Bank Sta=4996,5002
XS Rating Curve= 0 ,0
Exp/Cntr=0.3,0.1

Type RM Length L Ch R = 1 ,8566    ,867,867,867
BEGIN DESCRIPTION:
Mapping XS 6194f4d0
END DESCRIPTION:
XS GIS Cut Line= 3
      2066009.92     13417753.26      2066482.15     13417305.34
      2066544.65     13415833.14
#Sta/Elev= 30
  3849.6  388.33  4071.3  385.15  4163.1  384.82  4241.2  383.39  4290.5   383.7
  4375.5  382.08  4396.5  382.43  4453.1   379.8  4520.8  378.03  4580.9  374.03
  4703.8  372.47  4923.7  373.32  4951.2  372.78  4998.3  369.53  4998.8  368.73
  5003.8  368.73  5004.3  369.53  5021.3   371.1  5041.3   371.7  5161.7  371.06
  5211.5   374.5  5293.9  374.05  5361.6  373.95  5421.6  371.31  5492.3  372.23
  5529.1  371.78  5571.8  372.44  5721.9  380.32    5792   383.2    5974  388.59
#Mann= 7 ,-1 , 0
  3849.6      .1       0  4703.8     .05       0  4998.3    .035       0
  5004.3     .05       0  5293.9      .1       0  5492.3     .05       0
  5529.1      .1       0
Bank Sta=4998.3,5004.3
XS Rating Curve= 0 ,0
Exp/Cntr=0.3,0.1

Type RM Length L Ch R = 1 ,7699    ,336,336,336
BEGIN DESCRIPTION:
Mapping XS 683368bc
END DESCRIPTION:
XS GIS Cut Line= 4
      2066051.64     13417794.89      2066756.46     13417336.59
      2066940.49     13416218.53       2066801.6     13415951.18
#Sta/Elev= 30
  3371.3  387.13  3670.7  382.56  3857.8  381.23  3909.2  380.06  3987.6  379.89
  4168.8  375.71  4264.3  374.78  4347.2  372.94  4542.3  369.98  4650.7  370.18
  4666.8  370.36    4857   369.6  4963.6  368.38  4991.8  366.44    5001  366.38
  5001.5  365.58  5006.7  365.58  5007.2  366.38  5166.7  373.11  5220.5  374.87
  5247.4  376.79  5281.7  376.83  5328.4  379.01  5345.1  380.63  5372.6  381.06
  5411.2  383.09  5433.3  383.08  5521.7  386.06  5560.3  388.27  5646.4   390.4
#Mann= 9 ,-1 , 0
  3371.3      .1       0  4347.2     .05       0  4650.7     .07       0
  4666.8     .05       0    4857     .07       0  4991.8     .05       0
    5001    .035       0  5007.2     .05       0  5166.7      .1       0
Bank Sta=5001,5007.2
XS Rating Curve= 0 ,0
Exp/Cntr=0.3,0.1

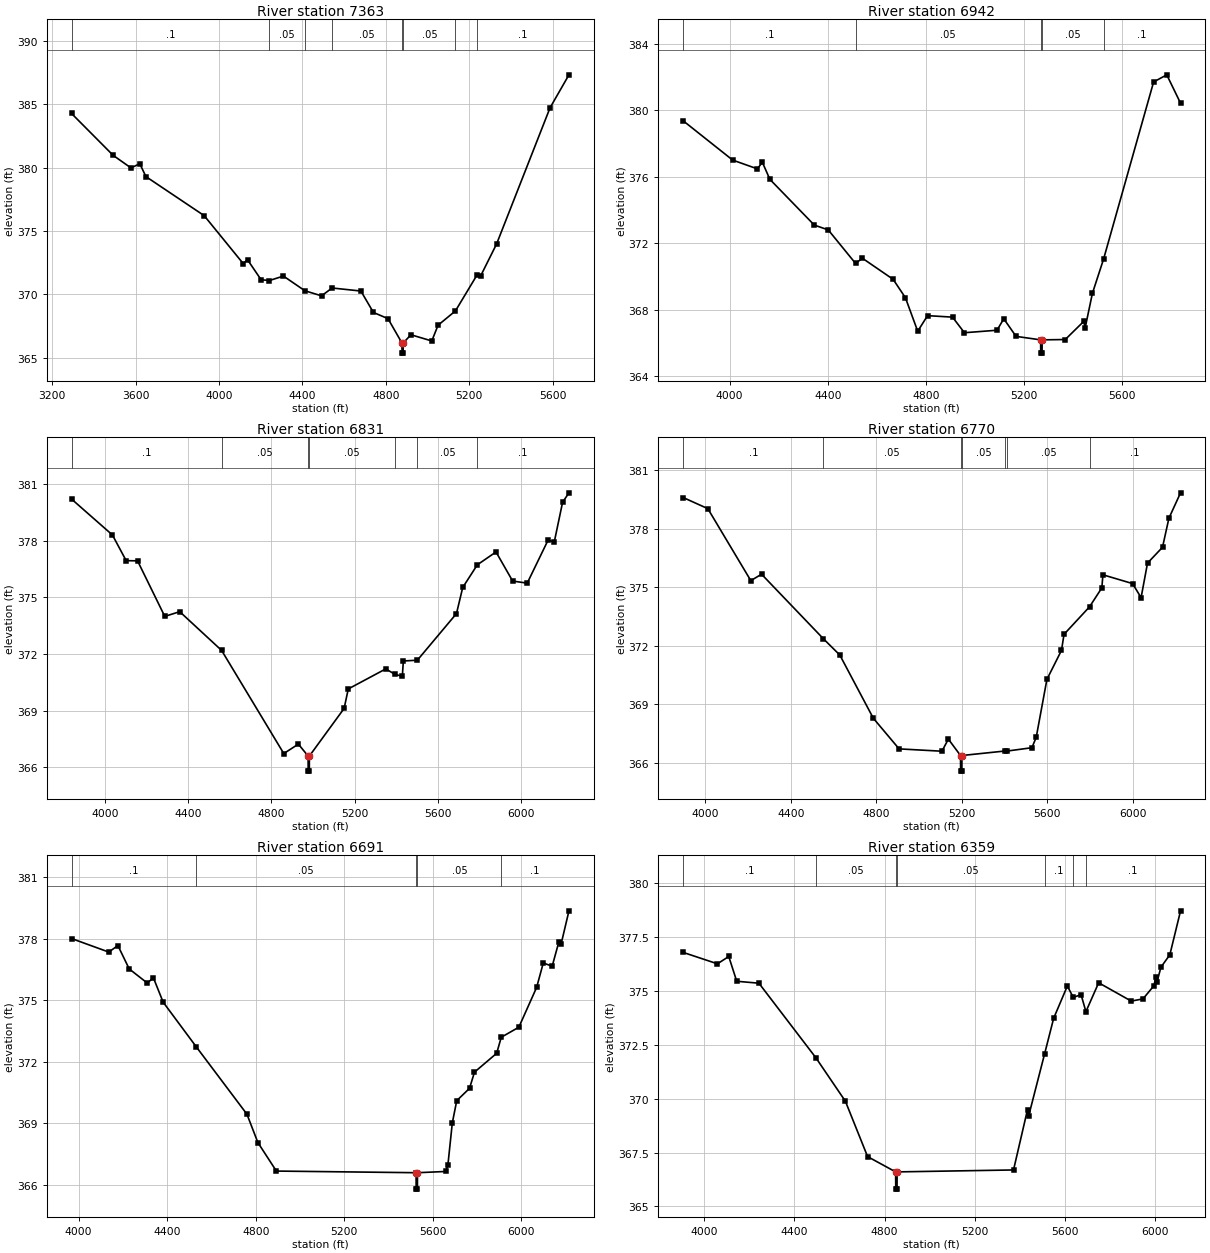
Type RM Length L Ch R = 1 ,7363    ,421,421,421
BEGIN DESCRIPTION:
UNT 067 in RCW 13.0
END DESCRIPTION:
XS GIS Cut Line= 4
      2066179.18      13417896.5      2067158.37     13417203.77
      2067173.99     13416542.31      2067012.54     13416042.33
#Sta/Elev= 30
  3292.4  384.28  3491.8  380.98  3577.9  379.98  3619.7  380.32  3649.3   379.3
  3928.7  376.22  4115.8  372.44  4136.7  372.74  4201.9  371.16  4241.9   371.1
    4309  371.45  4412.2  370.29  4491.9  369.89  4542.5  370.51  4680.7  370.27
  4740.7  368.58  4810.7  368.09  4877.6  366.17  4878.1  365.37  4883.3  365.37
  4883.8  366.17  4920.7  366.82  5020.8  366.33  5050.8  367.57  5134.2   368.7
  5237.7  371.53  5255.8  371.48  5331.9  373.99  5588.2  384.73  5678.9  387.33
#Mann= 8 ,-1 , 0
  3292.4      .1       0  4241.9     .05       0  4412.2      .1       0
  4542.5     .05       0  4877.6    .033       0  4883.8     .05       0
  5134.2     .07       0  5237.7      .1       0
Bank Sta=4877.6,4883.8
XS Rating Curve= 0 ,0
Exp/Cntr=0.3,0.1

Type RM Length L Ch R = 1 ,6942    ,111,111,111
BEGIN DESCRIPTION:
Mapping XS 7ff841cb
END DESCRIPTION:
XS GIS Cut Line= 4
      2067377.12     13418175.13      2067455.24     13417544.92
      2067400.56     13416552.73      2067344.88     13416159.48
#Sta/Elev= 30
    3811  379.38  4012.7  377.01  4113.4  376.48  4133.6  376.88  4164.2  375.85
  4345.2  373.09    4402   372.8  4513.2  370.78  4541.2  371.09  4666.3  369.82
  4716.4  368.71  4766.4  366.69  4806.5  367.63  4908.2  367.54  4956.7   366.6
  5089.2  366.75    5117  367.44    5167  366.38    5267  366.17  5267.5  365.37
  5272.8  365.37  5273.3  366.17  5367.3  366.19  5443.1  367.29  5448.1  366.87
  5477.8  368.97  5523.6  371.05  5727.2  381.72  5780.8  382.15  5836.9  380.44
#Mann= 5 ,-1 , 0
    3811      .1       0  4513.2     .05       0    5267    .033       0
  5273.3     .05       0  5523.6      .1       0
Bank Sta=5267,5273.3
XS Rating Curve= 0 ,0
Exp/Cntr=0.3,0.1

Type RM Length L Ch R = 1 ,6831    ,61,61,61
BEGIN DESCRIPTION:
UNT 067 in RCW 12.0
END DESCRIPTION:
XS GIS Cut Line= 3
      2067418.79     13418220.23      2067509.93     13417456.38
      2067451.14     13415834.41
#Sta/Elev= 30
  3838.9   380.2  4035.5   378.3  4101.6  376.94  4156.4  376.93  4287.3  373.99
  4359.2  374.24  4560.6  372.19  4859.7  366.73  4929.8  367.23  4976.6   366.6
  4977.1   365.8  4982.4   365.8  4982.9   366.6  5149.9  369.12  5169.9  370.15
    5350  371.21  5395.2  370.92  5429.8  370.82  5434.8  371.63    5502  371.67
  5690.3  374.14  5720.3  375.52  5790.5  376.72  5880.4   377.4  5960.4  375.86
  6030.5  375.75  6130.5  378.02  6160.6  377.93  6200.6  380.03  6231.2  380.53
#Mann= 7 ,-1 , 0
  3838.9      .1       0  4560.6     .05       0  4976.6    .033       0
  4982.9     .05       0  5395.2     .12       0    5502     .05       0
  5790.5      .1       0
Bank Sta=4976.6,4982.9
XS Rating Curve= 0 ,0
Exp/Cntr=0.3,0.1

Type RM Length L Ch R = 1 ,6770    ,79,79,79
BEGIN DESCRIPTION:
Mapping XS 1ddb6ea0
END DESCRIPTION:
XS GIS Cut Line= 4
      2067463.06     13418169.91      2067564.62     13417208.98
      2067512.54     13416451.17      2067480.43      13415850.7
#Sta/Elev= 30
  3895.9  379.59  4011.4  379.02  4212.6  375.33  4262.8  375.66  4552.3  372.35
  4628.9  371.52  4785.7  368.28  4906.3  366.71  5106.7  366.59  5136.8  367.21
  5193.7  366.37  5194.2  365.57  5199.7  365.57  5200.2  366.37  5401.1   366.6
  5412.7   366.6  5527.7  366.77  5547.8   367.3  5597.9  370.27  5666.1  371.76
    5678  372.58  5797.3  373.99  5854.9  374.96  5859.9  375.63  5998.5  375.18
  6038.5  374.46  6068.6  376.23  6138.7  377.04  6168.7  378.53  6223.1  379.83
#Mann= 7 ,-1 , 0
  3895.9      .1       0  4552.3     .05       0  5193.7    .033       0
  5200.2     .05       0  5401.1     .12       0  5412.7     .05       0
  5797.3      .1       0
Bank Sta=5193.7,5200.2
XS Rating Curve= 0 ,0
Exp/Cntr=0.3,0.1

Type RM Length L Ch R = 1 ,6691    ,332,332,332
BEGIN DESCRIPTION:
UNT 067 in RCW 11.0
END DESCRIPTION:
XS GIS Cut Line= 3
      2067848.47     13418059.64        2067625.       13417025.
       2067536.9     13415839.36
#Sta/Elev= 30
  3967.9  378.01  4136.3  377.35  4177.3  377.67  4228.4  376.53  4310.3  375.84
  4337.7   376.1  4381.8  374.91  4532.4  372.72  4760.4  369.45  4809.8  368.07
  4893.4  366.68  5524.5   366.6    5525   365.8  5530.5   365.8    5531   366.6
  5658.1  366.66  5668.2  366.96  5688.2  369.02  5708.3  370.11    5766  370.71
  5788.5   371.5  5888.8  372.42  5909.4   373.2    5989  373.69  6069.3  375.63
  6099.3  376.82  6139.5  376.66    6169  377.82  6179.6  377.73  6215.3  379.36
#Mann= 5 ,-1 , 0
  3967.9      .1       0  4532.4     .05       0  5524.5    .033       0
    5531     .05       0  5909.4      .1       0
Bank Sta=5524.5,5531
XS Rating Curve= 0 ,0
Exp/Cntr=0.3,0.1

Type RM Length L Ch R = 1 ,6359    ,73,73,73
BEGIN DESCRIPTION:
UNT 067 in RCW 10.0
END DESCRIPTION:
XS GIS Cut Line= 3
      2068034.69     13417976.42       2067926.6     13416939.88
      2067743.19     13415788.86
#Sta/Elev= 30
  3905.9  376.79  4058.1  376.26  4108.4   376.6  4143.8  375.45  4242.3  375.36
    4495   371.9  4626.1  369.88  4724.6  367.31  4849.1   366.6  4849.6   365.8
  4855.2   365.8  4855.7   366.6  5372.3  366.69  5434.4  369.49  5439.5   369.2
    5510  372.07  5550.4  373.73  5611.2  375.23  5637.5   374.7    5672  374.83
  5693.6  374.04  5750.2  375.38  5894.7  374.53  5946.8  374.63    5996  375.25
  6003.9  375.67    6009  375.41  6026.4   376.1  6066.1  376.68  6113.6  378.72
#Mann= 7 ,-1 , 0
  3905.9      .1       0    4495     .05       0  4849.1    .035       0
  4855.7     .05       0    5510      .1       0  5637.5     .05       0
  5693.6      .1       0
Bank Sta=4849.1,4855.7
XS Rating Curve= 0 ,0
Exp/Cntr=0.3,0.1

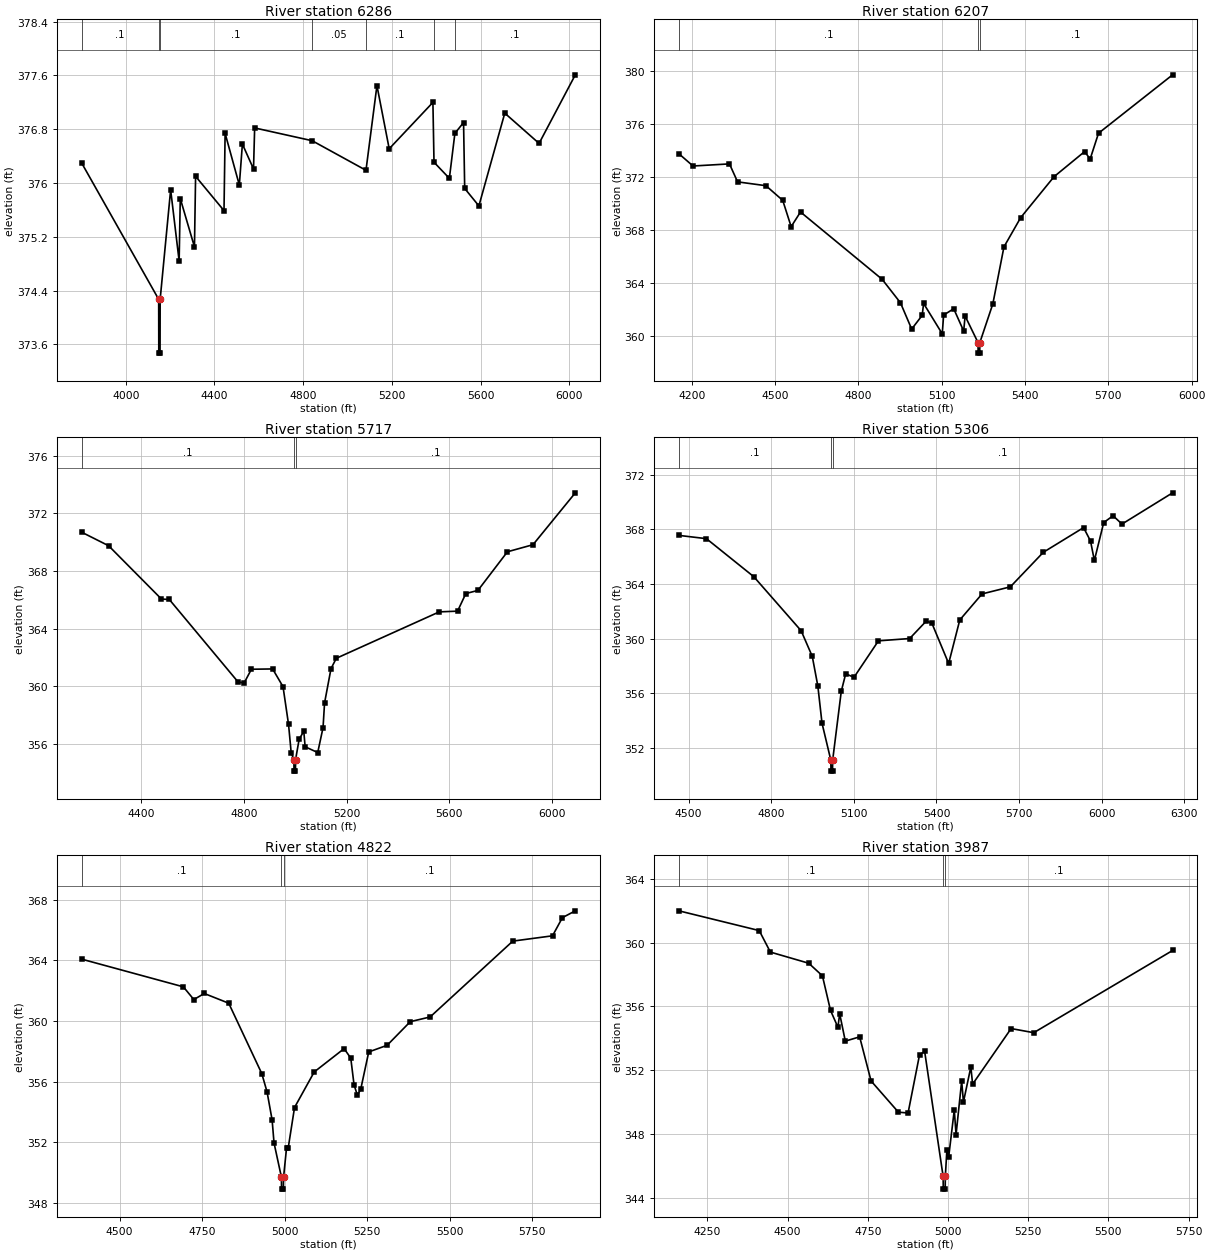
Type RM Length L Ch R = 1 ,6286    ,79,79,79
BEGIN DESCRIPTION:
Mapping XS 02aa45d4
END DESCRIPTION:
XS GIS Cut Line= 3
      2068101.96     13418052.37      2068132.57     13417831.28
      2067835.45     13415850.44
#Sta/Elev= 30
  3801.1   376.3  4148.7  374.27  4149.2  373.47  4154.8  373.47  4155.3  374.27
  4202.6   375.9  4240.9  374.84    4246  375.77    4310  375.05  4315.1   376.1
  4443.2  375.59  4448.2  376.74  4512.3  375.97  4526.1  376.58  4576.3  376.21
  4581.4  376.82  4840.6  376.63  5083.4  376.19  5132.8  377.45  5188.1  376.51
  5385.2   377.2  5390.1  376.31  5459.4  376.07  5484.3  376.74  5523.4   376.9
  5528.5  375.92  5592.5  375.66  5709.2  377.04  5863.9  376.59  6027.3  377.61
#Mann= 7 ,-1 , 0
  3801.1      .1       0  4148.7    .035       0  4155.3      .1       0
  4840.6     .05       0  5083.4      .1       0  5390.1     .05       0
  5484.3      .1       0
Bank Sta=4148.7,4155.3
XS Rating Curve= 0 ,0
Exp/Cntr=0.3,0.1

Type RM Length L Ch R = 1 ,6207    ,490,490,490
BEGIN DESCRIPTION:
UNT 067 in RCW 9.0
END DESCRIPTION:
XS GIS Cut Line= 3
      2068179.21     13417685.56      2068033.37     13416620.44
      2067996.98     13415918.64
#Sta/Elev= 30
  4153.5  373.76  4204.5  372.83  4335.7  372.99  4364.9  371.63    4467  371.34
  4527.5  370.23  4557.8  368.24  4591.5  369.35  4885.3  364.26  4951.4  362.48
  4991.8  360.49  5029.7  361.53  5034.7  362.43  5101.9  360.13  5106.9  361.55
  5143.2  362.03  5179.1  360.34  5184.2  361.48  5230.7  359.47  5231.2  358.67
  5236.8  358.67  5237.3  359.47  5284.1   362.4  5324.1  366.71  5384.2  368.92
  5504.4  372.02  5614.5  373.92  5634.5  373.36  5664.6  375.31  5931.3  379.73
#Mann= 3 ,-1 , 0
  4153.5      .1       0  5230.7     .07       0  5237.3      .1       0
Bank Sta=5230.7,5237.3
XS Rating Curve= 0 ,0
Exp/Cntr=0.3,0.1

Type RM Length L Ch R = 1 ,5717    ,411,411,411
BEGIN DESCRIPTION:
Mapping XS 2e668fe1
END DESCRIPTION:
XS GIS Cut Line= 4
      2068412.71     13417569.22      2068330.24     13417182.94
       2068551.6     13416336.59      2068430.06     13415694.18
#Sta/Elev= 30
  4167.9  370.69    4273  369.75    4479  366.05  4509.6  366.02  4777.8  360.29
  4801.3  360.23  4829.5  361.18  4912.2   361.2  4952.7  359.97  4974.2  357.35
  4984.5  355.38    4995  354.91  4995.5  354.11  5001.1  354.11  5001.6  354.91
  5015.5  356.32  5033.6  356.88  5038.8   355.8  5087.9   355.4  5108.6  357.13
  5114.5  358.84  5139.6  361.22  5160.3  361.94  5561.4  365.16  5632.7  365.21
  5664.9  366.43  5712.1  366.65    5827  369.33  5926.6  369.82  6091.5  373.42
#Mann= 3 ,-1 , 0
  4167.9      .1       0    4995     .07       0  5001.6      .1       0
Bank Sta=4995,5001.6
XS Rating Curve= 0 ,0
Exp/Cntr=0.3,0.1

Type RM Length L Ch R = 1 ,5306    ,484,484,484
BEGIN DESCRIPTION:
Mapping XS 943adc36
END DESCRIPTION:
XS GIS Cut Line= 3
      2068694.83     13417404.31      2068859.76     13416275.82
      2068682.29     13415648.21
#Sta/Elev= 30
  4464.6  367.56  4564.7  367.32  4736.8  364.53  4908.6  360.57    4949  358.69
  4969.2  356.52  4984.4  353.79  5016.4  351.08  5016.9  350.28  5022.5  350.28
    5023  351.08  5054.3  356.13  5070.3  357.41  5100.6  357.16  5189.2  359.83
  5302.7     360  5363.4  361.29  5383.6  361.11  5444.2  358.17  5484.6  361.36
  5565.5  363.27  5668.3  363.79  5787.9  366.32  5934.1  368.13  5959.3  367.15
  5973.3  365.72  6007.2   368.5  6041.2     369  6073.6  368.39  6257.3  370.68
#Mann= 3 ,-1 , 0
  4464.6      .1       0  5016.4     .07       0    5023      .1       0
Bank Sta=5016.4,5023
XS Rating Curve= 0 ,0
Exp/Cntr=0.3,0.1

Type RM Length L Ch R = 1 ,4822    ,835,835,835
BEGIN DESCRIPTION:
UNT 067 in RCW 8.0
END DESCRIPTION:
XS GIS Cut Line= 3
      2068924.01     13417406.87      2069124.52     13416818.36
       2069179.2       13415946.
#Sta/Elev= 30
  4384.8  364.09  4693.1  362.26  4724.8  361.42  4756.5  361.82  4830.5  361.18
  4930.7  356.53  4946.7  355.32    4962  353.47  4967.8  351.95  4990.1   349.7
  4990.6   348.9  4996.2   348.9  4996.7   349.7  5005.7  351.61  5010.7  351.61
  5029.9  354.29  5089.6  356.64  5180.2  358.18  5200.3  357.55  5210.3  355.78
  5220.3  355.11  5230.3  355.48  5254.7  357.96  5310.5   358.4  5380.6  359.96
  5440.7  360.27  5691.2  365.28  5811.5  365.63  5841.5  366.83  5880.6  367.28
#Mann= 3 ,-1 , 0
  4384.8      .1       0  4990.1     .07       0  4996.7      .1       0
Bank Sta=4990.1,4996.7
XS Rating Curve= 0 ,0
Exp/Cntr=0.3,0.1

Type RM Length L Ch R = 1 ,3987    ,255,255,255
BEGIN DESCRIPTION:
UNT 067 in RCW 7.0
END DESCRIPTION:
XS GIS Cut Line= 4
      2069101.08     13417417.31      2069309.41     13417021.48
      2069848.47     13416776.69      2070022.57     13416308.98
#Sta/Elev= 30
  4161.5     362  4411.9  360.76  4446.6  359.41  4566.2  358.71  4608.8  357.92
    4634  355.75  4657.1  354.69  4662.6  355.54  4680.1  353.82  4724.8  354.09
  4760.4  351.32  4845.6  349.36  4875.7  349.31  4911.5  352.97  4927.4  353.17
  4984.9  345.33  4985.4  344.53  4991.3  344.53  4991.8  345.33  4996.6  346.98
  5002.1  346.53  5019.7   349.5  5025.2  347.95  5042.7  351.31  5048.2     350
  5071.3   352.2  5076.8  351.12  5196.8  354.61  5267.3  354.35  5699.9  359.51
#Mann= 3 ,-1 , 0
  4161.5      .1       0  4984.9     .07       0  4991.8      .1       0
Bank Sta=4984.9,4991.8
XS Rating Curve= 0 ,0
Exp/Cntr=0.3,0.1

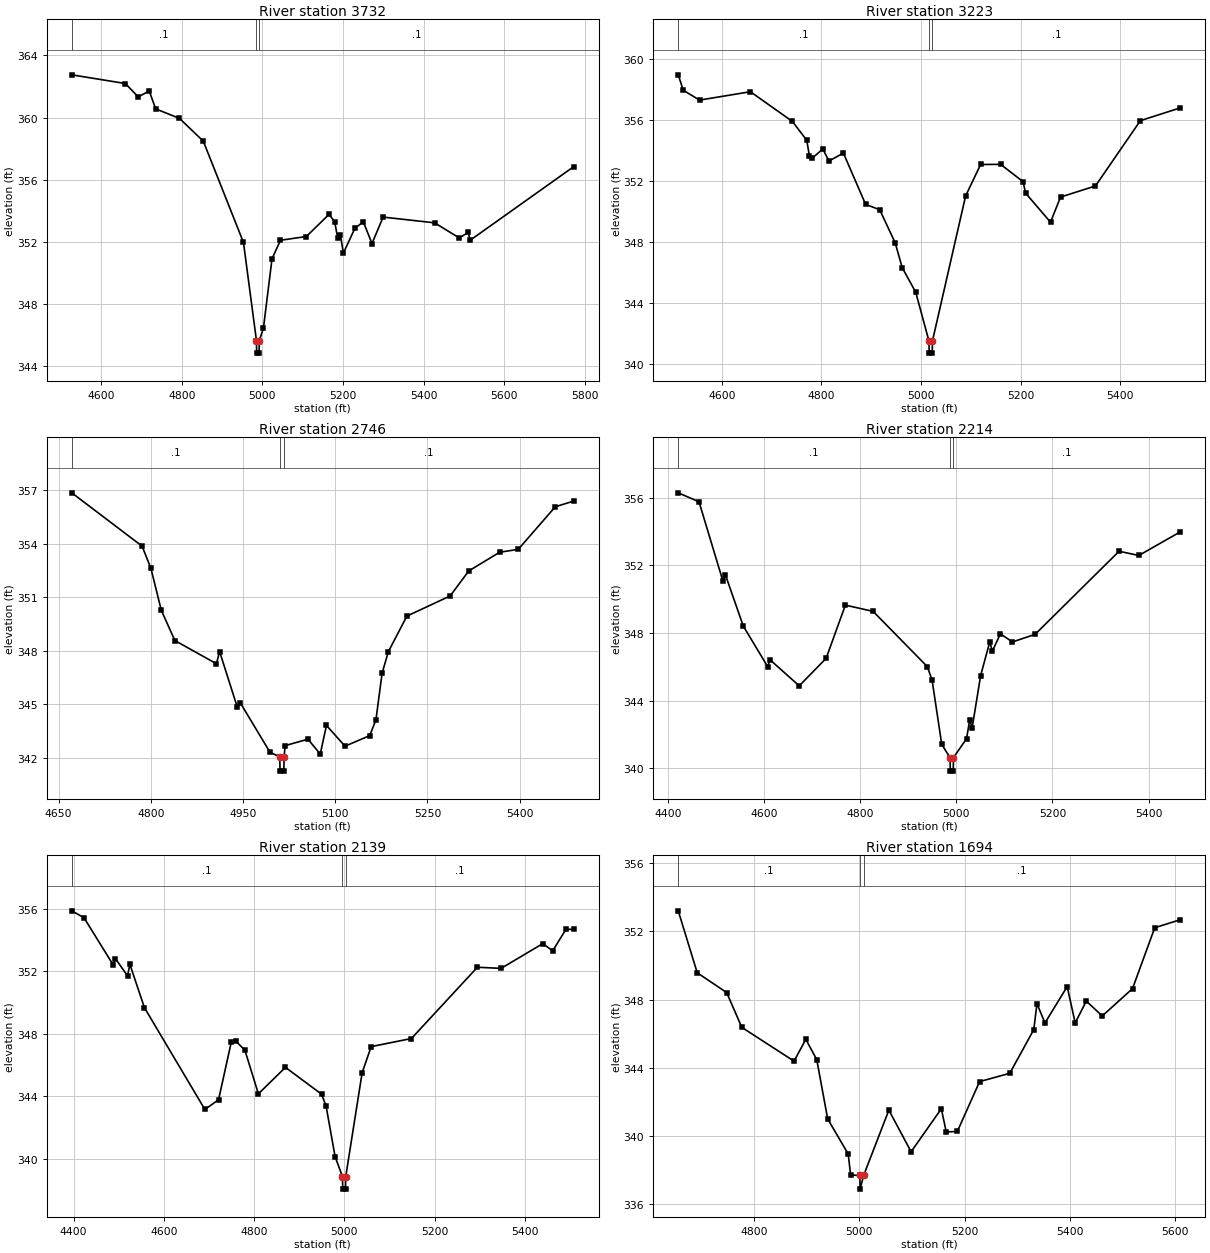
Type RM Length L Ch R = 1 ,3732    ,509,509,509
BEGIN DESCRIPTION:
Mapping XS e1d81a0c
END DESCRIPTION:
XS GIS Cut Line= 4
       2069426.6     13417479.81       2069614.1     13417149.09
      2070046.39     13416758.46      2070090.44     13416478.62
#Sta/Elev= 30
  4526.9  362.75    4660  362.19  4691.8  361.33  4719.2  361.71  4735.1  360.56
  4794.2  359.95  4853.4  358.48    4953  351.97  4985.3  345.65  4985.8  344.85
  4991.8  344.85  4992.3  345.65  5002.6  346.46  5023.9  350.92  5044.9  352.11
  5109.1  352.35  5165.2  353.77  5179.4  353.31  5186.8  352.25  5193.6  352.47
    5201  351.28  5229.4  352.87  5250.4   353.3    5272   351.9  5299.7   353.6
  5427.5  353.23  5488.6  352.26  5510.7  352.61  5515.7  352.11    5773  356.85
#Mann= 3 ,-1 , 0
  4526.9      .1       0  4985.3     .07       0  4992.3      .1       0
Bank Sta=4985.3,4992.3
XS Rating Curve= 0 ,0
Exp/Cntr=0.3,0.1

Type RM Length L Ch R = 1 ,3223    ,477,477,477
BEGIN DESCRIPTION:
UNT 067 in RCW 6.0
END DESCRIPTION:
XS GIS Cut Line= 3
      2069999.51     13417474.61        2070125.       13417025.
      2070160.98     13416484.99
#Sta/Elev= 30
  4512.7  358.97  4522.7  357.96  4555.4  357.31  4657.6  357.86  4741.8  355.91
  4770.8  354.67    4776  353.64  4782.2  353.51    4803   354.1  4815.3  353.31
  4844.3  353.83  4888.9  350.46  4917.2  350.11  4948.3  347.93  4962.4   346.3
  4989.5  344.69    5016  341.49  5016.6  340.69  5022.6  340.69  5023.1  341.49
  5089.7  351.02  5119.8  353.08  5159.9  353.09  5205.1  351.95  5210.1   351.2
  5260.1  349.29  5280.2  350.94  5350.3  351.67  5440.5  355.96  5520.7   356.8
#Mann= 3 ,-1 , 0
  4512.7      .1       0    5016     .07       0  5023.1      .1       0
Bank Sta=5016,5023.1
XS Rating Curve= 0 ,0
Exp/Cntr=0.3,0.1

Type RM Length L Ch R = 1 ,2746    ,532,532,532
BEGIN DESCRIPTION:
UNT 067 in RCW 5.0
END DESCRIPTION:
XS GIS Cut Line= 3
      2070325.01     13417424.98        2070425.       13417075.
      2070474.99     13416625.05
#Sta/Elev= 30
  4671.4  356.85  4785.8  353.86  4800.1  352.62    4817  350.27  4839.1  348.57
  4906.7  347.27  4911.9  347.95  4940.5  344.85  4945.7  345.07  4993.8  342.31
  5009.7  342.05  5010.2  341.25  5016.3  341.25  5016.8  342.05  5018.5  342.68
  5055.5  343.04  5075.6  342.21  5085.7  343.81  5115.9  342.65  5156.1  343.24
  5166.2  344.13  5176.2  346.74  5186.3  347.94  5216.5  349.94  5286.9  351.07
  5317.1  352.47  5367.4  353.52  5397.6  353.68    5458  356.07  5488.1  356.39
#Mann= 3 ,-1 , 0
  4671.4      .1       0  5009.7     .07       0  5016.8      .1       0
Bank Sta=5009.7,5016.8
XS Rating Curve= 0 ,0
Exp/Cntr=0.3,0.1

Type RM Length L Ch R = 1 ,2214    ,75,75,75
BEGIN DESCRIPTION:
Mapping XS b25a54b3
END DESCRIPTION:
XS GIS Cut Line= 4
      2070619.32     13417727.17      2070668.79     13417500.65
      2070692.22     13417133.46      2070588.05     13416701.13
#Sta/Elev= 30
  4421.4   356.3  4464.6  355.77  4514.5  351.06  4519.6  351.44  4556.7  348.41
  4607.4  346.01  4612.5  346.41  4673.1  344.87  4729.1   346.5  4769.1  349.65
  4826.8  349.28  4939.5  346.01  4949.5  345.21  4969.6   341.4  4986.8  340.62
  4987.4  339.82  4993.5  339.82    4994  340.62  5021.2  341.74  5027.7  342.85
  5032.9  342.39  5050.5  345.48  5069.6  347.48  5074.8  346.92  5091.6  347.95
  5116.7  347.47  5163.8  347.92  5338.5  352.84  5379.6  352.59  5465.9  353.99
#Mann= 3 ,-1 , 0
  4421.4      .1       0  4986.8     .07       0    4994      .1       0
Bank Sta=4986.8,4994
XS Rating Curve= 0 ,0
Exp/Cntr=0.3,0.1

Type RM Length L Ch R = 1 ,2139    ,445,445,445
BEGIN DESCRIPTION:
UNT 067 in RCW 4.0
END DESCRIPTION:
XS GIS Cut Line= 4
      2070660.98     13417753.22      2070759.93     13417443.36
      2070762.54     13417021.48      2070666.55     13416668.66
#Sta/Elev= 30
  4395.9  355.89  4422.9  355.45  4487.3  352.44  4492.5  352.83  4519.5  351.72
  4524.7  352.46  4556.9  349.68  4690.9  343.15  4721.2  343.77  4749.5  347.48
  4759.5  347.53  4779.5  346.96  4809.5  344.15  4869.5  345.85  4949.5  344.13
  4959.5  343.38  4979.5  340.13  4995.9  338.84  4996.5  338.04  5002.6  338.04
  5003.1  338.84  5039.5  345.51  5059.5  347.18  5148.7   347.7  5294.9  352.27
  5347.5   352.2    5440  353.79  5461.7  353.32  5491.1   354.7  5508.7  354.71
#Mann= 3 ,-1 , 0
  4395.9      .1       0  4995.9     .07       0  5003.1      .1       0
Bank Sta=4995.9,5003.1
XS Rating Curve= 0 ,0
Exp/Cntr=0.3,0.1

Type RM Length L Ch R = 1 ,1694    ,416,416,416
BEGIN DESCRIPTION:
UNT 067 in RCW 3.0
END DESCRIPTION:
XS GIS Cut Line= 3
      2070724.97     13417675.03        2070975.       13417475.
      2071317.25     13416940.72
#Sta/Elev= 30
  4655.5  353.21  4691.6  349.58  4747.6  348.42  4776.4  346.38  4875.7   344.4
  4898.1  345.68  4918.9  344.49  4939.7  341.01  4978.7  338.96  4983.3  337.73
  5000.8   337.7  5001.3   336.9    5008   337.7    5056  341.53  5098.3  339.09
  5155.8  341.61  5165.1  340.25  5186.2  340.28  5228.5   343.2    5286  343.69
  5331.6  346.25  5337.6  347.77  5352.8  346.64  5395.1  348.77  5410.3  346.64
  5431.4  347.92  5461.8  347.05  5519.3  348.65  5561.6  352.22  5610.2  352.69
#Mann= 3 ,-1 , 0
  4655.5      .1       0  5000.8     .07       0    5008      .1       0
Bank Sta=5000.8,5008
XS Rating Curve= 0 ,0
Exp/Cntr=0.3,0.1

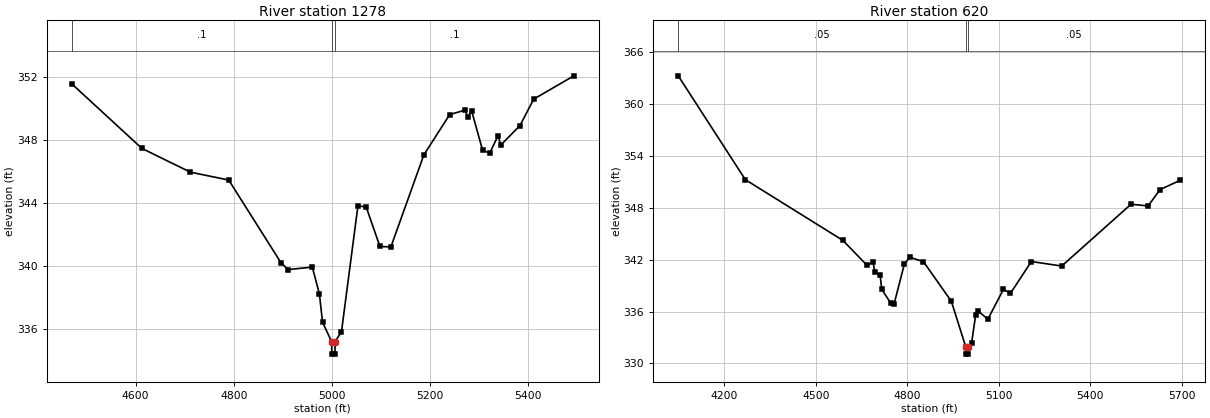
Type RM Length L Ch R = 1 ,1278    ,658,658,658
BEGIN DESCRIPTION:
UNT 067 in RCW 2.0
END DESCRIPTION:
XS GIS Cut Line= 3
      2070955.24     13417875.65        2071375.       13417525.
      2071587.32     13417098.48
#Sta/Elev= 30
  4469.9  351.57  4612.8  347.47  4711.7  345.96  4789.8  345.46  4896.5   340.2
  4910.8  339.77  4960.2  339.93  4974.6  338.23  4981.1  336.42  4999.5   335.2
  5000.1   334.4  5006.3   334.4  5006.8   335.2  5019.6  335.81  5053.2  343.82
    5070  343.75    5098  341.24  5120.4  341.21  5187.6  347.06  5240.3  349.62
  5271.6   349.9  5277.1  349.44  5284.9  349.86  5307.3  347.35  5321.9  347.17
  5338.7  348.28  5344.3  347.68  5383.5  348.92  5411.5   350.6  5493.3  352.08
#Mann= 3 ,-1 , 0
  4469.9      .1       0  4999.5     .07       0  5006.8      .1       0
Bank Sta=4999.5,5006.8
XS Rating Curve= 0 ,0
Exp/Cntr=0.3,0.1

Type RM Length L Ch R = 1 ,620     ,0,0,0
BEGIN DESCRIPTION:
UNT 067 in RCW 1.0
END DESCRIPTION:
XS GIS Cut Line= 4
      2070824.99       13417975.      2071447.43     13417998.04
      2071887.54     13417792.31      2071715.65     13417281.86
#Sta/Elev= 30
  4048.5  363.26  4268.7  351.25  4588.9  344.22  4667.7  341.35  4687.8   341.7
  4693.3   340.6  4710.7  340.25  4716.2  338.56    4746  336.95  4756.3  336.82
  4790.2  341.45  4807.6  342.28  4853.2  341.76  4944.6  337.18  4992.2  331.87
  4992.7  331.07  4998.9  331.07  4999.5  331.87  5010.9  332.33  5024.2  335.55
    5033  336.03  5064.4  335.11  5115.6  338.57  5138.4  338.09    5207  341.78
  5306.7  341.26  5534.2  348.41  5590.2  348.21  5629.2   350.1  5695.8  351.18
#Mann= 3 ,-1 , 0
  4048.5     .05       0  4992.2     .03       0  4999.5     .05       0
Bank Sta=4992.2,4999.5
XS Rating Curve= 0 ,0
Exp/Cntr=0.3,0.1
LCMann Table=0

Chan Stop Cuts=-1
Use User Specified Reach Order=0
Composite Channel Slope=5