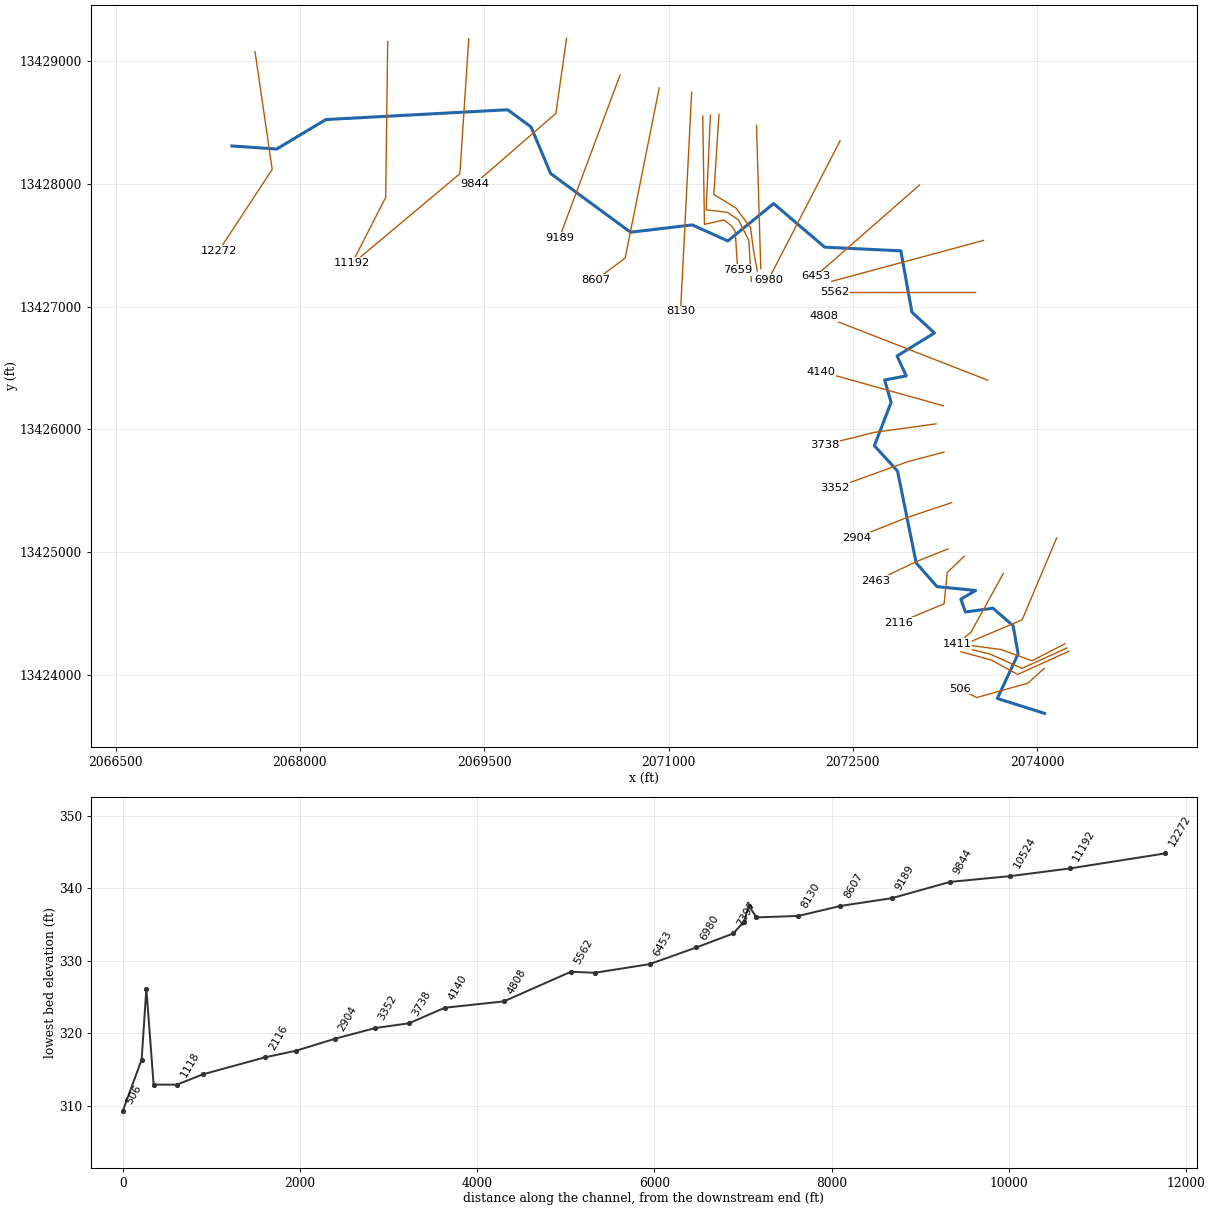
--- UNT 068 in RCW.prj (project) ---

Proj Title=UNT 068 in RCW Base Level Engineering
Current Plan=p01
Default Exp/Contr=0.3,0.1
English Units
Geom File=g01
Flow File=f01
Plan File=p01
BEGIN DESCRIPTION:
UNT 068 in RCW
END DESCRIPTION:

--- UNT 068 in RCW.p01 (plan) ---

Plan Title=Multiple Run
Short Identifier=Multiple
Geom File=g01
Flow File=f01
Subcritical Flow
K Sum by GR= 0
Std Step Tol= 0.01
Critical Tol= 0.01
Num of Std Step Trials= 20
Max Error Tol= 0.3
Flow Tol Ratio= 0.001
Split Flow NTrial= 30
Split Flow Tol= 0.02
Split Flow Ratio= 0.02
Log Output Level= 0
Friction Slope Method= 1
Unsteady Friction Slope Method= 2
Unsteady Bridges Friction Slope Method= 1
Parabolic Critical Depth
Global Vel Dist=  1 , 1 , 1
Global Log Level= 0
CheckData=True
Encroach Param= -1, 0, 0, 0
BEGIN DESCRIPTION:
Multiple Run
END DESCRIPTION:

--- UNT 068 in RCW.f01 (steady flow) ---

Flow Title=Multiple
Number of Profiles=7
Profile Names=10-year,25-year,50-year,1pct_min,100-year,1pct_plu,500-year
River Rch & RM= UNT 068 in RCW,Reach-1,12272
     148     200     241     145     290     579     426
River Rch & RM= UNT 068 in RCW,Reach-1,11192
     217     296     360     218     435     869     647
River Rch & RM= UNT 068 in RCW,Reach-1,3738
     256     353     431     263     524    1046     786
Boundary for River Rch & Prof#=UNT 068 in RCW,Reach-1,1
Up Type=0
Dn Type=3
Dn Slope=0.005
Boundary for River Rch & Prof#=UNT 068 in RCW,Reach-1,2
Up Type=0
Dn Type=3
Dn Slope=0.005
Boundary for River Rch & Prof#=UNT 068 in RCW,Reach-1,3
Up Type=0
Dn Type=3
Dn Slope=0.005
Boundary for River Rch & Prof#=UNT 068 in RCW,Reach-1,4
Up Type=0
Dn Type=3
Dn Slope=0.005
Boundary for River Rch & Prof#=UNT 068 in RCW,Reach-1,5
Up Type=0
Dn Type=3
Dn Slope=0.005
Boundary for River Rch & Prof#=UNT 068 in RCW,Reach-1,6
Up Type=0
Dn Type=3
Dn Slope=0.005
Boundary for River Rch & Prof#=UNT 068 in RCW,Reach-1,7
Up Type=0
Dn Type=3
Dn Slope=0.005

--- UNT 068 in RCW.g01 (geometry) ---

Geom Title=Existing Conditions

River Reach=UNT 068 in RCW,Reach-1
Reach XY= 30
      2067445.80     13428309.54      2067810.80     13428284.54
      2068210.80     13428524.54      2069690.80     13428604.54
      2069880.80     13428464.54      2070040.80     13428084.54
      2070690.79     13427606.25      2071192.87     13427665.97
      2071482.67     13427535.33      2071855.38     13427839.62
      2072270.80     13427484.54      2072890.80     13427454.54
      2072980.80     13426954.54      2073164.28     13426785.34
      2072860.11     13426597.14      2072935.11     13426435.34
      2072758.72     13426402.01      2072811.50     13426218.67
      2072675.30     13425866.15      2072864.19     13425659.21
      2073015.58     13424911.29      2073185.02     13424717.54
      2073498.98     13424686.36      2073379.47     13424615.46
      2073416.27     13424510.60      2073639.88     13424541.85
      2073804.47     13424399.49      2073845.44     13424169.63
      2073676.00     13423805.74      2074060.80     13423684.54

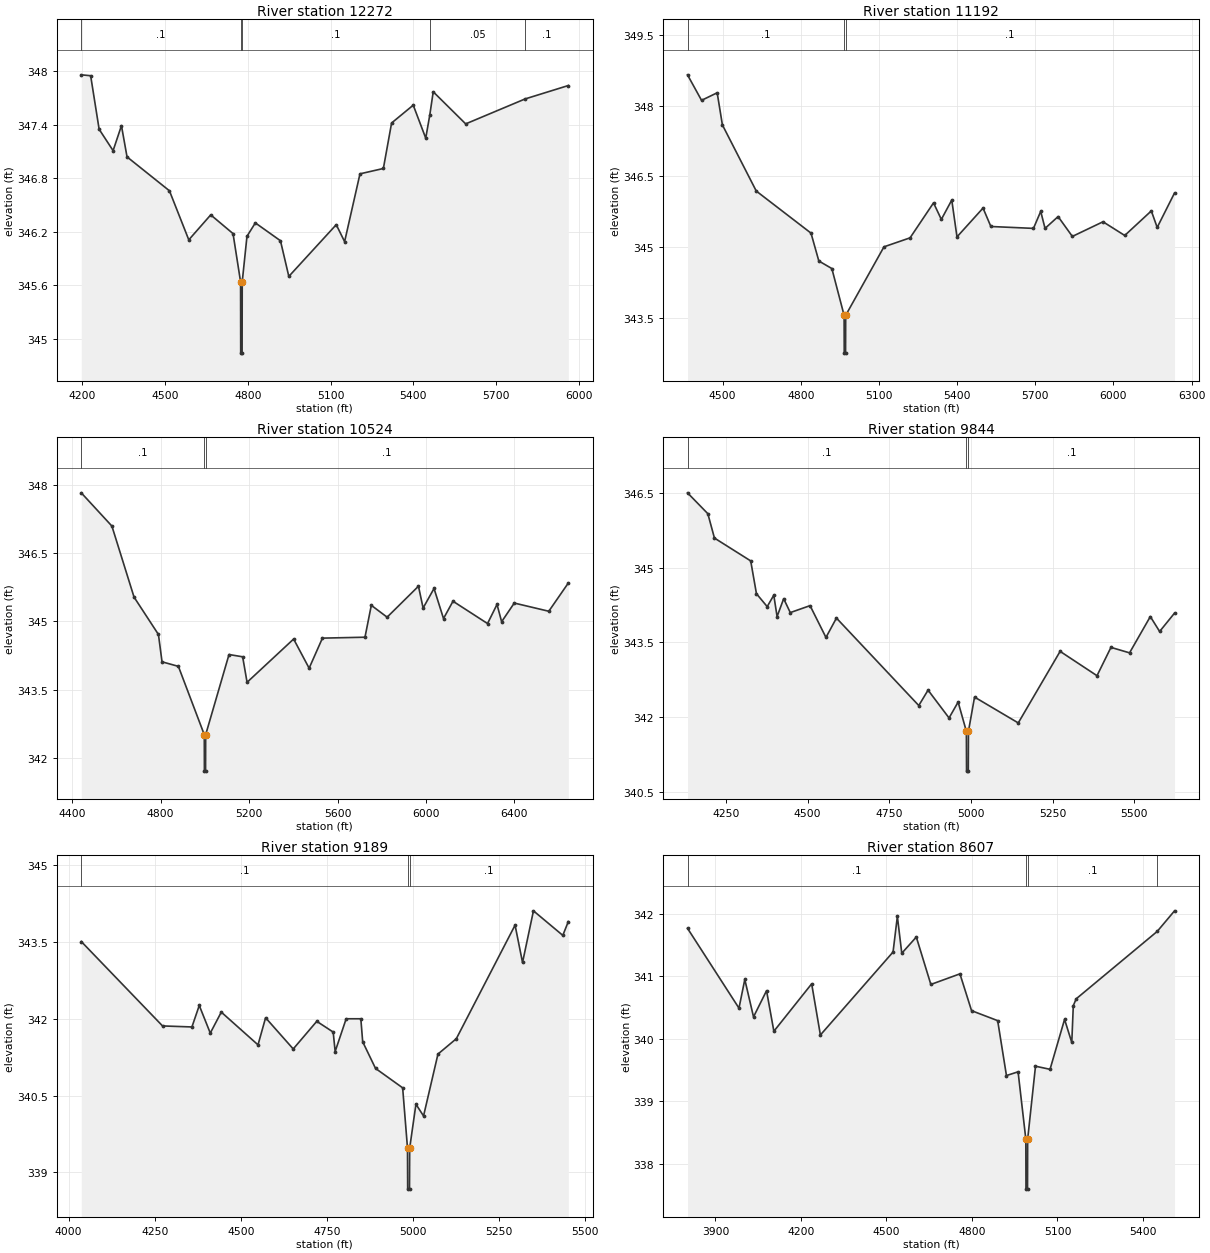
Type RM Length L Ch R = 1,12272,1080,1080,1080
BEGIN DESCRIPTION:
UNT 068 in RCW 15.0
END DESCRIPTION:
XS GIS Cut Line= 3
      2067634.43     13429079.07      2067774.19     13428118.69
      2067339.31     13427454.48
#Sta/Elev= 30
  4197.1  347.96  4231.1  347.95  4261.8  347.35  4312.4  347.11  4342.7  347.39
  4362.9  347.04  4516.5  346.66  4586.6  346.11  4666.1  346.39  4746.9  346.18
  4774.2  345.64  4774.7  344.84  4779.7  344.84  4780.2  345.64  4797.4  346.15
  4827.7  346.30  4918.7  346.10  4949.0  345.70  5120.8  346.28  5151.1  346.09
  5206.8  346.85  5291.5  346.91  5321.3  347.42  5399.7  347.62  5445.0  347.25
  5459.7  347.51  5472.1  347.77  5589.7  347.41  5805.2  347.69  5961.5  347.84
#Mann=5,-1,0
  4197.1     0.1       0  4774.2    0.07       0  4780.2     0.1       0
  5459.7    0.05       0  5805.2     0.1       0
Bank Sta=4774.2,4780.2
Exp/Cntr=0.3,0.1

Type RM Length L Ch R = 1,11192,668,668,668
BEGIN DESCRIPTION:
Mapping XS a5985849
END DESCRIPTION:
XS GIS Cut Line= 3
      2068714.29     13429158.89      2068697.96     13427890.87
      2068425.32     13427355.63
#Sta/Elev= 30
  4365.6  348.65  4419.5  348.11  4479.5  348.27  4499.5  347.59  4629.5  346.19
  4839.5  345.30  4869.5  344.71  4919.5  344.55  4966.5  343.56  4967.0  342.76
  4972.1  342.76  4972.6  343.56  5119.5  345.01  5219.6  345.20  5309.6  345.94
  5339.6  345.59  5379.6  346.00  5399.6  345.22  5499.6  345.83  5529.6  345.44
  5693.1  345.40  5720.9  345.76  5737.5  345.40  5787.6  345.65  5842.3  345.23
  5959.9  345.54  6043.3  345.25  6145.3  345.77  6167.8  345.42  6234.4  346.15
#Mann=3,-1,0
  4365.6     0.1       0  4966.5    0.07       0  4972.6     0.1       0
Bank Sta=4966.5,4972.6
Exp/Cntr=0.3,0.1

Type RM Length L Ch R = 1,10524,680,680,680
BEGIN DESCRIPTION:
Mapping XS 25d024d0
END DESCRIPTION:
XS GIS Cut Line= 3
      2069374.01     13429183.23      2069301.77     13428083.11
      2068459.19     13427375.93
#Sta/Elev= 30
  4441.2  347.82  4579.7  347.09  4679.9  345.53  4790.2  344.71  4806.4  344.11
  4880.4  344.01  4997.5  342.51  4998.0  341.71  5003.3  341.71  5003.8  342.51
  5109.3  344.27  5171.0  344.22  5191.0  343.66  5401.5  344.61  5471.6  343.97
  5531.8  344.63  5724.2  344.65  5752.8  345.35  5824.3  345.09  5966.1  345.77
  5987.0  345.29  6036.4  345.72  6079.3  345.06  6122.2  345.44  6278.4  344.95
  6321.3  345.37  6342.1  344.99  6399.3  345.40  6555.4  345.22  6643.7  345.84
#Mann=3,-1,0
  4441.2     0.1       0  4997.5    0.07       0  5003.8     0.1       0
Bank Sta=4997.5,5003.8
Exp/Cntr=0.3,0.1

Type RM Length L Ch R = 1,9844,655,655,655
BEGIN DESCRIPTION:
Mapping XS 06c9c26c
END DESCRIPTION:
XS GIS Cut Line= 3
      2070170.01     13429186.65      2070083.21     13428574.71
      2069423.51     13428001.81
#Sta/Elev= 30
  4132.0  346.51  4194.3  346.09  4214.5  345.60  4325.6  345.14  4343.2  344.48
  4376.1  344.22  4396.3  344.45  4406.4  344.02  4426.6  344.38  4446.8  344.10
  4507.4  344.24  4556.1  343.60  4588.2  343.99  4840.4  342.23  4868.8  342.54
  4933.1  341.98  4960.9  342.30  4986.2  341.71  4986.7  340.91  4992.0  340.91
  4992.5  341.71  5011.2  342.40  5145.1  341.88  5273.3  343.32  5386.3  342.83
  5429.0  343.40  5486.0  343.29  5549.6  344.02  5578.1  343.72  5623.8  344.09
#Mann=3,-1,0
  4132.0     0.1       0  4986.2    0.07       0  4992.5     0.1       0
Bank Sta=4986.2,4992.5
Exp/Cntr=0.3,0.1

Type RM Length L Ch R = 1,9189,582,582,582
BEGIN DESCRIPTION:
Mapping XS dd196349
END DESCRIPTION:
XS GIS Cut Line= 2
      2070604.92     13428886.35      2070111.88     13427560.02
#Sta/Elev= 30
  4036.7  343.51  4272.8  341.86  4358.2  341.84  4379.5  342.26  4411.5  341.72
  4443.5  342.13  4550.2  341.49  4572.2  342.02  4652.5  341.41  4720.9  341.95
  4768.6  341.74  4774.3  341.36  4806.3  342.00  4848.9  342.00  4854.3  341.55
  4891.6  341.03  4970.4  340.65  4984.5  339.47  4985.0  338.67  4990.3  338.67
  4990.8  339.47  5009.0  340.33  5031.1  340.10  5073.0  341.31  5126.3  341.61
  5297.0  343.83  5318.7  343.10  5350.4  344.11  5435.7  343.63  5451.7  343.90
#Mann=3,-1,0
  4036.7     0.1       0  4984.5    0.07       0  4990.8     0.1       0
Bank Sta=4984.5,4990.8
Exp/Cntr=0.3,0.1

Type RM Length L Ch R = 1,8607,477,477,477
BEGIN DESCRIPTION:
Mapping XS 062b9fcc
END DESCRIPTION:
XS GIS Cut Line= 3
      2070924.35     13428782.14      2070647.05     13427395.64
      2070411.02     13427219.28
#Sta/Elev= 30
  3802.1  341.77  3982.7  340.49  4003.1  340.95  4033.7  340.35  4079.4  340.77
  4105.1  340.12  4237.7  340.88  4268.3  340.06  4523.2  341.39  4538.3  341.96
  4553.8  341.37  4604.8  341.63  4655.8  340.87  4757.8  341.04  4798.6  340.45
  4890.2  340.29  4921.0  339.41  4961.8  339.47  4989.0  338.39  4989.5  337.59
  4994.9  337.59  4995.4  338.39  5022.9  339.56  5073.9  339.51  5124.9  340.31
  5150.2  339.94  5155.5  340.53  5165.7  340.64  5449.9  341.72  5510.7  342.05
#Mann=4,-1,0
  3802.1     0.1       0  4989.0    0.07       0  4995.4     0.1       0
  5449.9    0.05       0
Bank Sta=4989,4995.4
Exp/Cntr=0.3,0.1

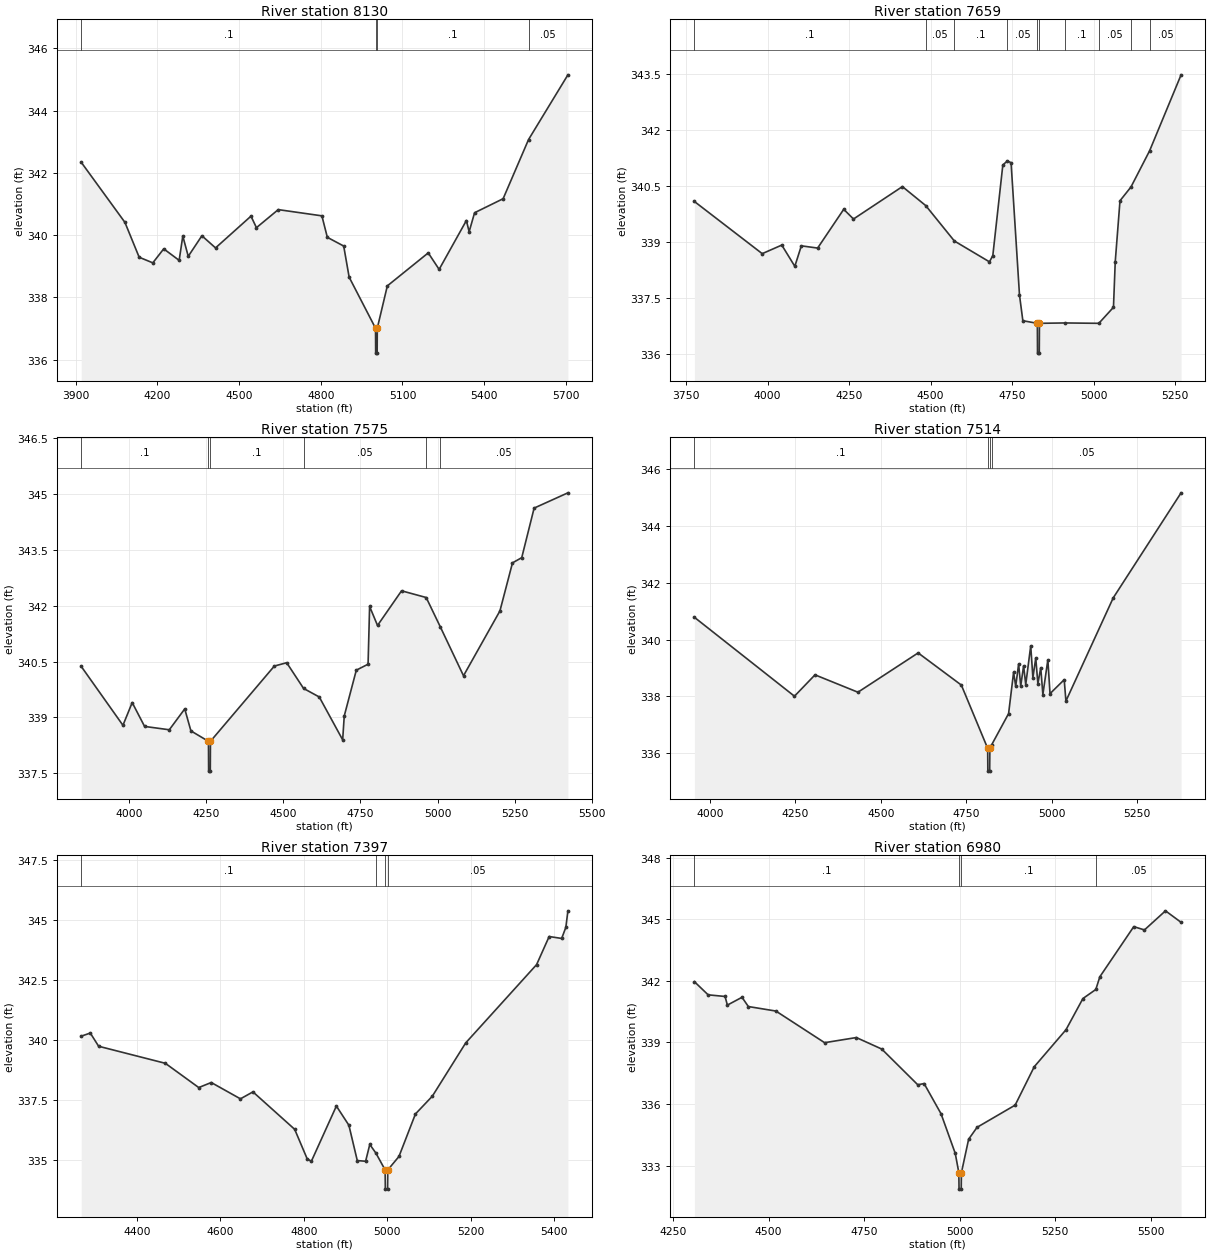
Type RM Length L Ch R = 1,8130,471,471,471
BEGIN DESCRIPTION:
Mapping XS 3879a63f
END DESCRIPTION:
XS GIS Cut Line= 2
      2071188.25     13428747.44      2071097.97     13426962.73
#Sta/Elev= 30
  3920.4  342.34  4080.8  340.41  4133.1  339.29  4183.2  339.11  4223.2  339.56
  4279.9  339.19  4293.3  339.97  4313.3  339.32  4363.4  339.98  4413.5  339.59
  4543.6  340.61  4563.7  340.24  4643.8  340.82  4804.0  340.62  4824.0  339.93
  4884.1  339.65  4904.1  338.65  5001.0  337.01  5001.5  336.21  5006.9  336.21
  5007.4  337.01  5044.3  338.37  5194.5  339.43  5234.5  338.90  5334.6  340.47
  5344.7  340.11  5364.7  340.72  5469.5  341.17  5562.8  343.07  5707.4  345.15
#Mann=4,-1,0
  3920.4     0.1       0  5001.0    0.07       0  5007.4     0.1       0
  5562.8    0.05       0
Bank Sta=5001,5007.4
Exp/Cntr=0.3,0.1

Type RM Length L Ch R = 1,7659,84,84,84
BEGIN DESCRIPTION:
Mapping XS 52c7cb73
END DESCRIPTION:
XS GIS Cut Line= 6
      2071278.53     13428552.97      2071292.41     13427671.06
      2071452.14     13427705.79      2071514.64     13427657.18
      2071542.41     13427615.51      2071563.12     13427298.01
#Sta/Elev= 30
  3775.4  340.08  3983.4  338.68  4043.4  338.91  4083.4  338.34  4103.4  338.89
  4153.4  338.83  4233.4  339.87  4263.4  339.61  4413.4  340.48  4485.0  339.97
  4572.8  339.02  4680.5  338.46  4690.8  338.63  4721.5  341.06  4735.6  341.17
  4746.8  341.12  4772.6  337.57  4782.9  336.88  4827.4  336.81  4827.9  336.01
  4833.3  336.01  4833.8  336.81  4911.5  336.82  5016.0  336.81  5060.9  337.24
  5066.3  338.46  5080.9  340.10  5114.6  340.47  5171.7  341.44  5268.3  343.48
#Mann=10,-1,0
  3775.4     0.1       0  4485.0    0.05       0  4572.8     0.1       0
  4735.6    0.05       0  4827.4    0.07       0  4833.8    0.05       0
  4911.5     0.1       0  5016.0    0.05       0  5114.6     0.1       0
  5171.7    0.05       0
Bank Sta=4827.4,4833.8
Exp/Cntr=0.3,0.1

Type RM Length L Ch R = 1,7575,61,61,61
BEGIN DESCRIPTION:
Mapping XS 8631a4aa
END DESCRIPTION:
XS GIS Cut Line= 6
      2071341.03     13428559.97      2071306.30     13427789.12
      2071479.91     13427768.29      2071570.19     13427705.79
      2071653.53     13427539.12      2071674.36     13427205.75
#Sta/Elev= 30
  3845.5  340.37  3980.6  338.79  4010.6  339.40  4050.7  338.76  4130.8  338.67
  4180.8  339.23  4200.8  338.64  4257.7  338.36  4258.2  337.56  4263.6  337.56
  4264.1  338.36  4471.1  340.38  4511.1  340.47  4565.8  339.78  4616.7  339.55
  4692.5  338.40  4697.6  339.04  4736.7  340.27  4774.8  340.43  4779.8  341.98
  4805.4  341.47  4883.3  342.40  4963.1  342.22  5009.0  341.43  5084.0  340.12
  5202.0  341.86  5242.7  343.15  5272.7  343.29  5312.8  344.62  5422.3  345.03
#Mann=6,-1,0
  3845.5     0.1       0  4257.7    0.07       0  4264.1     0.1       0
  4565.8    0.05       0  4963.1     0.1       0  5009.0    0.05       0
Bank Sta=4257.7,4264.1
Exp/Cntr=0.3,0.1

Type RM Length L Ch R = 1,7514,117,117,117
BEGIN DESCRIPTION:
Mapping XS 3366cadf
END DESCRIPTION:
XS GIS Cut Line= 6
      2071410.47     13428566.87      2071368.80     13427914.12
      2071549.36     13427803.01      2071667.41     13427643.29
      2071695.19     13427434.95      2071722.89     13427289.54
#Sta/Elev= 30
  3954.9  340.78  4247.4  338.01  4307.5  338.76  4433.0  338.15  4609.0  339.53
  4735.4  338.40  4812.3  336.18  4812.8  335.38  4818.2  335.38  4818.7  336.18
  4823.8  336.30  4873.5  337.40  4888.1  338.85  4894.3  338.36  4902.8  339.14
  4909.0  338.37  4917.4  339.08  4923.6  338.42  4938.2  339.78  4944.5  338.66
  4952.9  339.35  4959.1  338.45  4967.5  339.01  4973.7  338.07  4988.3  339.29
  4994.6  338.10  5036.1  338.59  5041.1  337.84  5179.3  341.46  5377.8  345.15
#Mann=4,-1,0
  3954.9     0.1       0  4812.3    0.03       0  4818.7     0.1       0
  4823.8    0.05       0
Bank Sta=4812.3,4818.7
Exp/Cntr=0.3,0.1

Type RM Length L Ch R = 1,7397,417,417,417
BEGIN DESCRIPTION:
Mapping XS 06c547e3
END DESCRIPTION:
XS GIS Cut Line= 2
      2071716.02     13428476.66      2071750.75     13427309.98
#Sta/Elev= 30
  4266.1  340.16  4287.8  340.29  4307.8  339.74  4467.8  339.03  4547.9  338.02
  4577.9  338.23  4647.9  337.55  4677.9  337.84  4778.0  336.28  4808.0  335.05
  4818.0  334.95  4878.0  337.25  4908.0  336.45  4928.1  334.98  4948.1  334.95
  4958.1  335.65  4972.8  335.29  4994.9  334.59  4995.4  333.79  5000.8  333.79
  5001.3  334.59  5028.1  335.15  5067.6  336.92  5108.1  337.66  5188.2  339.88
  5358.2  343.14  5388.3  344.31  5418.3  344.23  5428.3  344.69  5433.3  345.38
#Mann=4,-1,0
  4266.1     0.1       0  4972.8    0.05       0  4994.9    0.03       0
  5001.3    0.05       0
Bank Sta=4994.9,5001.3
Exp/Cntr=0.3,0.1

Type RM Length L Ch R = 1,6980,527,527,527
BEGIN DESCRIPTION:
Mapping XS d67c5c35
END DESCRIPTION:
XS GIS Cut Line= 2
      2072396.58     13428351.62      2071813.34     13427219.86
#Sta/Elev= 30
  4305.8  341.96  4341.7  341.32  4386.0  341.24  4392.0  340.82  4430.3  341.20
  4446.9  340.75  4519.0  340.53  4646.4  338.99  4729.4  339.24  4795.9  338.68
  4890.2  336.94  4906.7  337.00  4951.0  335.53  4988.2  333.60  4997.6  332.66
  4998.1  331.86  5003.8  331.86  5004.3  332.66  5023.2  334.29  5045.3  334.87
  5144.9  335.95  5194.9  337.82  5277.9  339.62  5322.2  341.14  5355.9  341.58
  5366.5  342.20  5455.2  344.64  5483.2  344.48  5538.2  345.41  5579.0  344.85
#Mann=4,-1,0
  4305.8     0.1       0  4997.6    0.07       0  5004.3     0.1       0
  5355.9    0.05       0
Bank Sta=4997.6,5004.3
Exp/Cntr=0.3,0.1

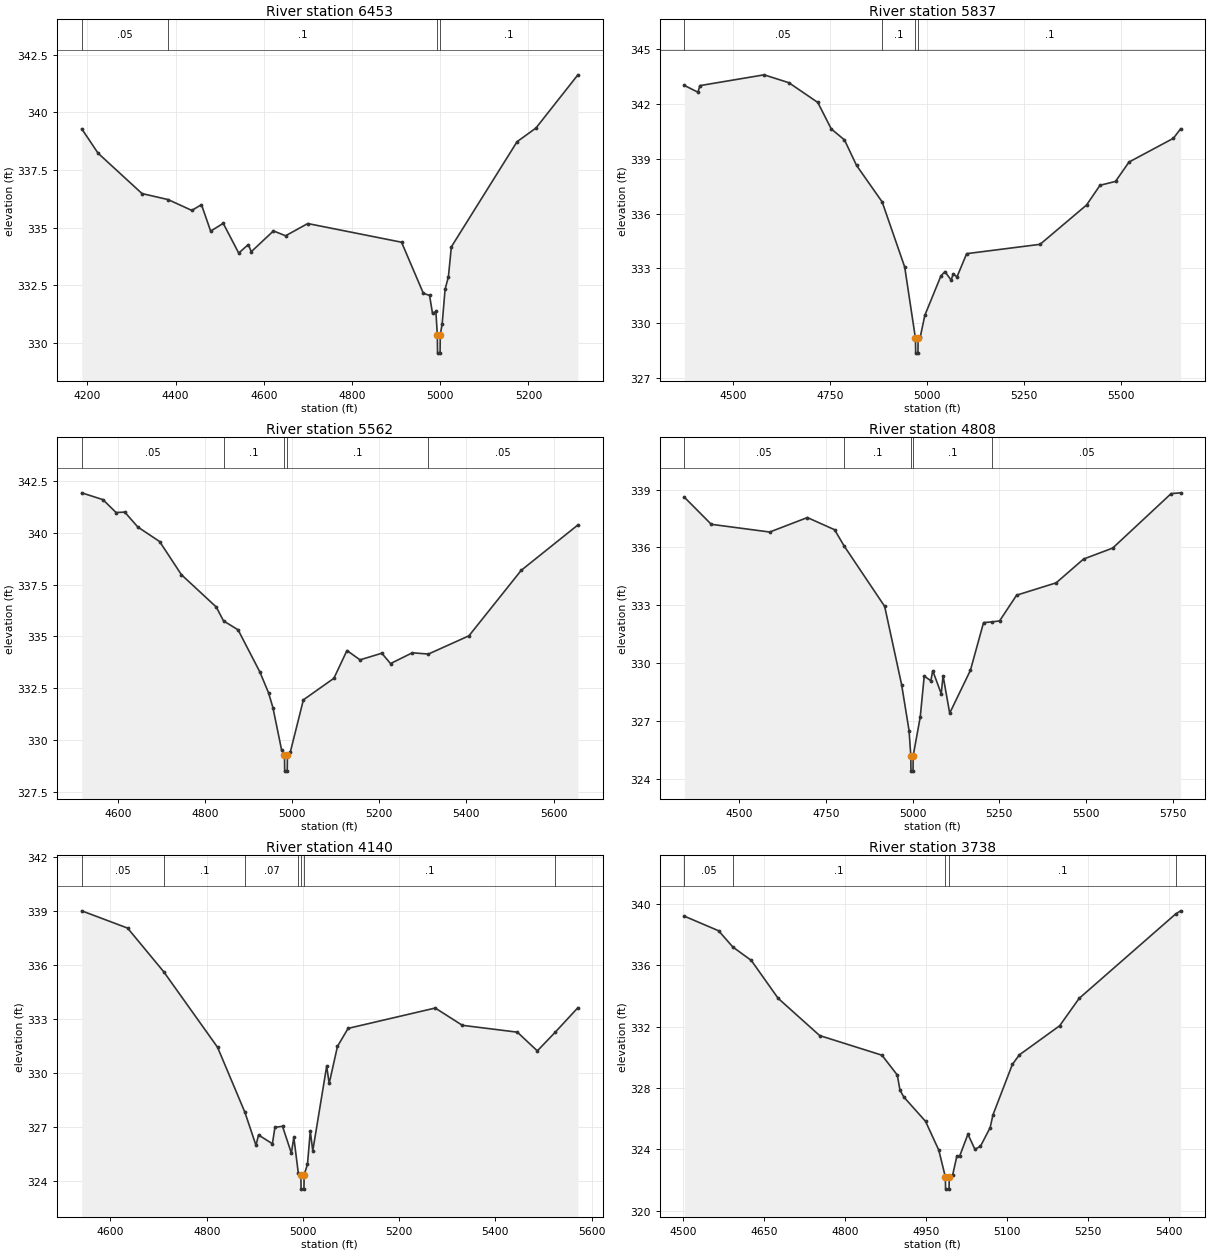
Type RM Length L Ch R = 1,6453,616,616,616
BEGIN DESCRIPTION:
Mapping XS dd03fd17
END DESCRIPTION:
XS GIS Cut Line= 2
      2073042.38     13427990.48      2072196.67     13427248.75
#Sta/Elev= 30
  4187.2  339.29  4224.3  338.23  4323.9  336.48  4383.0  336.22  4436.8  335.75
  4458.7  336.00  4479.5  334.85  4508.0  335.19  4543.1  333.90  4564.9  334.27
  4571.6  333.96  4621.9  334.86  4649.4  334.65  4699.7  335.18  4912.3  334.37
  4961.6  332.16  4975.8  332.06  4982.5  331.28  4990.1  331.37  4993.4  330.36
  4993.9  329.56  4999.6  329.56  5000.1  330.36  5004.3  330.81  5011.0  332.33
  5018.5  332.87  5025.2  334.17  5174.2  338.73  5216.9  339.32  5312.1  341.63
#Mann=4,-1,0
  4187.2    0.05       0  4383.0     0.1       0  4993.4    0.07       0
  5000.1     0.1       0
Bank Sta=4993.4,5000.1
Exp/Cntr=0.3,0.1

Type RM Length L Ch R = 1,5837,275,275,275
BEGIN DESCRIPTION:
Mapping XS af1dd68d
END DESCRIPTION:
XS GIS Cut Line= 2
      2073563.25     13427539.12      2072328.55     13427206.17
#Sta/Elev= 30
  4374.3  343.01  4409.0  342.64  4414.2  343.00  4579.6  343.59  4643.4  343.16
  4718.0  342.08  4752.8  340.63  4786.8  340.03  4817.8  338.64  4883.9  336.64
  4942.0  333.08  4969.8  329.17  4970.3  328.37  4976.1  328.37  4976.6  329.17
  4981.9  329.23  4993.9  330.44  5035.3  332.59  5045.7  332.83  5061.7  332.36
  5066.9  332.70  5076.8  332.54  5101.7  333.81  5290.9  334.32  5410.7  336.47
  5445.4  337.55  5485.3  337.76  5520.1  338.82  5634.6  340.12  5653.1  340.64
#Mann=4,-1,0
  4374.3    0.05       0  4883.9     0.1       0  4969.8    0.07       0
  4976.6     0.1       0
Bank Sta=4969.8,4976.6
Exp/Cntr=0.3,0.1

Type RM Length L Ch R = 1,5562,754,754,754
BEGIN DESCRIPTION:
Mapping XS 3ba0d1ce
END DESCRIPTION:
XS GIS Cut Line= 2
      2073493.80     13427122.45      2072354.90     13427122.45
#Sta/Elev= 30
  4517.0  341.93  4565.8  341.60  4595.8  340.98  4615.8  341.00  4645.8  340.28
  4695.8  339.58  4745.8  337.98  4825.8  336.42  4842.5  335.75  4875.8  335.32
  4925.8  333.29  4945.8  332.28  4955.8  331.57  4975.8  329.52  4982.4  329.30
  4982.9  328.50  4988.7  328.50  4989.2  329.30  4995.8  329.42  5025.8  331.94
  5095.8  332.98  5125.8  334.32  5155.8  333.87  5205.8  334.19  5225.8  333.69
  5275.8  334.21  5312.8  334.15  5405.8  335.03  5525.8  338.19  5655.9  340.38
#Mann=5,-1,0
  4517.0    0.05       0  4842.5     0.1       0  4982.4    0.07       0
  4989.2     0.1       0  5312.8    0.05       0
Bank Sta=4982.4,4989.2
Exp/Cntr=0.3,0.1

Type RM Length L Ch R = 1,4808,668,668,668
BEGIN DESCRIPTION:
Mapping XS b801b4bb
END DESCRIPTION:
XS GIS Cut Line= 2
      2073598.01     13426400.22      2072266.03     13426920.52
#Sta/Elev= 30
  4342.6  338.60  4420.0  337.20  4588.4  336.80  4697.0  337.55  4775.3  336.92
  4802.5  336.09  4919.7  332.95  4968.5  328.90  4990.0  326.52  4995.0  325.22
  4995.5  324.42  5001.4  324.42  5001.9  325.22  5022.2  327.22  5033.7  329.34
  5052.8  329.10  5058.2  329.62  5082.7  328.43  5088.0  329.36  5107.1  327.42
  5166.8  329.64  5204.7  332.11  5230.0  332.15  5251.0  332.20  5299.9  333.53
  5414.0  334.17  5492.8  335.40  5576.9  335.97  5745.3  338.79  5772.6  338.83
#Mann=5,-1,0
  4342.6    0.05       0  4802.5     0.1       0  4995.0    0.07       0
  5001.9     0.1       0  5230.0    0.05       0
Bank Sta=4995,5001.9
Exp/Cntr=0.3,0.1

Type RM Length L Ch R = 1,4140,402,402,402
BEGIN DESCRIPTION:
Mapping XS 538fae8e
END DESCRIPTION:
XS GIS Cut Line= 2
      2073236.87     13426191.89      2072243.79     13426469.68
#Sta/Elev= 30
  4540.2  339.00  4635.6  338.04  4710.5  335.62  4822.5  331.42  4879.3  327.81
  4902.4  325.97  4907.6  326.55  4936.5  326.06  4941.7  326.97  4957.5  327.03
  4975.9  325.54  4981.0  326.42  4990.4  324.41  4995.6  324.34  4996.1  323.54
  5002.0  323.54  5002.5  324.34  5009.4  324.92  5015.2  326.76  5020.4  325.67
  5049.3  330.37  5054.5  329.41  5071.7  331.47  5093.8  332.47  5274.9  333.60
  5331.3  332.64  5445.5  332.26  5487.1  331.22  5524.4  332.26  5571.4  333.62
#Mann=7,-1,0
  4540.2    0.05       0  4710.5     0.1       0  4879.3    0.07       0
  4990.4     0.1       0  4995.6    0.07       0  5002.5     0.1       0
  5524.4    0.05       0
Bank Sta=4995.6,5002.5
Exp/Cntr=0.3,0.1

Type RM Length L Ch R = 1,3738,386,386,386
BEGIN DESCRIPTION:
UNT 068 in RCW 8.0
END DESCRIPTION:
XS GIS Cut Line= 3
      2073177.79     13426044.32      2072675.00     13425975.00
      2072274.95     13425874.99
#Sta/Elev= 30
  4502.4  339.19  4565.8  338.24  4592.2  337.18  4626.3  336.31  4676.1  333.84
  4753.1  331.41  4868.6  330.13  4897.0  328.84  4902.0  327.86  4909.0  327.41
  4949.4  325.82  4974.0  323.94  4986.1  322.20  4986.6  321.40  4992.9  321.40
  4993.5  322.20  4999.8  322.34  5007.4  323.54  5012.5  323.54  5028.0  324.98
  5040.9  324.00  5051.2  324.19  5069.2  325.41  5074.4  326.24  5110.4  329.53
  5123.3  330.15  5198.1  332.05  5234.1  333.83  5412.9  339.33  5422.3  339.54
#Mann=5,-1,0
  4502.4    0.05       0  4592.2     0.1       0  4986.1    0.07       0
  4993.5     0.1       0  5412.9    0.05       0
Bank Sta=4986.1,4993.5
Exp/Cntr=0.3,0.1

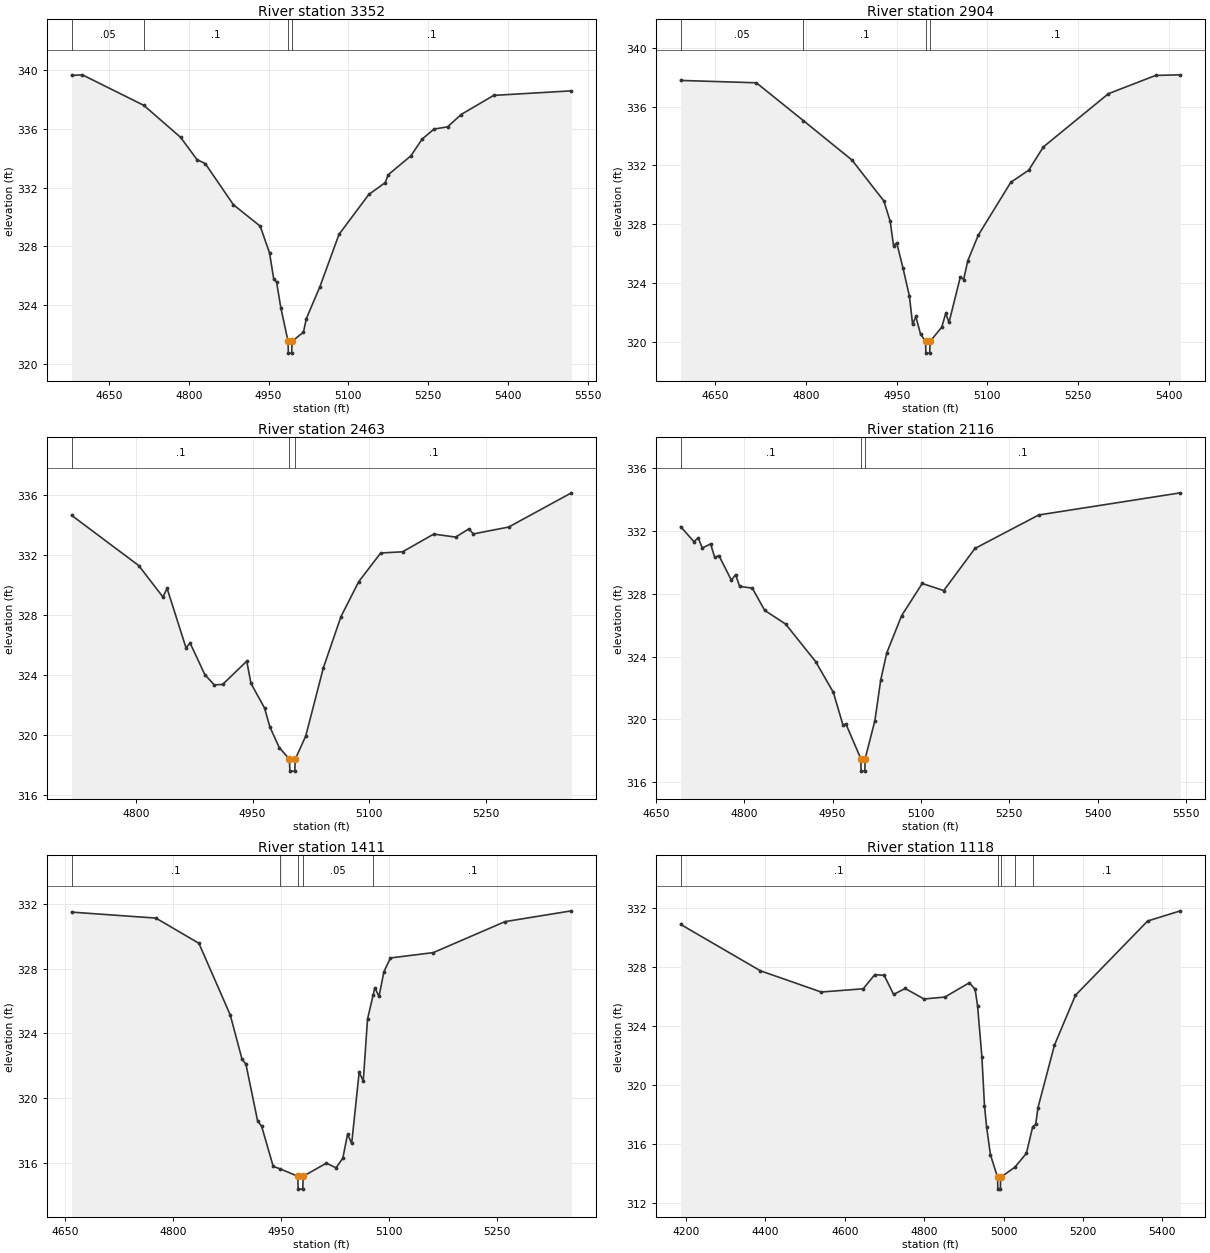
Type RM Length L Ch R = 1,3352,448,448,448
BEGIN DESCRIPTION:
UNT 068 in RCW 7.0
END DESCRIPTION:
XS GIS Cut Line= 3
      2073242.89     13425814.28      2072947.80     13425736.17
      2072351.06     13425521.01
#Sta/Elev= 30
  4579.8  339.63  4600.0  339.67  4715.6  337.59  4784.5  335.42  4815.5  333.90
  4831.0  333.63  4883.9  330.83  4934.3  329.37  4951.8  327.55  4959.7  325.78
  4965.0  325.58  4973.1  323.81  4986.7  321.53  4987.2  320.73  4993.5  320.73
  4994.1  321.53  5015.6  322.16  5021.0  323.08  5046.4  325.24  5082.4  328.81
  5138.5  331.53  5169.2  332.33  5175.0  332.87  5217.6  334.16  5238.8  335.30
  5261.2  335.98  5286.6  336.13  5312.0  336.97  5373.3  338.27  5519.4  338.58
#Mann=4,-1,0
  4579.8    0.05       0  4715.6     0.1       0  4986.7    0.07       0
  4994.1     0.1       0
Bank Sta=4986.7,4994.1
Exp/Cntr=0.3,0.1

Type RM Length L Ch R = 1,2904,441,441,441
BEGIN DESCRIPTION:
UNT 068 in RCW 6.0
END DESCRIPTION:
XS GIS Cut Line= 3
      2073303.74     13425401.98      2072925.00     13425275.00
      2072528.39     13425116.15
#Sta/Elev= 30
  4592.7  337.77  4717.9  337.61  4795.5  335.05  4876.1  332.37  4928.9  329.59
  4939.4  328.20  4944.8  326.57  4950.1  326.75  4960.5  325.04  4971.1  323.14
  4976.4  321.22  4981.7  321.76  4989.5  320.56  4997.8  320.07  4998.4  319.27
  5004.7  319.27  5005.3  320.07  5024.5  321.02  5031.2  321.97  5036.6  321.35
  5055.4  324.45  5060.8  324.26  5067.6  325.53  5085.0  327.27  5138.8  330.86
  5168.4  331.68  5192.7  333.26  5300.3  336.87  5378.4  338.11  5419.4  338.15
#Mann=4,-1,0
  4592.7    0.05       0  4795.5     0.1       0  4997.8    0.07       0
  5005.3     0.1       0
Bank Sta=4997.8,5005.3
Exp/Cntr=0.3,0.1

Type RM Length L Ch R = 1,2463,347,347,347
BEGIN DESCRIPTION:
UNT 068 in RCW 5.0
END DESCRIPTION:
XS GIS Cut Line= 3
      2073275.03     13425025.01      2073025.00     13424925.00
      2072688.70     13424764.58
#Sta/Elev= 30
  4717.7  334.66  4803.9  331.31  4834.9  329.22  4840.3  329.79  4864.5  325.84
  4869.9  326.14  4888.7  324.05  4900.8  323.36  4911.6  323.39  4942.6  324.94
  4948.0  323.46  4965.5  321.81  4972.2  320.57  4984.3  319.18  4997.4  318.41
  4998.0  317.61  5004.3  317.61  5004.9  318.41  5018.3  319.94  5041.0  324.50
  5063.6  327.91  5086.3  330.23  5114.6  332.15  5142.8  332.23  5182.7  333.41
  5210.9  333.21  5228.0  333.76  5233.6  333.42  5279.0  333.88  5359.6  336.16
#Mann=3,-1,0
  4717.7     0.1       0  4997.4    0.07       0  5004.9     0.1       0
Bank Sta=4997.4,5004.9
Exp/Cntr=0.3,0.1

Type RM Length L Ch R = 1,2116,705,705,705
BEGIN DESCRIPTION:
Mapping XS c220326a
END DESCRIPTION:
XS GIS Cut Line= 4
      2073406.64     13424965.26      2073268.65     13424832.48
      2073242.61     13424577.28      2072872.79     13424423.62
#Sta/Elev= 30
  4692.0  332.27  4714.6  331.31  4721.8  331.56  4728.7  330.91  4742.9  331.17
  4749.8  330.31  4757.0  330.43  4778.1  328.86  4785.3  329.22  4792.2  328.46
  4813.6  328.36  4834.7  326.94  4870.2  326.07  4921.2  323.68  4951.3  321.72
  4967.6  319.64  4972.6  319.71  4997.8  317.51  4998.4  316.71  5004.7  316.71
  5005.3  317.51  5021.7  319.91  5031.7  322.51  5041.8  324.22  5067.1  326.60
  5102.1  328.65  5138.7  328.20  5191.6  330.88  5299.9  333.01  5540.5  334.42
#Mann=3,-1,0
  4692.0     0.1       0  4997.8    0.07       0  5005.3     0.1       0
Bank Sta=4997.8,5005.3
Exp/Cntr=0.3,0.1

Type RM Length L Ch R = 1,1411,293,293,293
BEGIN DESCRIPTION:
UNT 068 in RCW 3.0
END DESCRIPTION:
XS GIS Cut Line= 3
      2073725.02     13424825.04      2073461.36     13424345.50
      2073349.41     13424250.46
#Sta/Elev= 30
  4658.8  331.52  4775.8  331.15  4835.5  329.59  4879.1  325.14  4895.2  322.44
  4900.9  322.08  4917.0  318.59  4922.7  318.24  4938.7  315.76  4948.2  315.61
  4972.8  315.15  4973.4  314.35  4979.8  314.35  4980.4  315.15  5012.6  315.96
  5025.9  315.67  5035.4  316.27  5042.0  317.76  5047.7  317.18  5058.1  321.60
  5063.8  321.05  5069.7  324.89  5077.5  326.38  5079.9  326.84  5085.6  326.29
  5092.5  327.83  5101.6  328.68  5161.0  329.01  5260.6  330.93  5352.9  331.60
#Mann=5,-1,0
  4658.8     0.1       0  4948.2    0.05       0  4972.8   0.033       0
  4980.4    0.05       0  5077.5     0.1       0
Bank Sta=4972.8,4980.4
Exp/Cntr=0.3,0.1

Type RM Length L Ch R = 1,1118,263,263,263
BEGIN DESCRIPTION:
Mapping XS 15ffc506
END DESCRIPTION:
XS GIS Cut Line= 3
      2074158.68     13425113.71      2073878.03     13424447.07
      2073384.41     13424237.43
#Sta/Elev= 30
  4186.2  330.86  4387.2  327.72  4540.5  326.28  4646.3  326.50  4675.5  327.46
  4699.2  327.41  4722.9  326.12  4752.1  326.52  4799.6  325.81  4852.1  325.94
  4913.9  326.91  4928.3  326.47  4934.5  325.36  4945.4  321.90  4952.0  318.57
  4957.4  317.11  4967.1  315.25  4985.0  313.73  4985.6  312.93  4992.0  312.93
  4992.6  313.73  5028.7  314.42  5057.5  315.35  5073.5  317.16  5081.1  317.31
  5086.6  318.43  5128.4  322.69  5181.2  326.06  5363.1  331.09  5445.8  331.78
#Mann=5,-1,0
  4186.2     0.1       0  4985.0    0.07       0  4992.6     0.1       0
  5028.7    0.05       0  5073.5     0.1       0
Bank Sta=4985,4992.6
Exp/Cntr=0.3,0.1

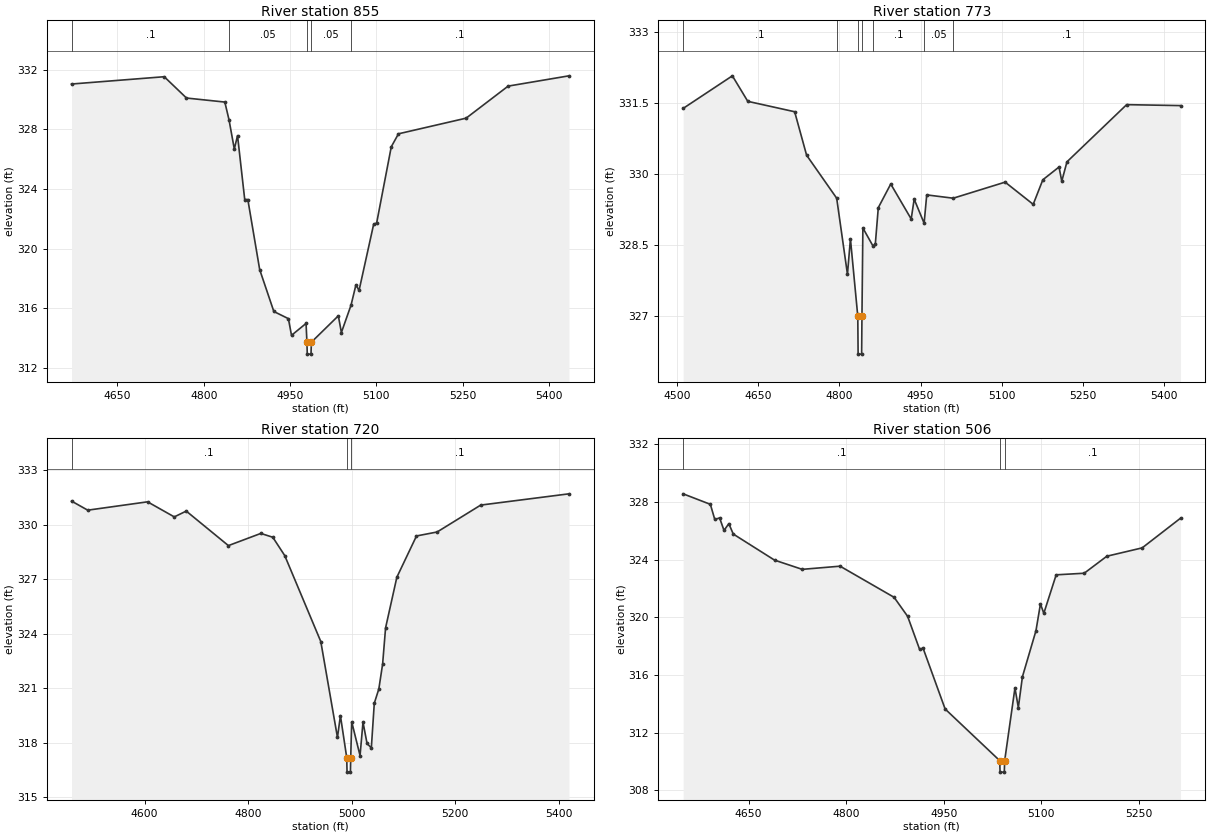
Type RM Length L Ch R = 1,855,82,82,82
BEGIN DESCRIPTION:
Mapping XS a6b4fd51
END DESCRIPTION:
XS GIS Cut Line= 4
      2074227.03     13424251.78      2073958.75     13424113.73
      2073706.15     13424204.88      2073414.50     13424243.94
#Sta/Elev= 30
  4570.2  331.05  4731.3  331.54  4770.0  330.11  4836.6  329.84  4843.9  328.65
  4853.1  326.69  4858.7  327.59  4871.2  323.30  4876.6  323.30  4897.2  318.60
  4921.8  315.79  4947.1  315.31  4952.5  314.19  4977.8  314.99  4979.3  313.73
  4979.9  312.93  4986.4  312.93  4987.0  313.73  5033.9  315.50  5039.2  314.38
  5056.0  316.22  5064.5  317.58  5069.9  317.20  5095.2  321.63  5100.5  321.73
  5125.9  326.84  5138.4  327.71  5256.0  328.76  5329.0  330.91  5434.7  331.60
#Mann=5,-1,0
  4570.2     0.1       0  4843.9    0.05       0  4979.3   0.033       0
  4987.0    0.05       0  5056.0     0.1       0
Bank Sta=4979.3,4987
Exp/Cntr=0.3,0.1

Type RM Length L Ch R = 1,773,53,53,53
BEGIN DESCRIPTION:
UNT 068 in RCW 2.0
END DESCRIPTION:
XS GIS Cut Line= 4
      2074242.58     13424217.89      2073878.03     13424051.23
      2073615.00     13424168.42      2073391.07     13424223.10
#Sta/Elev= 30
  4511.2  331.39  4602.2  332.08  4630.7  331.54  4717.3  331.32  4739.4  330.40
  4795.0  329.49  4814.9  327.88  4820.4  328.63  4834.0  326.99  4834.6  326.19
  4841.1  326.19  4841.7  326.99  4843.4  328.86  4862.0  328.48  4866.4  328.52
  4871.9  329.29  4894.9  329.79  4932.7  329.05  4938.2  329.47  4956.6  328.96
  4961.4  329.56  5010.4  329.49  5106.3  329.83  5158.2  329.36  5176.0  329.88
  5205.9  330.15  5211.0  329.85  5220.6  330.26  5330.9  331.47  5430.5  331.45
#Mann=7,-1,0
  4511.2     0.1       0  4795.0    0.05       0  4834.0   0.033       0
  4841.7    0.05       0  4862.0     0.1       0  4956.6    0.05       0
  5010.4     0.1       0
Bank Sta=4834,4841.7
Exp/Cntr=0.3,0.1

Type RM Length L Ch R = 1,720,214,214,214
BEGIN DESCRIPTION:
Mapping XS 5fa71201
END DESCRIPTION:
XS GIS Cut Line= 4
      2074260.88     13424191.88      2073841.57     13424001.75
      2073628.03     13424118.94      2073380.61     13424186.66
#Sta/Elev= 30
  4458.9  331.31  4490.2  330.81  4605.7  331.27  4657.3  330.44  4680.4  330.76
  4761.8  328.86  4824.4  329.53  4847.5  329.32  4870.6  328.31  4940.2  323.58
  4972.4  318.30  4978.1  319.50  4990.3  317.19  4990.9  316.39  4997.4  316.39
  4998.0  317.19  4999.9  319.16  5016.0  317.30  5021.7  319.14  5029.5  317.97
  5037.8  317.72  5043.5  320.18  5052.3  320.97  5059.6  322.34  5065.3  324.33
  5087.1  327.12  5125.0  329.39  5164.9  329.61  5249.0  331.09  5419.4  331.71
#Mann=3,-1,0
  4458.9     0.1       0  4990.3    0.07       0  4998.0     0.1       0
Bank Sta=4990.3,4998
Exp/Cntr=0.3,0.1

Type RM Length L Ch R = 1,506,0,0,0
BEGIN DESCRIPTION:
UNT 068 in RCW 1.0
END DESCRIPTION:
XS GIS Cut Line= 4
      2074057.68     13424051.20      2073924.36     13423930.61
      2073507.69     13423813.43      2073372.81     13423884.57
#Sta/Elev= 30
  4549.2  328.57  4591.1  327.84  4597.9  326.79  4605.3  326.90  4612.1  326.03
  4619.5  326.50  4626.3  325.78  4689.8  323.97  4732.4  323.33  4790.6  323.55
  4873.7  321.39  4894.5  320.07  4913.0  317.77  4918.2  317.87  4952.2  313.64
  5036.1  310.06  5036.7  309.26  5043.2  309.26  5043.8  310.06  5059.6  315.10
  5064.8  313.74  5071.1  315.88  5091.9  319.07  5098.8  320.93  5104.0  320.28
  5123.0  322.95  5166.1  323.06  5200.9  324.24  5255.3  324.82  5314.3  326.88
#Mann=3,-1,0
  4549.2     0.1       0  5036.1    0.07       0  5043.8     0.1       0
Bank Sta=5036.1,5043.8
Exp/Cntr=0.3,0.1

Chan Stop Cuts=-1