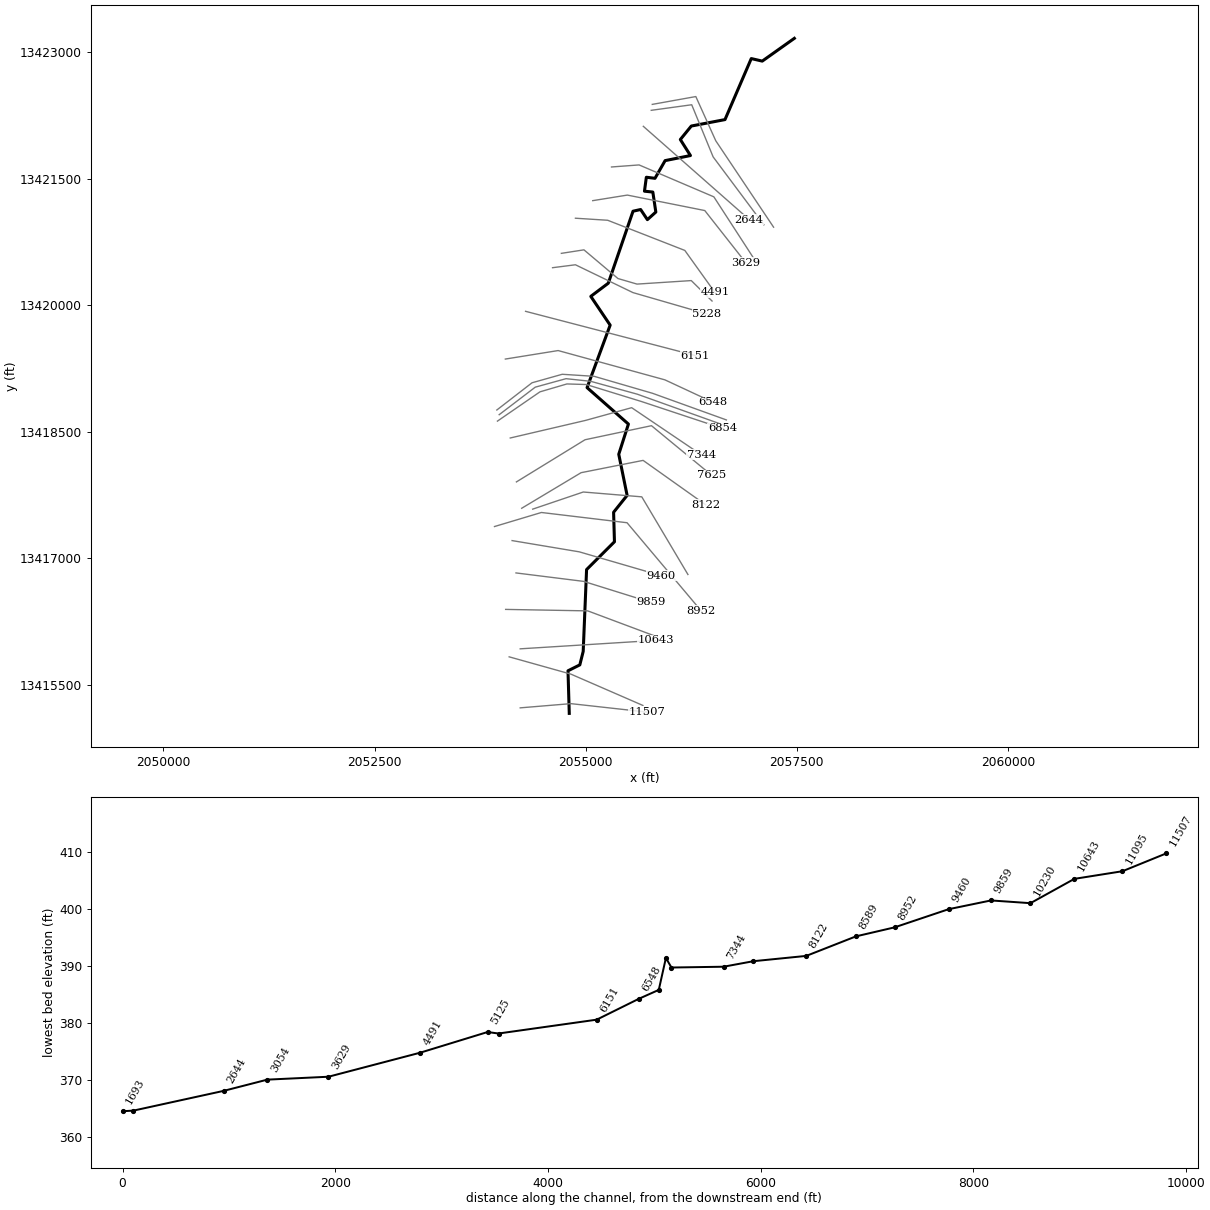
--- UNT 070 in RCW.prj (project) ---

Proj Title=UNT 070 in RCW Base Level Engineering
Current Plan=p01
Default Exp/Contr=0.3,0.1
English Units
Geom File=g01
Flow File=f01
Plan File=p01
BEGIN DESCRIPTION:
UNT 070 in RCW
END DESCRIPTION:

--- UNT 070 in RCW.p01 (plan) ---

Plan Title=Multiple Run
Short Identifier=Multiple
Geom File=g01
Flow File=f01
Subcritical Flow
K Sum by GR= 0
Std Step Tol= 0.01
Critical Tol= 0.01
Num of Std Step Trials= 20
Max Error Tol= 0.3
Flow Tol Ratio= 0.001
Split Flow NTrial= 30
Split Flow Tol= 0.02
Split Flow Ratio= 0.02
Log Output Level= 0
Friction Slope Method= 1
Unsteady Friction Slope Method= 2
Unsteady Bridges Friction Slope Method= 1
Parabolic Critical Depth
Global Vel Dist=  1 , 1 , 1
Global Log Level= 0
CheckData=True
Encroach Param= -1, 0, 0, 0
BEGIN DESCRIPTION:
Multiple Run
END DESCRIPTION:

--- UNT 070 in RCW.f01 (steady flow) ---

Flow Title=Multiple
Number of Profiles=7
Profile Names=10-year,25-year,50-year,1pct_min,100-year,1pct_plu,500-year
River Rch & RM= UNT 070 in RCW,Reach-1,11507
     175     239     292     178     354     707     531
River Rch & RM= UNT 070 in RCW,Reach-1,10643
     233     322     394     241     481     959     726
Boundary for River Rch & Prof#=UNT 070 in RCW,Reach-1,1
Up Type=0
Dn Type=3
Dn Slope=0.005
Boundary for River Rch & Prof#=UNT 070 in RCW,Reach-1,2
Up Type=0
Dn Type=3
Dn Slope=0.005
Boundary for River Rch & Prof#=UNT 070 in RCW,Reach-1,3
Up Type=0
Dn Type=3
Dn Slope=0.005
Boundary for River Rch & Prof#=UNT 070 in RCW,Reach-1,4
Up Type=0
Dn Type=3
Dn Slope=0.005
Boundary for River Rch & Prof#=UNT 070 in RCW,Reach-1,5
Up Type=0
Dn Type=3
Dn Slope=0.005
Boundary for River Rch & Prof#=UNT 070 in RCW,Reach-1,6
Up Type=0
Dn Type=3
Dn Slope=0.005
Boundary for River Rch & Prof#=UNT 070 in RCW,Reach-1,7
Up Type=0
Dn Type=3
Dn Slope=0.005

--- UNT 070 in RCW.g01 (geometry) ---

Geom Title=Existing Conditions

River Reach=UNT 070 in RCW,Reach-1
Reach XY= 30
      2054805.80     13415159.54      2054790.80     13415664.54
      2054930.80     13415734.54      2054970.80     13415894.54
      2055010.80     13416864.54      2055340.80     13417194.54
      2055330.80     13417544.54      2055490.80     13417744.54
      2055391.79     13418232.24      2055506.19     13418590.26
      2055016.60     13419022.55      2055290.04     13419763.44
      2055060.80     13420104.54      2055267.91     13420260.84
      2055560.80     13421114.54      2055650.80     13421134.54
      2055730.80     13421014.54      2055830.80     13421104.54
      2055795.25     13421341.56      2055696.29     13421351.98
      2055718.43     13421517.35      2055820.80     13421504.54
      2055940.80     13421714.54      2056240.80     13421774.54
      2056120.80     13421964.54      2056250.80     13422124.54
      2056649.67     13422200.98      2056960.80     13422924.54
      2057090.80     13422894.54      2057470.80     13423164.54

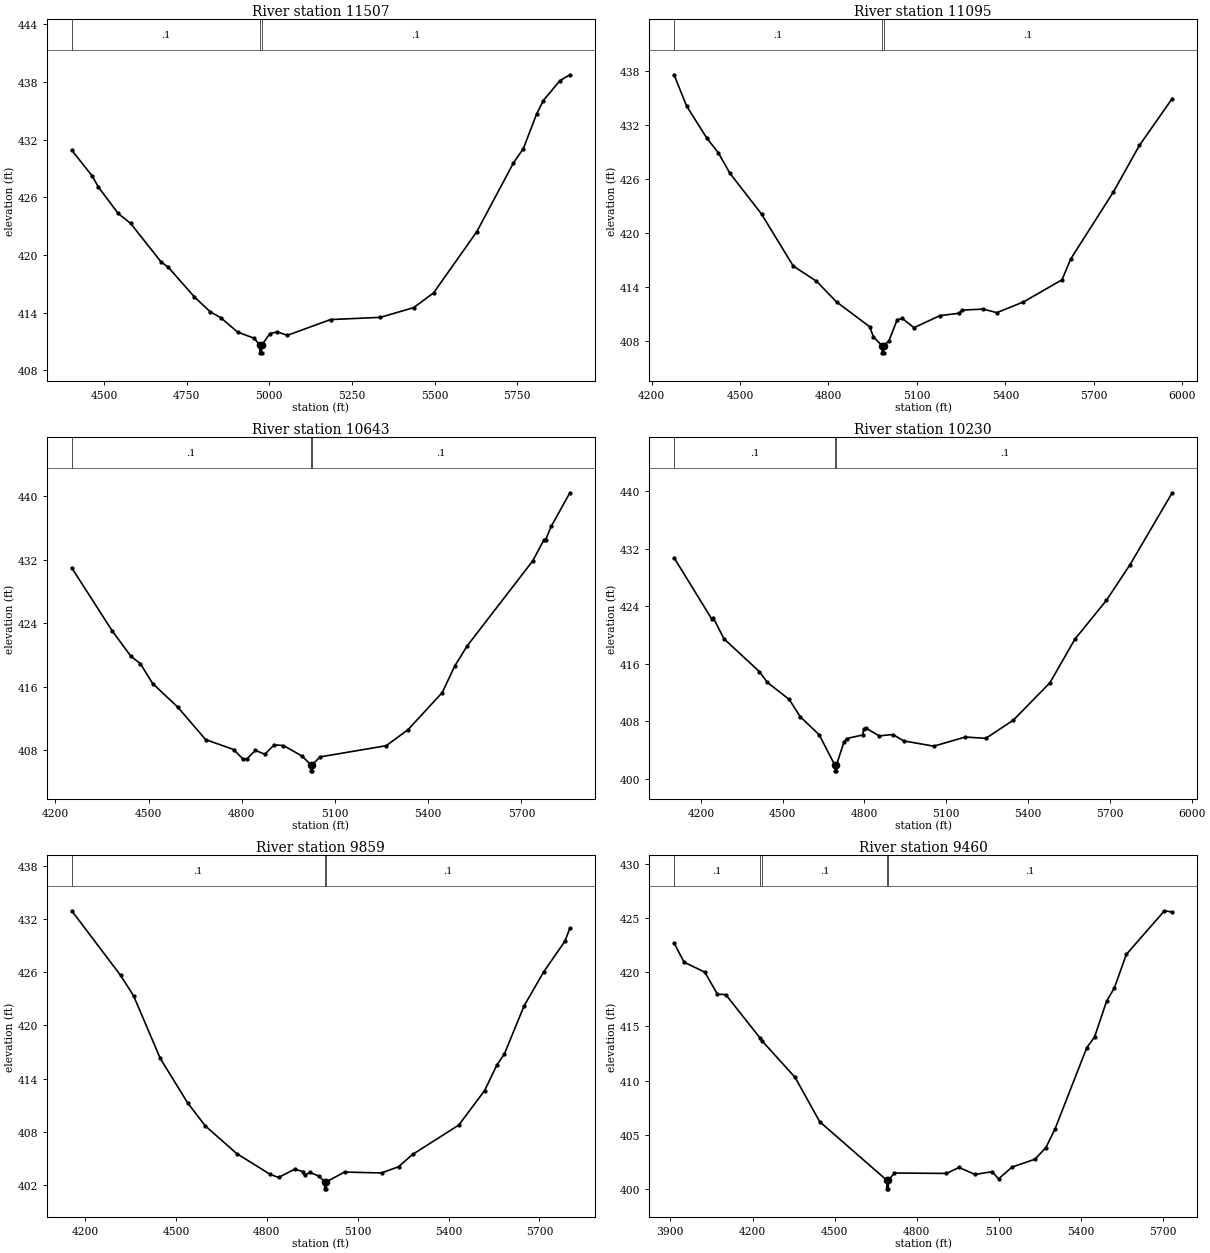
Type RM Length L Ch R = 1,11507,412,412,412
BEGIN DESCRIPTION:
UNT 070 in RCW 14.0
END DESCRIPTION:
XS GIS Cut Line= 3
      2054224.99     13415225.00      2054825.00     13415275.00
      2055724.97     13415175.00
#Sta/Elev= 30
  4402.0  430.90  4464.7  428.18  4482.3  427.08  4542.5  424.32  4580.1  423.29
  4672.9  419.26  4693.0  418.77  4773.3  415.64  4821.0  414.10  4853.6  413.47
  4903.7  411.99  4953.9  411.35  4971.0  410.63  4971.5  409.83  4976.5  409.83
  4977.0  410.63  5001.6  411.83  5024.2  412.01  5054.4  411.65  5185.2  413.29
  5336.1  413.52  5436.7  414.53  5497.1  416.06  5627.9  422.43  5738.6  429.56
  5768.8  431.07  5809.0  434.67  5829.1  436.06  5879.4  438.13  5909.6  438.74
#Mann=3,-1,0
  4402.0     0.1       0  4971.0    0.07       0  4977.0     0.1       0
Bank Sta=4971,4977
Exp/Cntr=0.3,0.1

Type RM Length L Ch R = 1,11095,452,452,452
BEGIN DESCRIPTION:
UNT 070 in RCW 13.0
END DESCRIPTION:
XS GIS Cut Line= 3
      2054094.19     13415830.03      2054825.00     13415625.00
      2055677.51     13415253.64
#Sta/Elev= 30
  4276.5  437.54  4318.9  434.08  4387.0  430.54  4426.3  428.90  4465.6  426.63
  4573.1  422.09  4680.5  416.33  4759.1  414.65  4827.3  412.35  4939.9  409.59
  4952.4  408.47  4981.4  407.50  4981.9  406.70  4986.9  406.70  4987.4  407.50
  5004.4  407.99  5032.9  410.36  5050.0  410.52  5090.1  409.49  5178.0  410.83
  5242.8  411.09  5253.7  411.44  5324.0  411.55  5370.9  411.16  5460.9  412.34
  5591.8  414.80  5621.5  417.12  5766.3  424.56  5854.2  429.70  5965.4  434.90
#Mann=3,-1,0
  4276.5     0.1       0  4981.4    0.07       0  4987.4     0.1       0
Bank Sta=4981.4,4987.4
Exp/Cntr=0.3,0.1

Type RM Length L Ch R = 1,10643,413,413,413
BEGIN DESCRIPTION:
UNT 070 in RCW 12.0
END DESCRIPTION:
XS GIS Cut Line= 3
      2054224.95     13415925.00      2055025.00     13415975.00
      2055825.03     13416025.00
#Sta/Elev= 30
  4252.7  430.97  4383.0  423.02  4443.1  419.81  4473.2  418.90  4513.3  416.37
  4593.4  413.42  4683.6  409.30  4773.8  408.05  4803.8  406.85  4816.3  406.87
  4843.9  407.94  4874.0  407.45  4904.0  408.64  4934.1  408.55  4994.2  407.22
  5021.2  406.16  5021.7  405.36  5026.8  405.36  5027.3  406.16  5051.8  407.12
  5264.7  408.53  5334.9  410.55  5445.1  415.24  5485.1  418.57  5525.2  421.12
  5735.6  431.82  5773.2  434.55  5778.2  434.55  5795.8  436.21  5855.9  440.45
#Mann=3,-1,0
  4252.7     0.1       0  5021.2    0.07       0  5027.3     0.1       0
Bank Sta=5021.2,5027.3
Exp/Cntr=0.3,0.1

Type RM Length L Ch R = 1,10230,371,371,371
BEGIN DESCRIPTION:
UNT 070 in RCW 11.0
END DESCRIPTION:
XS GIS Cut Line= 3
      2054052.54     13416392.53      2055025.00     13416375.00
      2055824.99     13416075.00
#Sta/Elev= 30
  4101.6  430.72  4240.5  422.16  4245.5  422.37  4284.1  419.47  4414.1  414.90
  4444.1  413.38  4524.1  411.01  4564.1  408.63  4634.1  406.09  4691.1  401.89
  4691.6  401.09  4696.7  401.09  4697.2  401.89  4724.2  405.04  4734.2  405.58
  4793.0  406.07  4798.0  406.95  4804.2  407.05  4854.2  405.95  4904.2  406.14
  4944.2  405.25  5054.2  404.52  5169.4  405.79  5245.1  405.61  5345.7  408.13
  5480.1  413.33  5571.7  419.39  5687.4  424.80  5772.9  429.69  5928.6  439.75
#Mann=3,-1,0
  4101.6     0.1       0  4691.1    0.07       0  4697.2     0.1       0
Bank Sta=4691.1,4697.2
Exp/Cntr=0.3,0.1

Type RM Length L Ch R = 1,9859,399,399,399
BEGIN DESCRIPTION:
UNT 070 in RCW 10.0
END DESCRIPTION:
XS GIS Cut Line= 3
      2054175.03     13416825.00      2054975.00     13416725.00
      2055774.96     13416475.01
#Sta/Elev= 30
  4156.3  432.90  4317.5  425.62  4360.3  423.32  4448.5  416.26  4539.2  411.24
  4597.2  408.66  4700.5  405.55  4811.3  403.20  4839.0  402.85  4891.9  403.78
  4919.7  403.52  4924.7  403.10  4942.3  403.42  4973.0  402.99  4990.9  402.37
  4991.4  401.57  4996.5  401.57  4997.0  402.37  5056.8  403.46  5178.8  403.36
  5234.9  404.06  5281.5  405.45  5434.0  408.76  5519.3  412.65  5559.7  415.53
  5584.3  416.76  5649.3  422.18  5714.2  426.02  5784.4  429.48  5800.6  430.95
#Mann=3,-1,0
  4156.3     0.1       0  4990.9    0.07       0  4997.0     0.1       0
Bank Sta=4990.9,4997
Exp/Cntr=0.3,0.1

Type RM Length L Ch R = 1,9460,508,508,508
BEGIN DESCRIPTION:
UNT 070 in RCW 9.0
END DESCRIPTION:
XS GIS Cut Line= 3
      2054128.88     13417208.51      2054925.00     13417075.00
      2055896.23     13416791.85
#Sta/Elev= 30
  3913.5  422.69  3950.1  420.93  4025.8  420.01  4071.8  417.98  4102.2  417.94
  4228.7  413.90  4235.0  413.67  4355.7  410.30  4445.3  406.22  4689.9  400.83
  4690.4  400.03  4695.5  400.03  4696.0  400.83  4718.2  401.49  4908.2  401.45
  4954.0  402.00  5012.4  401.36  5074.9  401.61  5098.4  400.95  5147.8  402.04
  5231.1  402.76  5271.1  403.83  5304.1  405.52  5420.6  413.05  5448.9  414.03
  5492.8  417.33  5521.1  418.55  5565.0  421.65  5704.2  425.67  5732.4  425.55
#Mann=5,-1,0
  3913.5     0.1       0  4228.7    0.08       0  4235.0     0.1       0
  4689.9    0.07       0  4696.0     0.1       0
Bank Sta=4689.9,4696
Exp/Cntr=0.3,0.1

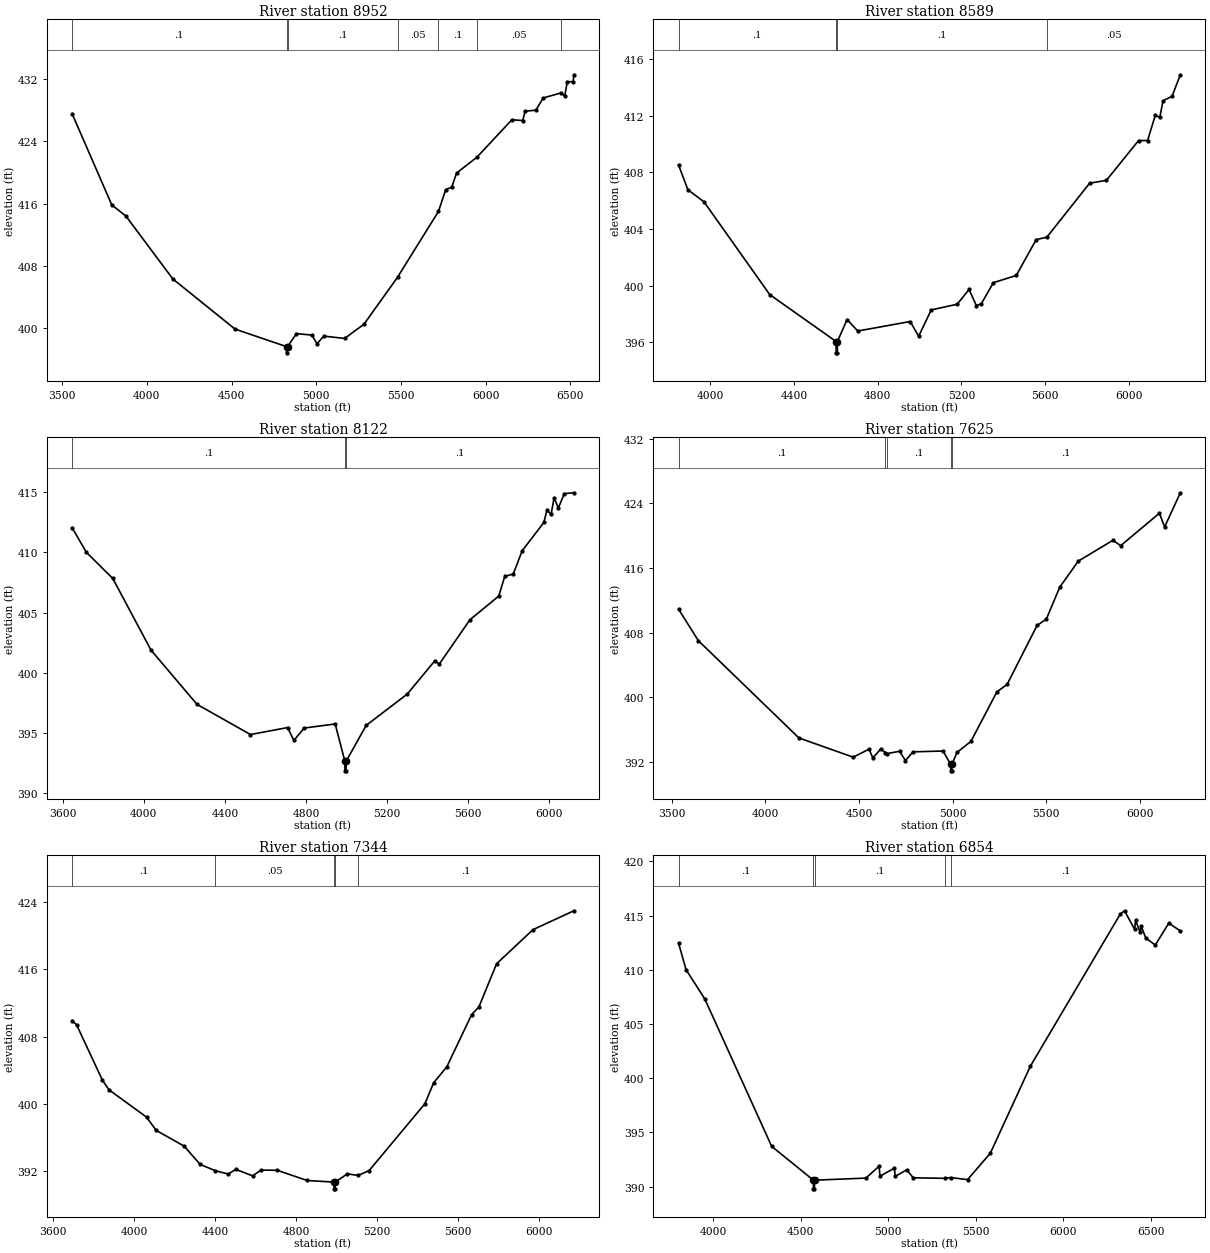
Type RM Length L Ch R = 1,8952,363,363,363
BEGIN DESCRIPTION:
Mapping XS 3d2dcf59
END DESCRIPTION:
XS GIS Cut Line= 4
      2053920.58     13417375.17      2054476.12     13417541.84
      2055490.01     13417420.31      2056364.46     13416379.29
#Sta/Elev= 30
  3559.2  427.58  3793.5  415.85  3877.0  414.41  4153.9  406.33  4520.8  399.89
  4824.4  397.64  4824.9  396.84  4830.5  397.64  4883.4  399.31  4974.0  399.12
  5004.2  398.01  5044.5  398.99  5167.3  398.69  5281.5  400.52  5479.5  406.55
  5721.0  415.01  5764.1  417.82  5799.2  418.12  5827.8  419.94  5946.5  421.95
  6154.3  426.79  6218.1  426.69  6232.4  427.88  6296.1  428.03  6339.0  429.59
  6442.6  430.23  6466.5  429.85  6480.8  431.68  6516.0  431.68  6519.9  432.57
#Mann=7,-1,0
  3559.2     0.1       0  4824.4    0.07       0  4830.5     0.1       0
  5479.5    0.05       0  5721.0     0.1       0  5946.5    0.05       0
  6442.6     0.1       0
Bank Sta=4824.4,4830.5
Exp/Cntr=0.3,0.1

Type RM Length L Ch R = 1,8589,467,467,467
BEGIN DESCRIPTION:
Mapping XS 2ebab660
END DESCRIPTION:
XS GIS Cut Line= 4
      2054372.79     13417581.47      2054971.75     13417784.60
      2055664.45     13417727.31      2056210.66     13416806.56
#Sta/Elev= 30
  3848.1  408.52  3892.7  406.77  3970.0  405.91  4284.0  399.37  4601.0  396.06
  4601.5  395.26  4606.9  395.26  4607.4  396.06  4653.5  397.61  4704.6  396.80
  4955.4  397.47  4995.6  396.43  5055.8  398.29  5179.9  398.69  5236.4  399.73
  5271.3  398.60  5294.6  398.71  5352.7  400.21  5462.0  400.72  5557.5  403.25
  5608.3  403.42  5812.8  407.23  5892.7  407.43  6046.7  410.24  6089.6  410.24
  6126.6  412.02  6148.0  411.88  6163.7  413.05  6206.5  413.36  6246.2  414.88
#Mann=4,-1,0
  3848.1     0.1       0  4601.0    0.07       0  4607.4     0.1       0
  5608.3    0.05       0
Bank Sta=4601,4607.4
Exp/Cntr=0.3,0.1

Type RM Length L Ch R = 1,8122,497,497,497
BEGIN DESCRIPTION:
Mapping XS c56fb251
END DESCRIPTION:
XS GIS Cut Line= 4
      2054242.61     13417591.91      2054945.70     13418013.76
      2055680.08     13418159.60      2056419.63     13417633.58
#Sta/Elev= 30
  3646.1  412.06  3716.6  410.01  3847.1  407.83  4035.3  401.88  4262.7  397.36
  4526.5  394.85  4710.0  395.43  4740.6  394.36  4791.6  395.39  4944.5  395.73
  4992.3  392.63  4992.8  391.83  4998.2  391.83  4998.7  392.63  5097.4  395.61
  5300.4  398.22  5436.9  401.00  5457.8  400.70  5609.1  404.39  5751.8  406.37
  5781.3  408.01  5823.1  408.20  5867.4  410.14  5974.3  412.49  5989.1  413.50
  6010.0  413.17  6024.8  414.54  6045.7  413.69  6075.2  414.89  6122.3  414.96
#Mann=3,-1,0
  3646.1     0.1       0  4992.3    0.07       0  4998.7     0.1       0
Bank Sta=4992.3,4998.7
Exp/Cntr=0.3,0.1

Type RM Length L Ch R = 1,7625,281,281,281
BEGIN DESCRIPTION:
Mapping XS d104287a
END DESCRIPTION:
XS GIS Cut Line= 4
      2054180.08     13417904.39      2054992.58     13418404.39
      2055779.04     13418571.06      2056491.27     13417983.59
#Sta/Elev= 30
  3535.6  410.90  3641.5  407.00  4178.6  394.97  4469.0  392.59  4553.4  393.58
  4573.9  392.50  4616.5  393.61  4641.0  393.16  4647.0  393.02  4717.0  393.32
  4747.7  392.17  4788.5  393.25  4948.9  393.35  4989.7  391.70  4990.2  390.90
  4995.7  390.90  4996.2  391.70  5023.6  393.18  5097.9  394.54  5236.7  400.67
  5291.0  401.58  5451.4  408.88  5500.9  409.67  5572.6  413.62  5671.6  416.84
  5856.6  419.41  5898.2  418.75  6105.0  422.76  6132.8  421.06  6216.8  425.29
#Mann=5,-1,0
  3535.6     0.1       0  4641.0    0.05       0  4647.0     0.1       0
  4989.7    0.07       0  4996.2     0.1       0
Bank Sta=4989.7,4996.2
Exp/Cntr=0.3,0.1

Type RM Length L Ch R = 1,7344,490,490,490
BEGIN DESCRIPTION:
Mapping XS 78aa75fe
END DESCRIPTION:
XS GIS Cut Line= 4
      2054107.15     13418425.22      2054997.79     13418633.56
      2055544.66     13418784.60      2056367.58     13418227.30
#Sta/Elev= 30
  3695.0  409.89  3717.2  409.40  3844.7  402.82  3877.7  401.67  4062.3  398.44
  4109.9  396.87  4247.7  395.00  4327.5  392.82  4401.2  392.09  4465.3  391.68
  4502.6  392.24  4586.3  391.47  4627.5  392.16  4707.2  392.13  4854.9  390.92
  4987.4  390.73  4987.9  389.93  4993.4  389.93  4993.9  390.73  5052.9  391.71
  5107.0  391.52  5160.8  392.10  5436.0  400.03  5479.4  402.53  5543.9  404.40
  5666.7  410.61  5702.6  411.52  5789.5  416.63  5969.2  420.68  6170.9  422.92
#Mann=5,-1,0
  3695.0     0.1       0  4401.2    0.05       0  4987.4   0.033       0
  4993.9    0.05       0  5107.0     0.1       0
Bank Sta=4987.4,4993.9
Exp/Cntr=0.3,0.1

Type RM Length L Ch R = 1,6854,52,52,52
BEGIN DESCRIPTION:
Mapping XS cfe9d48e
END DESCRIPTION:
XS GIS Cut Line= 6
      2053955.31     13418625.19      2054458.76     13418972.39
      2054778.20     13419066.14      2055007.37     13419059.20
      2055660.14     13418857.81      2056620.94     13418538.70
#Sta/Elev= 30
  3800.9  412.46  3843.8  410.01  3951.3  407.30  4333.4  393.71  4572.1  390.59
  4572.6  389.79  4578.1  389.79  4578.6  390.59  4872.2  390.78  4947.7  391.88
  4952.7  390.96  5034.8  391.69  5040.0  390.94  5105.3  391.54  5143.2  390.81
  5325.0  390.76  5357.6  390.83  5453.6  390.64  5583.5  393.07  5812.6  401.10
  6326.7  415.13  6351.0  415.44  6409.0  413.73  6414.3  414.56  6440.7  413.44
  6446.0  414.05  6472.4  412.93  6527.0  412.28  6604.3  414.30  6670.2  413.58
#Mann=5,-1,0
  3800.9     0.1       0  4572.1    0.07       0  4578.6     0.1       0
  5325.0    0.05       0  5357.6     0.1       0
Bank Sta=4572.1,4578.6
Exp/Cntr=0.3,0.1

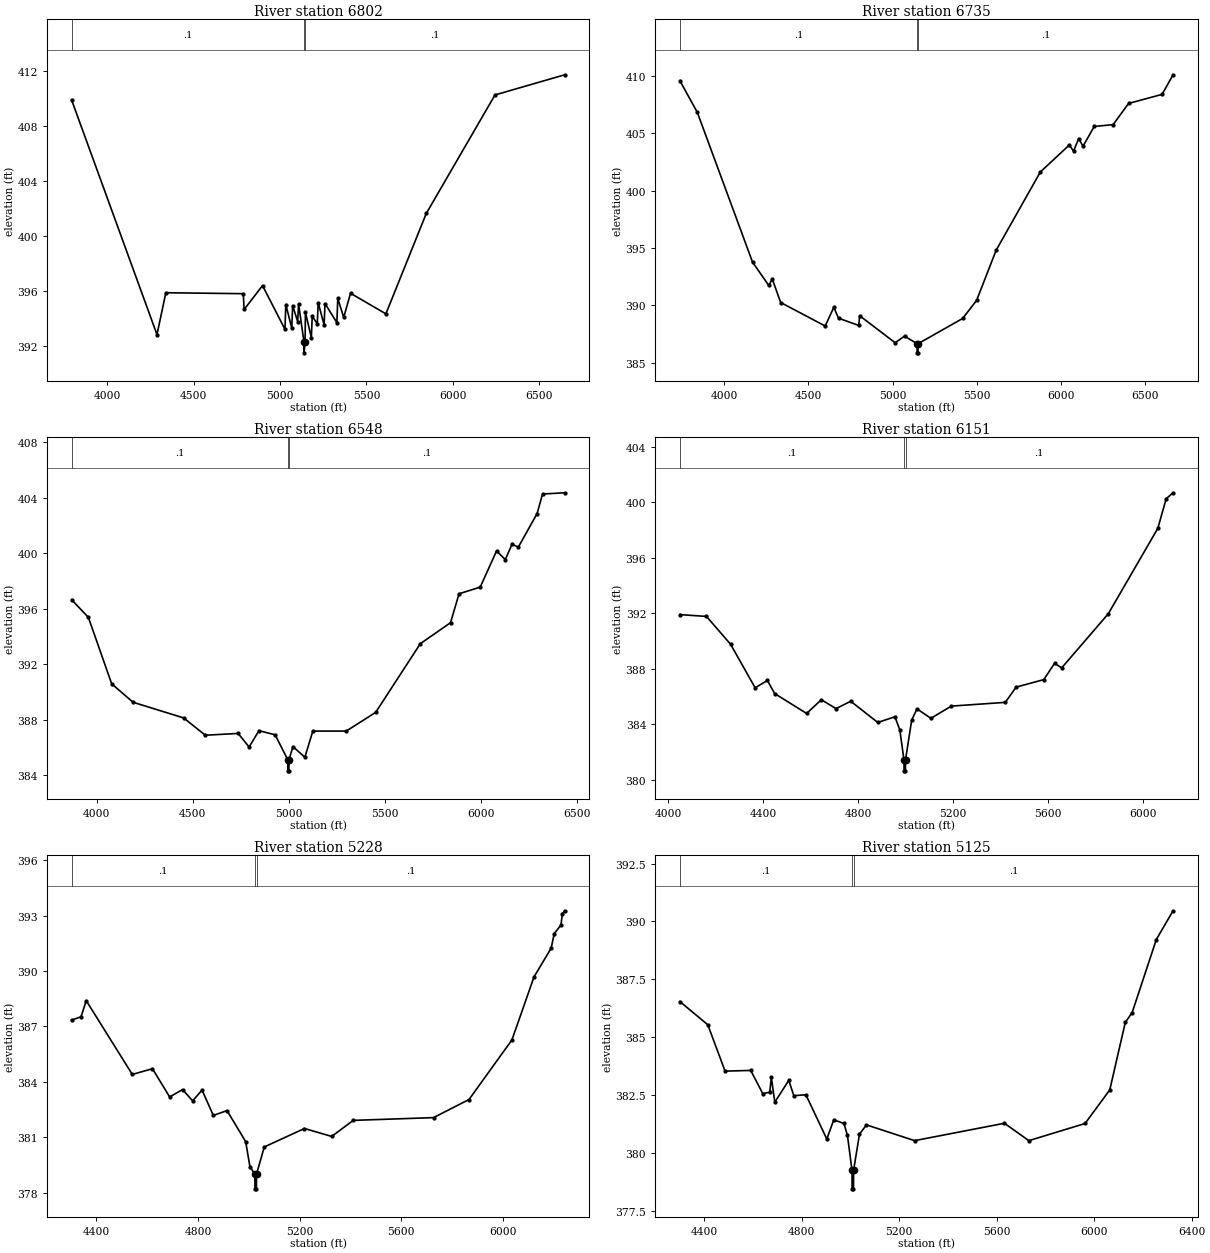
Type RM Length L Ch R = 1,6802,67,67,67
BEGIN DESCRIPTION:
Mapping XS b5c7f9fc
END DESCRIPTION:
XS GIS Cut Line= 6
      2053976.10     13418701.55      2054403.20     13419027.95
      2054767.78     13419128.64      2055059.45     13419097.39
      2055611.53     13418944.61      2056618.50     13418583.50
#Sta/Elev= 30
  3795.1  409.89  4288.7  392.80  4340.0  395.85  4787.7  395.78  4792.8  394.63
  4899.2  396.37  5028.7  393.19  5033.9  394.99  5068.2  393.27  5073.4  394.91
  5102.5  393.75  5107.7  395.04  5138.8  392.27  5139.3  391.47  5145.3  392.27
  5147.2  394.41  5181.5  392.58  5186.7  394.13  5215.8  393.59  5221.0  395.12
  5255.3  393.51  5260.5  395.06  5329.2  393.67  5334.3  395.43  5368.7  394.05
  5408.2  395.81  5612.6  394.31  5846.3  401.63  6243.6  410.26  6646.8  411.73
#Mann=3,-1,0
  3795.1     0.1       0  5138.8    0.07       0  5145.3     0.1       0
Bank Sta=5138.8,5145.3
Exp/Cntr=0.3,0.1

Type RM Length L Ch R = 1,6735,187,187,187
BEGIN DESCRIPTION:
Mapping XS 1e607176
END DESCRIPTION:
XS GIS Cut Line= 6
      2053948.38     13418757.14      2054365.01     13419080.03
      2054722.64     13419180.73      2055101.12     13419156.42
      2055792.09     13418955.03      2056665.75     13418639.54
#Sta/Elev= 30
  3737.4  409.59  3840.3  406.84  4168.1  393.77  4264.5  391.74  4285.3  392.29
  4335.1  390.25  4599.3  388.20  4650.4  389.83  4678.5  388.88  4798.6  388.25
  4803.6  389.10  5014.7  386.74  5070.1  387.32  5144.3  386.66  5144.8  385.86
  5150.3  385.86  5150.8  386.66  5415.2  388.86  5498.1  390.44  5614.2  394.82
  5876.3  401.64  6048.0  403.99  6073.4  403.46  6104.0  404.56  6129.4  403.88
  6196.0  405.61  6308.1  405.77  6400.1  407.62  6598.8  408.41  6663.9  410.12
#Mann=3,-1,0
  3737.4     0.1       0  5144.3    0.07       0  5150.8     0.1       0
Bank Sta=5144.3,5150.8
Exp/Cntr=0.3,0.1

Type RM Length L Ch R = 1,6548,397,397,397
BEGIN DESCRIPTION:
Mapping XS 8e6fdbb4
END DESCRIPTION:
XS GIS Cut Line= 4
      2054049.05     13419361.28      2054674.03     13419461.98
      2055937.92     13419114.75      2056503.87     13418850.88
#Sta/Elev= 30
  3868.9  396.65  3956.0  395.38  4077.5  390.58  4188.9  389.25  4452.3  388.12
  4565.2  386.87  4736.1  387.00  4793.3  386.02  4844.6  387.20  4929.0  386.90
  4994.6  385.10  4995.1  384.30  5000.6  384.30  5001.1  385.10  5021.5  386.05
  5083.7  385.28  5125.2  387.17  5299.2  387.17  5452.5  388.52  5685.2  393.48
  5842.3  394.99  5886.7  397.08  5997.0  397.56  6082.0  400.17  6127.7  399.55
  6162.5  400.65  6195.6  400.45  6293.3  402.87  6321.7  404.28  6437.1  404.37
#Mann=3,-1,0
  3868.9     0.1       0  4994.6    0.07       0  5001.1     0.1       0
Bank Sta=4994.6,5001.1
Exp/Cntr=0.3,0.1

Type RM Length L Ch R = 1,6151,923,923,923
BEGIN DESCRIPTION:
Mapping XS f4b545bd
END DESCRIPTION:
XS GIS Cut Line= 2
      2054288.59     13419927.26      2056299.05     13419402.94
#Sta/Elev= 30
  4048.7  391.90  4160.3  391.77  4262.0  389.76  4365.4  386.62  4417.0  387.15
  4448.0  386.20  4582.4  384.77  4644.4  385.76  4706.4  385.12  4768.4  385.65
  4882.1  384.12  4954.4  384.53  4975.1  383.58  4992.5  381.43  4993.0  380.63
  4998.6  380.63  4999.1  381.43  5025.1  384.29  5047.4  385.10  5106.0  384.42
  5192.2  385.30  5419.5  385.57  5465.2  386.67  5581.5  387.21  5627.1  388.38
  5657.2  388.06  5853.5  391.96  6062.1  398.12  6097.4  400.26  6126.4  400.69
#Mann=3,-1,0
  4048.7     0.1       0  4992.5    0.07       0  4999.1     0.1       0
Bank Sta=4992.5,4999.1
Exp/Cntr=0.3,0.1

Type RM Length L Ch R = 1,5228,103,103,103
BEGIN DESCRIPTION:
Mapping XS 2ad5cad3
END DESCRIPTION:
XS GIS Cut Line= 4
      2054608.09     13420444.62      2054878.89     13420479.34
      2055559.45     13420149.48      2056434.47     13419896.00
#Sta/Elev= 30
  4303.0  387.34  4340.2  387.53  4360.4  388.40  4541.8  384.40  4621.0  384.71
  4688.8  383.18  4739.5  383.58  4779.1  382.97  4816.2  383.55  4860.6  382.18
  4914.5  382.44  4987.8  380.76  5004.8  379.39  5024.0  379.00  5024.5  378.20
  5030.1  378.20  5030.6  379.00  5061.1  380.47  5219.1  381.47  5326.5  381.04
  5411.0  381.91  5727.1  382.06  5866.7  383.04  6035.6  386.27  6122.6  389.69
  6189.8  391.24  6202.2  392.03  6228.6  392.50  6233.8  393.10  6243.3  393.27
#Mann=3,-1,0
  4303.0     0.1       0  5024.0    0.07       0  5030.6     0.1       0
Bank Sta=5024,5030.6
Exp/Cntr=0.3,0.1

Type RM Length L Ch R = 1,5125,634,634,634
BEGIN DESCRIPTION:
Mapping XS 685fc23d
END DESCRIPTION:
XS GIS Cut Line= 6
      2054712.27     13420614.76      2054979.59     13420656.42
      2055382.37     13420316.14      2055608.06     13420250.17
      2056250.42     13420291.84      2056496.33     13420049.39
#Sta/Elev= 30
  4301.5  386.54  4415.6  385.54  4486.4  383.54  4591.6  383.57  4641.0  382.57
  4669.6  382.63  4676.1  383.27  4690.4  382.20  4747.6  383.14  4768.4  382.48
  4817.9  382.52  4903.6  380.61  4932.2  381.44  4973.9  381.28  4988.2  380.77
  5006.9  379.26  5007.4  378.46  5013.0  378.46  5013.5  379.26  5037.6  380.82
  5066.2  381.22  5263.7  380.54  5632.0  381.29  5732.2  380.54  5962.7  381.28
  6064.0  382.73  6127.6  385.64  6155.9  386.07  6254.9  389.22  6323.5  390.46
#Mann=3,-1,0
  4301.5     0.1       0  5006.9    0.07       0  5013.5     0.1       0
Bank Sta=5006.9,5013.5
Exp/Cntr=0.3,0.1

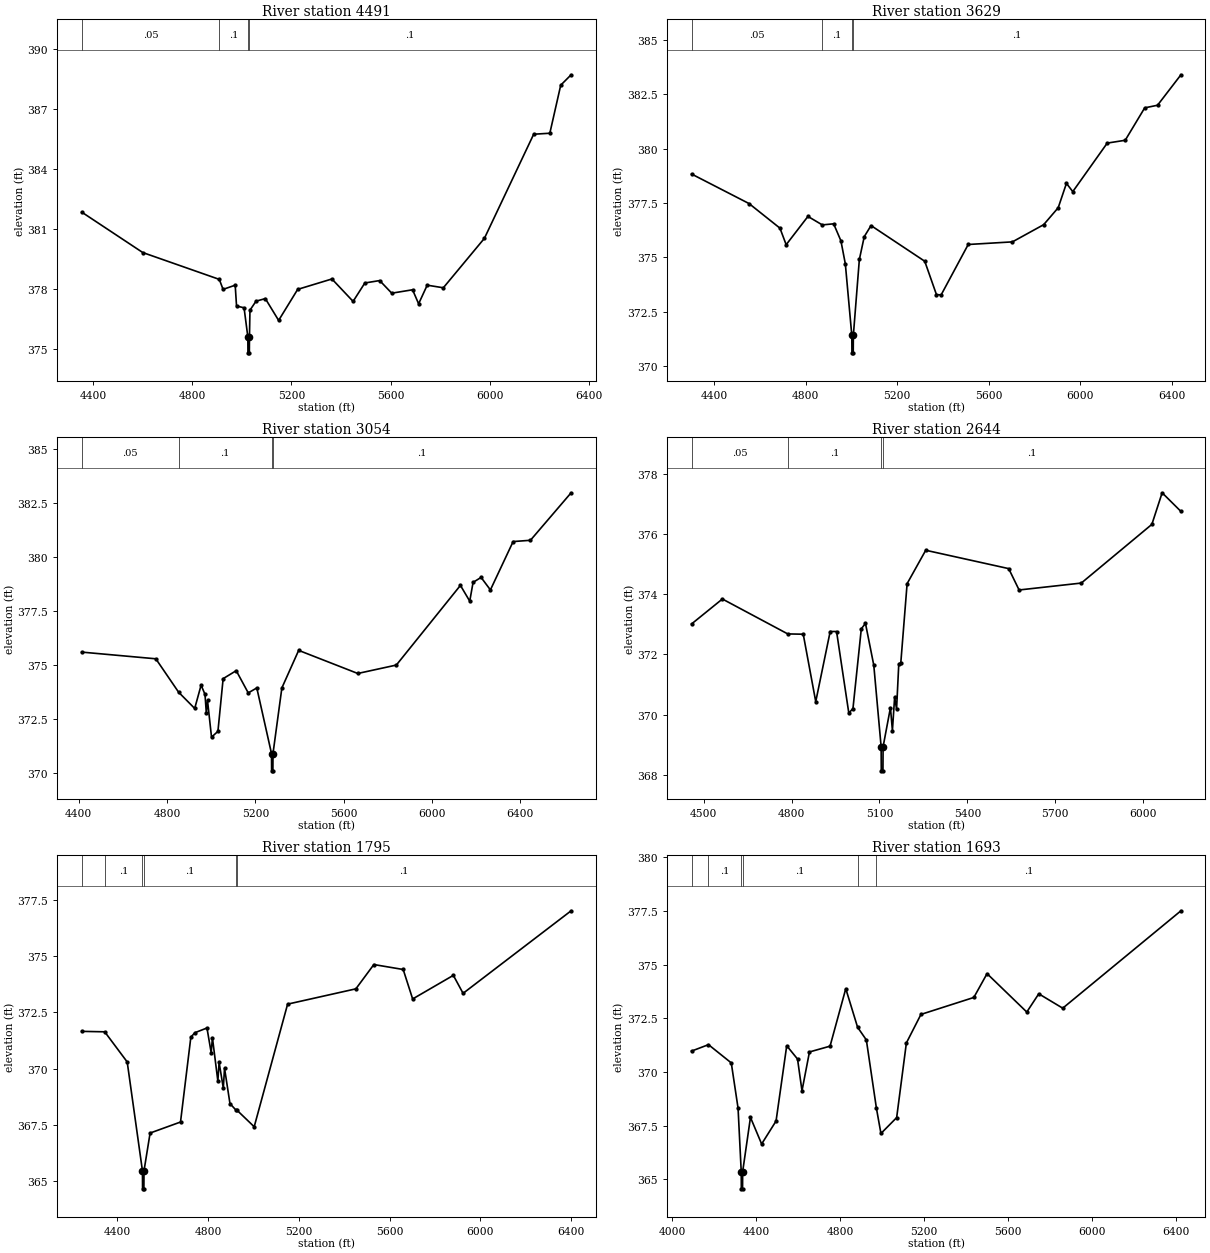
Type RM Length L Ch R = 1,4491,862,862,862
BEGIN DESCRIPTION:
Mapping XS 18ccfbb5
END DESCRIPTION:
XS GIS Cut Line= 4
      2054878.85     13421031.42      2055260.84     13421007.11
      2056174.03     13420649.48      2056530.67     13420150.88
#Sta/Elev= 30
  4352.9  381.86  4599.5  379.84  4908.5  378.50  4923.9  378.00  4972.8  378.21
  4978.2  377.17  5008.6  377.08  5023.8  375.63  5024.3  374.83  5029.9  374.83
  5030.4  375.63  5032.4  376.96  5056.9  377.41  5094.5  377.54  5148.2  376.45
  5225.1  378.00  5363.4  378.52  5448.9  377.40  5496.4  378.32  5556.3  378.44
  5605.0  377.81  5689.1  377.98  5713.5  377.28  5748.2  378.21  5813.3  378.08
  5979.2  380.55  6178.2  385.75  6243.4  385.80  6287.4  388.20  6329.4  388.72
#Mann=4,-1,0
  4352.9    0.05       0  4908.5     0.1       0  5023.8    0.07       0
  5030.4     0.1       0
Bank Sta=5023.8,5030.4
Exp/Cntr=0.3,0.1

Type RM Length L Ch R = 1,3629,575,575,575
BEGIN DESCRIPTION:
UNT 070 in RCW 2.0
END DESCRIPTION:
XS GIS Cut Line= 4
      2055083.77     13421239.75      2055493.48     13421305.73
      2056410.28     13421122.37      2056896.25     13420503.65
#Sta/Elev= 30
  4302.2  378.83  4553.5  377.47  4688.3  376.34  4715.4  375.58  4810.5  376.88
  4873.1  376.49  4922.7  376.54  4954.4  375.76  4973.7  374.70  5002.0  371.41
  5002.5  370.61  5008.2  370.61  5008.7  371.41  5034.9  374.90  5056.3  375.95
  5085.9  376.46  5320.4  374.82  5371.4  373.29  5391.8  373.27  5510.2  375.59
  5703.1  375.71  5839.5  376.50  5903.1  377.28  5939.0  378.40  5966.7  378.02
  6117.1  380.25  6195.6  380.38  6280.7  381.87  6336.7  381.99  6438.9  383.39
#Mann=4,-1,0
  4302.2    0.05       0  4873.1     0.1       0  5002.0    0.07       0
  5008.7     0.1       0
Bank Sta=5002,5008.7
Exp/Cntr=0.3,0.1

Type RM Length L Ch R = 1,3054,410,410,410
BEGIN DESCRIPTION:
Mapping XS 71596baa
END DESCRIPTION:
XS GIS Cut Line= 4
      2055305.97     13421639.06      2055632.37     13421663.36
      2056517.78     13421284.89      2057021.24     13420507.13
#Sta/Elev= 30
  4413.4  375.60  4749.1  375.29  4852.5  373.74  4925.2  372.99  4954.2  374.07
  4971.9  373.64  4977.8  372.78  4983.2  373.36  5001.4  371.66  5030.4  371.93
  5054.0  374.37  5113.3  374.74  5167.7  373.71  5206.5  373.94  5273.1  370.90
  5273.6  370.10  5279.3  370.10  5279.8  370.90  5320.0  373.94  5396.1  375.68
  5663.8  374.61  5838.5  375.00  6128.7  378.69  6170.9  377.96  6186.0  378.83
  6222.3  379.06  6264.5  378.48  6367.4  380.72  6445.9  380.78  6630.1  382.98
#Mann=4,-1,0
  4413.4    0.05       0  4852.5     0.1       0  5273.1    0.07       0
  5279.8     0.1       0
Bank Sta=5273.1,5279.8
Exp/Cntr=0.3,0.1

Type RM Length L Ch R = 1,2644,849,849,849
BEGIN DESCRIPTION:
Mapping XS c1ced7ee
END DESCRIPTION:
XS GIS Cut Line= 2
      2055682.57     13422121.16      2056936.15     13421015.82
#Sta/Elev= 30
  4458.1  373.01  4563.5  373.84  4786.7  372.68  4839.6  372.67  4882.3  370.43
  4931.6  372.76  4953.4  372.76  4995.2  370.05  5009.4  370.20  5037.9  372.85
  5052.1  373.03  5080.5  371.64  5105.6  368.93  5106.1  368.13  5111.8  368.13
  5112.3  368.93  5137.4  370.23  5144.1  369.47  5151.7  370.58  5158.3  370.18
  5165.9  371.69  5172.6  371.70  5194.3  374.35  5257.9  375.46  5541.2  374.85
  5576.7  374.14  5789.2  374.37  6030.1  376.32  6065.2  377.37  6129.4  376.75
#Mann=4,-1,0
  4458.1    0.05       0  4786.7     0.1       0  5105.6    0.07       0
  5112.3     0.1       0
Bank Sta=5105.6,5112.3
Exp/Cntr=0.3,0.1

Type RM Length L Ch R = 1,1795,102,102,102
BEGIN DESCRIPTION:
Mapping XS 9c45e321
END DESCRIPTION:
XS GIS Cut Line= 4
      2055776.42     13422310.93      2056255.63     13422376.91
      2056509.10     13421758.85      2057109.79     13420953.30
#Sta/Elev= 30
  4243.5  371.66  4344.9  371.64  4444.0  370.30  4511.2  365.46  4511.7  364.66
  4517.5  364.66  4518.0  365.46  4544.9  367.14  4678.9  367.63  4724.4  371.40
  4742.1  371.60  4795.5  371.81  4814.1  370.71  4819.5  371.38  4843.5  369.45
  4848.9  370.28  4867.5  369.14  4872.9  370.02  4896.8  368.45  4924.1  368.15
  4928.2  368.15  5003.6  367.42  5150.8  372.87  5451.6  373.55  5530.8  374.63
  5660.1  374.41  5701.8  373.10  5881.1  374.15  5924.0  373.35  6400.1  377.02
#Mann=6,-1,0
  4243.5    0.05       0  4344.9     0.1       0  4511.2    0.07       0
  4518.0     0.1       0  4924.1    0.08       0  4928.2     0.1       0
Bank Sta=4511.2,4518
Exp/Cntr=0.3,0.1

Type RM Length L Ch R = 1,1693,0,0,0
BEGIN DESCRIPTION:
UNT 070 in RCW 1.0
END DESCRIPTION:
XS GIS Cut Line= 4
      2055788.64     13422381.25      2056304.24     13422474.13
      2056540.35     13421949.82      2057225.00     13420924.99
#Sta/Elev= 30
  4092.7  370.97  4173.5  371.27  4282.1  370.42  4314.4  368.31  4329.5  365.35
  4330.0  364.55  4335.8  364.55  4336.3  365.35  4373.5  367.88  4426.7  366.64
  4495.4  367.71  4546.2  371.22  4597.7  370.60  4618.9  369.12  4654.5  370.93
  4752.6  371.20  4827.5  373.88  4883.8  372.08  4925.5  371.49  4973.6  368.30
  4995.0  367.13  5069.9  367.87  5116.2  371.35  5185.6  372.68  5437.5  373.47
  5500.5  374.58  5689.8  372.79  5746.8  373.64  5861.0  372.97  6424.1  377.51
#Mann=6,-1,0
  4092.7    0.05       0  4173.5     0.1       0  4329.5    0.07       0
  4336.3     0.1       0  4883.8    0.08       0  4973.6     0.1       0
Bank Sta=4329.5,4336.3
Exp/Cntr=0.3,0.1

Chan Stop Cuts=-1