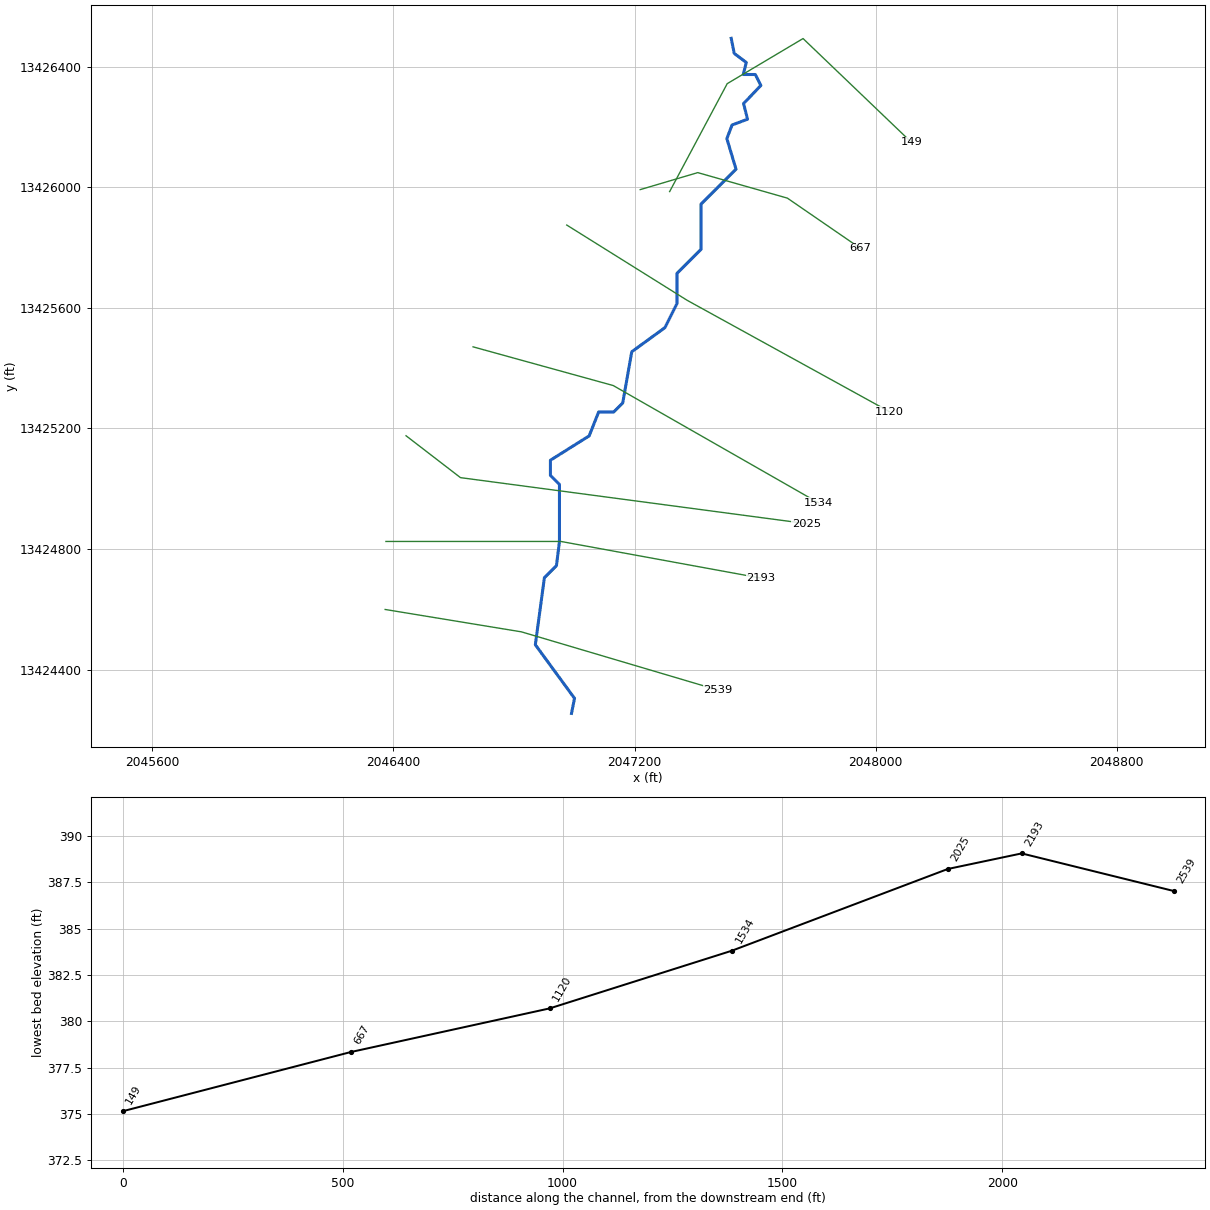
--- UNT 080 in RCW.prj (project) ---

Proj Title=UNT 080 in RCW Base Level Engineering
Current Plan=p01
Default Exp/Contr=0.3,0.1
English Units
Geom File=g01
Flow File=f01
Plan File=p01
BEGIN DESCRIPTION:
UNT 080 in RCW
END DESCRIPTION:

--- UNT 080 in RCW.p01 (plan) ---

Plan Title=Multiple Run
Short Identifier=Multiple
Geom File=g01
Flow File=f01
Subcritical Flow
K Sum by GR= 0
Std Step Tol= 0.01
Critical Tol= 0.01
Num of Std Step Trials= 20
Max Error Tol= 0.3
Flow Tol Ratio= 0.001
Split Flow NTrial= 30
Split Flow Tol= 0.02
Split Flow Ratio= 0.02
Log Output Level= 0
Friction Slope Method= 1
Unsteady Friction Slope Method= 2
Unsteady Bridges Friction Slope Method= 1
Parabolic Critical Depth
Global Vel Dist=  1 , 1 , 1
Global Log Level= 0
CheckData=True
Encroach Param= -1, 0, 0, 0
BEGIN DESCRIPTION:
Multiple Run
END DESCRIPTION:

--- UNT 080 in RCW.f01 (steady flow) ---

Flow Title=Multiple
Number of Profiles=7
Profile Names=10-year,25-year,50-year,1pct_min,100-year,1pct_plu,500-year
River Rch & RM= UNT 080 in RCW,Reach-1,2539
     113     151     180     108     216     431     313
River Rch & RM= UNT 080 in RCW,Reach-1,149
     536     766     960     599    1194    2383    1878
Boundary for River Rch & Prof#=UNT 080 in RCW,Reach-1,1
Up Type=0
Dn Type=3
Dn Slope=0.005
Boundary for River Rch & Prof#=UNT 080 in RCW,Reach-1,2
Up Type=0
Dn Type=3
Dn Slope=0.005
Boundary for River Rch & Prof#=UNT 080 in RCW,Reach-1,3
Up Type=0
Dn Type=3
Dn Slope=0.005
Boundary for River Rch & Prof#=UNT 080 in RCW,Reach-1,4
Up Type=0
Dn Type=3
Dn Slope=0.005
Boundary for River Rch & Prof#=UNT 080 in RCW,Reach-1,5
Up Type=0
Dn Type=3
Dn Slope=0.005
Boundary for River Rch & Prof#=UNT 080 in RCW,Reach-1,6
Up Type=0
Dn Type=3
Dn Slope=0.005
Boundary for River Rch & Prof#=UNT 080 in RCW,Reach-1,7
Up Type=0
Dn Type=3
Dn Slope=0.005

--- UNT 080 in RCW.g01 (geometry) ---

Geom Title=Existing Conditions

River Reach=UNT 080 in RCW,Reach-1
Reach XY= 30
      2046990.80     13424254.54      2047000.80     13424304.54
      2046870.80     13424482.23      2046900.80     13424704.54
      2046940.80     13424744.54      2046950.80     13424824.54
      2046950.80     13425014.54      2046920.80     13425044.54
      2046920.80     13425094.54      2047049.41     13425175.31
      2047080.80     13425254.54      2047130.80     13425254.54
      2047160.80     13425284.54      2047190.80     13425454.54
      2047300.80     13425534.54      2047340.80     13425614.54
      2047340.80     13425714.54      2047420.80     13425794.54
      2047420.80     13425944.54      2047536.71     13426060.35
      2047506.32     13426161.91      2047523.68     13426207.05
      2047574.90     13426226.15      2047561.88     13426278.23
      2047619.17     13426338.13      2047600.80     13426374.54
      2047560.80     13426374.54      2047570.80     13426414.54
      2047530.80     13426444.54      2047520.80     13426494.54

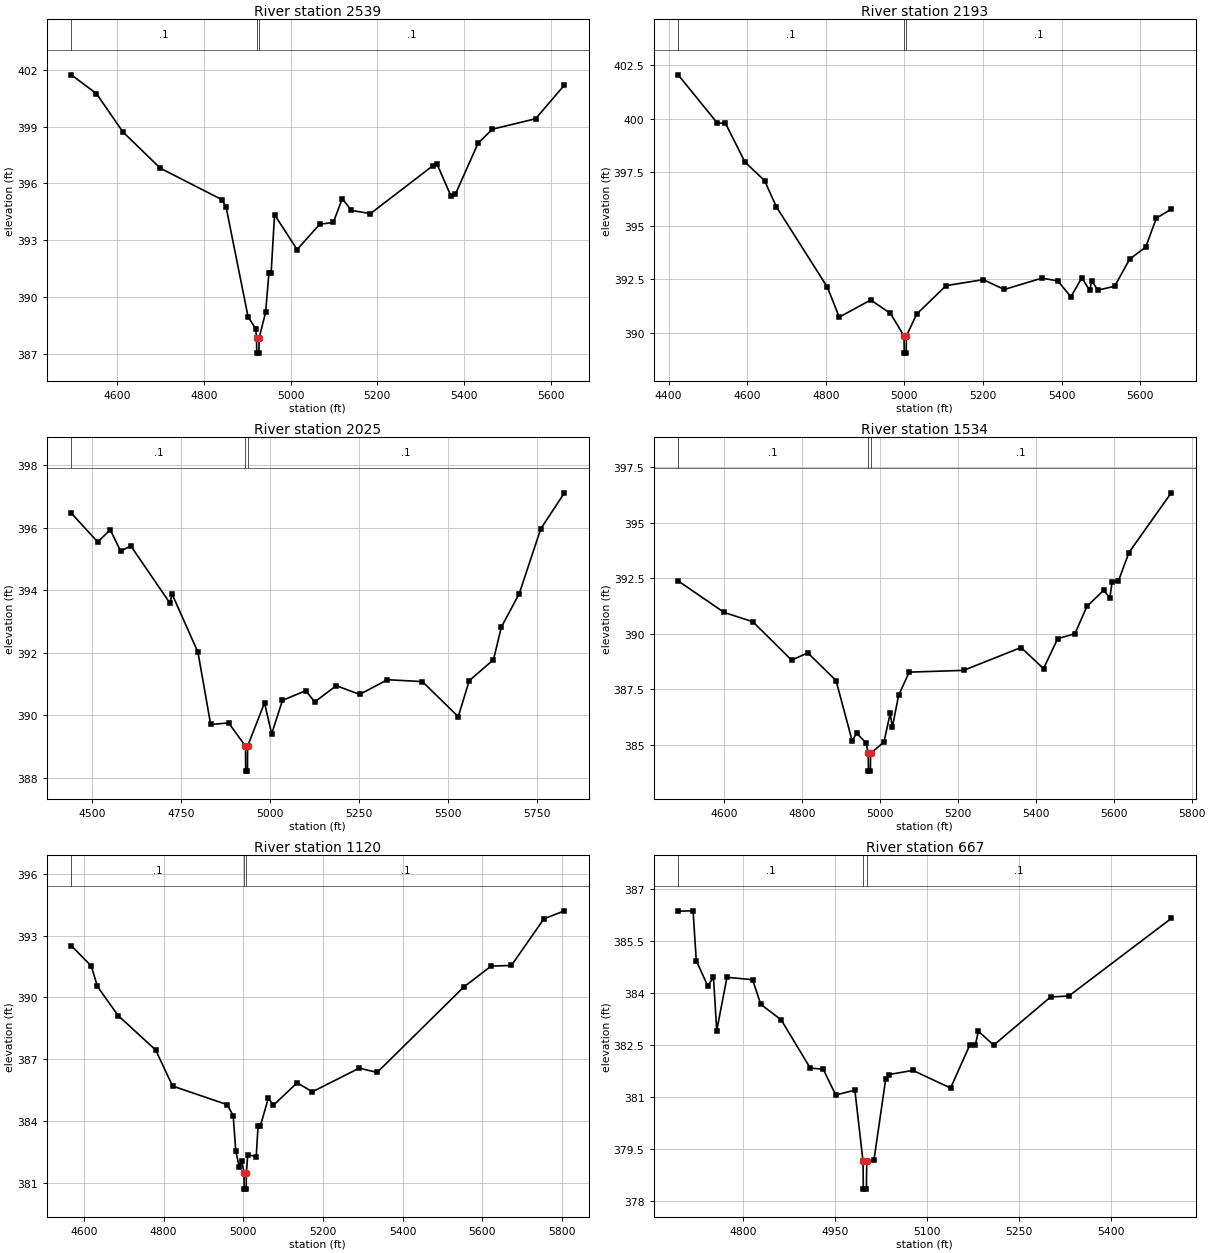
Type RM Length L Ch R = 1,2539,346,346,346
BEGIN DESCRIPTION:
UNT 080 in RCW 4.0
END DESCRIPTION:
XS GIS Cut Line= 3
      2046372.43     13424599.32      2046825.00     13424525.00
      2047476.57     13424331.96
#Sta/Elev= 30
  4493.6  401.73  4551.5  400.74  4612.8  398.71  4698.9  396.80  4840.8  395.14
  4850.9  394.74  4901.6  388.95  4919.1  388.32  4921.1  387.83  4921.6  387.03
  4926.6  387.03  4927.1  387.83  4942.1  389.19  4949.7  391.26  4954.8  391.26
  4962.7  394.34  5014.8  392.50  5067.0  393.84  5098.2  393.93  5119.1  395.19
  5140.0  394.57  5184.0  394.40  5327.7  396.92  5338.1  397.00  5369.4  395.35
  5379.9  395.41  5432.3  398.11  5465.6  398.86  5565.3  399.41  5631.8  401.19
#Mann=3,-1,0
  4493.6     0.1       0  4921.1    0.07       0  4927.1     0.1       0
Bank Sta=4921.1,4927.1
Exp/Cntr=0.3,0.1

Type RM Length L Ch R = 1,2193,168,168,168
BEGIN DESCRIPTION:
UNT 080 in RCW 3.0
END DESCRIPTION:
XS GIS Cut Line= 3
      2046375.00     13424825.00      2046955.72     13424825.02
      2047618.95     13424703.48
#Sta/Elev= 30
  4424.2  402.05  4524.2  399.79  4544.2  399.80  4594.2  397.98  4644.2  397.11
  4674.2  395.89  4804.2  392.13  4834.2  390.74  4914.2  391.54  4964.2  390.92
  4999.1  389.86  4999.6  389.06  5004.6  389.06  5005.1  389.86  5031.2  390.88
  5105.9  392.21  5200.8  392.49  5254.0  392.03  5349.9  392.56  5390.5  392.43
  5423.6  391.69  5451.5  392.57  5471.7  391.99  5476.8  392.44  5492.2  392.00
  5535.0  392.18  5573.5  393.45  5614.2  394.01  5641.3  395.36  5679.2  395.78
#Mann=3,-1,0
  4424.2     0.1       0  4999.1    0.07       0  5005.1     0.1       0
Bank Sta=4999.1,5005.1
Exp/Cntr=0.3,0.1

Type RM Length L Ch R = 1,2025,491,491,491
BEGIN DESCRIPTION:
Mapping XS e8b0202a
END DESCRIPTION:
XS GIS Cut Line= 3
      2046441.83     13425175.71      2046622.38     13425036.82
      2047770.88     13424884.15
#Sta/Elev= 30
  4440.9  396.46  4515.1  395.54  4550.4  395.93  4579.4  395.25  4608.4  395.41
  4718.6  393.58  4723.6  393.89  4796.9  392.02  4832.7  389.71  4883.2  389.76
  4930.6  389.02  4931.1  388.22  4936.1  388.22  4936.6  389.02  4984.1  390.40
  5004.2  389.41  5034.5  390.48  5100.0  390.79  5125.3  390.43  5185.8  390.95
  5251.5  390.67  5329.8  391.14  5427.9  391.08  5528.8  389.96  5559.7  391.11
  5627.9  391.78  5649.9  392.82  5700.3  393.89  5760.8  395.96  5827.3  397.11
#Mann=3,-1,0
  4440.9     0.1       0  4930.6    0.07       0  4936.6     0.1       0
Bank Sta=4930.6,4936.6
Exp/Cntr=0.3,0.1

Type RM Length L Ch R = 1,1534,414,414,414
BEGIN DESCRIPTION:
Mapping XS 31ff3465
END DESCRIPTION:
XS GIS Cut Line= 3
      2046664.08     13425470.84      2047129.33     13425342.38
      2047809.90     13424953.48
#Sta/Elev= 30
  4481.1  392.38  4599.2  390.96  4673.0  390.54  4772.5  388.81  4814.0  389.14
  4886.6  387.89  4928.1  385.17  4939.4  385.52  4963.8  385.08  4969.3  384.61
  4969.8  383.81  4974.8  383.81  4975.3  384.61  5009.7  385.12  5025.6  386.41
  5031.3  385.80  5047.2  387.22  5074.5  388.27  5214.2  388.35  5361.9  389.38
  5419.5  388.43  5456.0  389.78  5500.1  390.00  5530.9  391.23  5574.1  391.96
  5589.9  391.62  5595.7  392.34  5611.5  392.36  5638.9  393.66  5747.6  396.35
#Mann=3,-1,0
  4481.1     0.1       0  4969.3    0.07       0  4975.3     0.1       0
Bank Sta=4969.3,4975.3
Exp/Cntr=0.3,0.1

Type RM Length L Ch R = 1,1120,453,453,453
BEGIN DESCRIPTION:
UNT 080 in RCW 2.0
END DESCRIPTION:
XS GIS Cut Line= 3
      2046974.97     13425875.02      2047375.00     13425625.00
      2048045.99     13425255.57
#Sta/Elev= 30
  4568.6  392.51  4618.8  391.52  4634.1  390.53  4686.0  389.12  4780.3  387.45
  4822.8  385.70  4959.6  384.80  4974.9  384.27  4981.4  382.54  4990.2  381.78
  4996.1  382.08  5002.0  381.50  5002.5  380.70  5007.5  380.70  5008.0  381.50
  5011.4  382.37  5032.7  382.28  5037.4  383.77  5043.2  383.77  5063.2  385.12
  5075.9  384.77  5135.5  385.86  5173.4  385.42  5291.5  386.57  5336.2  386.36
  5554.0  390.51  5622.5  391.52  5673.3  391.55  5754.7  393.81  5806.3  394.20
#Mann=3,-1,0
  4568.6     0.1       0  5002.0    0.07       0  5008.0     0.1       0
Bank Sta=5002,5008
Exp/Cntr=0.3,0.1

Type RM Length L Ch R = 1,667,518,518,518
BEGIN DESCRIPTION:
Mapping XS f683da0f
END DESCRIPTION:
XS GIS Cut Line= 4
      2047218.80     13425992.52      2047409.81     13426048.96
      2047707.12     13425964.32      2047950.05     13425797.31
#Sta/Elev= 30
  4694.6  386.37  4718.9  386.38  4724.1  384.94  4742.8  384.21  4752.1  384.46
  4757.4  382.92  4774.1  384.46  4815.8  384.39  4829.1  383.68  4862.4  383.23
  4909.6  381.84  4931.0  381.80  4951.2  381.06  4982.4  381.20  4995.7  379.14
  4996.2  378.34  5001.2  378.34  5001.7  379.14  5013.5  379.18  5032.6  381.52
  5037.8  381.65  5076.9  381.77  5138.3  381.26  5169.5  382.50  5178.4  382.49
  5183.6  382.90  5208.5  382.50  5301.1  383.89  5330.9  383.92  5497.7  386.16
#Mann=3,-1,0
  4694.6     0.1       0  4995.7    0.07       0  5001.7     0.1       0
Bank Sta=4995.7,5001.7
Exp/Cntr=0.3,0.1

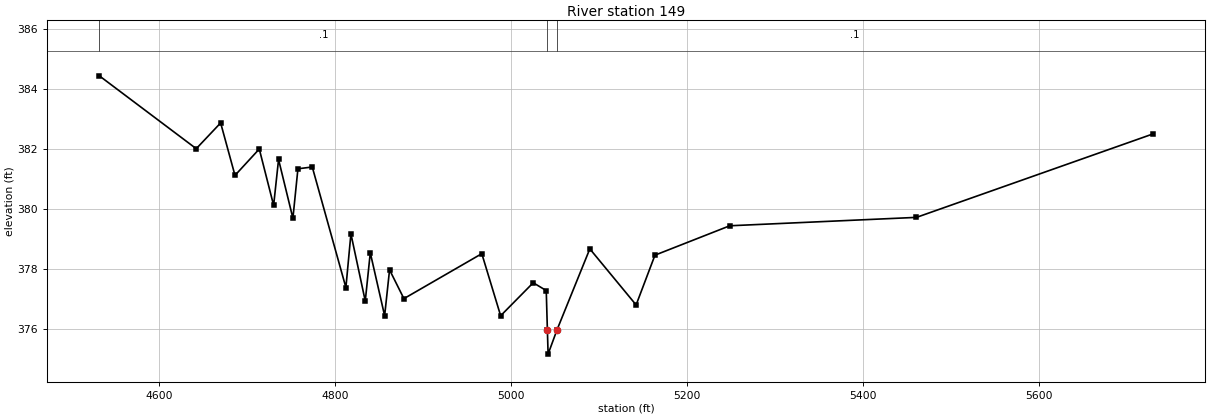
Type RM Length L Ch R = 1,149,0,0,0
BEGIN DESCRIPTION:
UNT 080 in RCW 1.0
END DESCRIPTION:
XS GIS Cut Line= 4
      2047316.48     13425986.00      2047507.47     13426344.10
      2047759.20     13426493.84      2048118.81     13426149.40
#Sta/Elev= 30
  4532.1  384.43  4642.2  382.00  4669.9  382.86  4686.2  381.11  4713.8  381.99
  4730.1  380.11  4735.7  381.64  4752.0  379.68  4757.7  381.33  4774.0  381.39
  4812.2  377.37  4817.9  379.16  4834.2  376.92  4839.9  378.53  4856.2  376.43
  4861.8  377.96  4878.1  377.00  4966.6  378.50  4988.0  376.43  5025.0  377.53
  5039.8  377.27  5041.1  375.95  5041.9  375.15  5051.9  375.95  5089.3  378.66
  5141.9  376.79  5163.3  378.45  5248.3  379.43  5460.4  379.71  5728.8  382.49
#Mann=3,-1,0
  4532.1     0.1       0  5041.1    0.07       0  5051.9     0.1       0
Bank Sta=5041.1,5051.9
Exp/Cntr=0.3,0.1

Chan Stop Cuts=-1