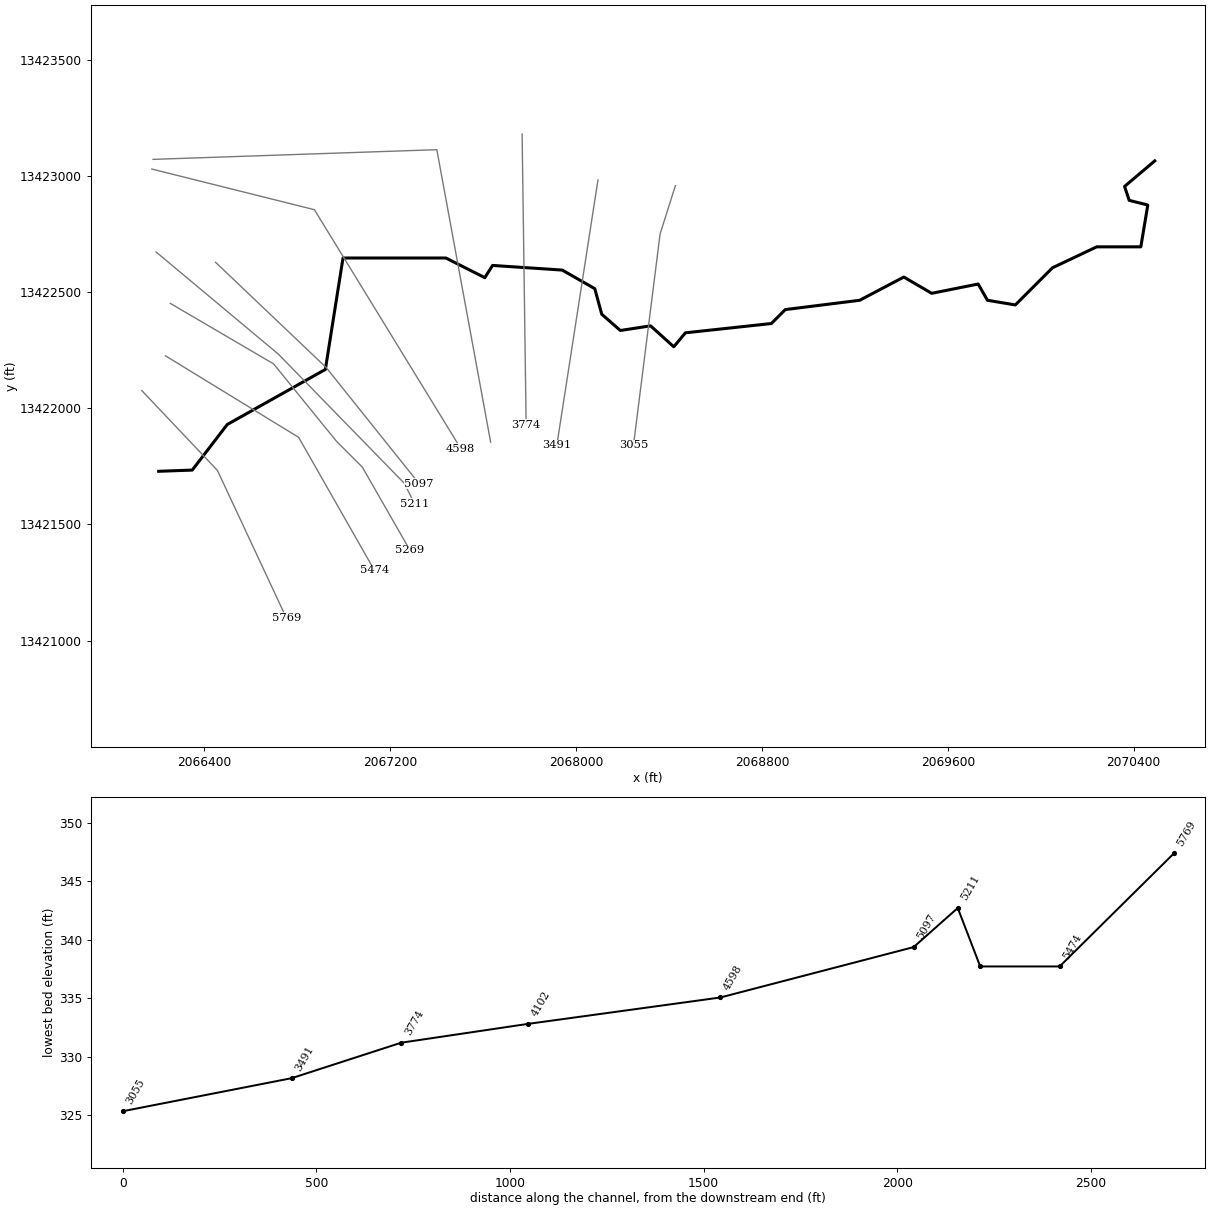
--- UNT 081 in RCW.prj (project) ---

Proj Title=UNT 081 in RCW Base Level Engineering
Current Plan=p01
Default Exp/Contr=0.3,0.1
English Units
Geom File=g01
Flow File=f01
Plan File=p01
BEGIN DESCRIPTION:
UNT 081 in RCW
END DESCRIPTION:

--- UNT 081 in RCW.p01 (plan) ---

Plan Title=Multiple Run
Short Identifier=Multiple
Geom File=g01
Flow File=f01
Subcritical Flow
K Sum by GR= 0
Std Step Tol= 0.01
Critical Tol= 0.01
Num of Std Step Trials= 20
Max Error Tol= 0.3
Flow Tol Ratio= 0.001
Split Flow NTrial= 30
Split Flow Tol= 0.02
Split Flow Ratio= 0.02
Log Output Level= 0
Friction Slope Method= 1
Unsteady Friction Slope Method= 2
Unsteady Bridges Friction Slope Method= 1
Parabolic Critical Depth
Global Vel Dist=  1 , 1 , 1
Global Log Level= 0
CheckData=True
Encroach Param= -1, 0, 0, 0
BEGIN DESCRIPTION:
Multiple Run
END DESCRIPTION:

--- UNT 081 in RCW.f01 (steady flow) ---

Flow Title=Multiple
Number of Profiles=7
Profile Names=10-year,25-year,50-year,1pct_min,100-year,1pct_plu,500-year
River Rch & RM= UNT 081 in RCW,Reach-1,5769
     137     186     225     136     271     542     401
Boundary for River Rch & Prof#=UNT 081 in RCW,Reach-1,1
Up Type=0
Dn Type=3
Dn Slope=0.005
Boundary for River Rch & Prof#=UNT 081 in RCW,Reach-1,2
Up Type=0
Dn Type=3
Dn Slope=0.005
Boundary for River Rch & Prof#=UNT 081 in RCW,Reach-1,3
Up Type=0
Dn Type=3
Dn Slope=0.005
Boundary for River Rch & Prof#=UNT 081 in RCW,Reach-1,4
Up Type=0
Dn Type=3
Dn Slope=0.005
Boundary for River Rch & Prof#=UNT 081 in RCW,Reach-1,5
Up Type=0
Dn Type=3
Dn Slope=0.005
Boundary for River Rch & Prof#=UNT 081 in RCW,Reach-1,6
Up Type=0
Dn Type=3
Dn Slope=0.005
Boundary for River Rch & Prof#=UNT 081 in RCW,Reach-1,7
Up Type=0
Dn Type=3
Dn Slope=0.005

--- UNT 081 in RCW.g01 (geometry) ---

Geom Title=Existing Conditions

River Reach=UNT 081 in RCW,Reach-1
Reach XY= 30
      2066203.92     13421728.59      2066348.45     13421733.80
      2066499.02     13421929.93      2066921.33     13422166.91
      2066997.28     13422646.51      2067439.99     13422646.51
      2067607.56     13422561.92      2067640.80     13422614.54
      2067940.80     13422594.54      2068080.80     13422514.54
      2068110.80     13422404.54      2068190.80     13422334.54
      2068320.80     13422354.54      2068420.80     13422264.54
      2068470.80     13422324.54      2068840.80     13422364.54
      2068900.80     13422424.54      2069220.80     13422464.54
      2069410.80     13422564.54      2069530.80     13422494.54
      2069730.80     13422534.54      2069770.80     13422464.54
      2069890.80     13422444.54      2070050.80     13422604.54
      2070240.80     13422694.54      2070430.80     13422694.54
      2070460.80     13422874.54      2070380.80     13422894.54
      2070360.80     13422954.54      2070490.80     13423064.54

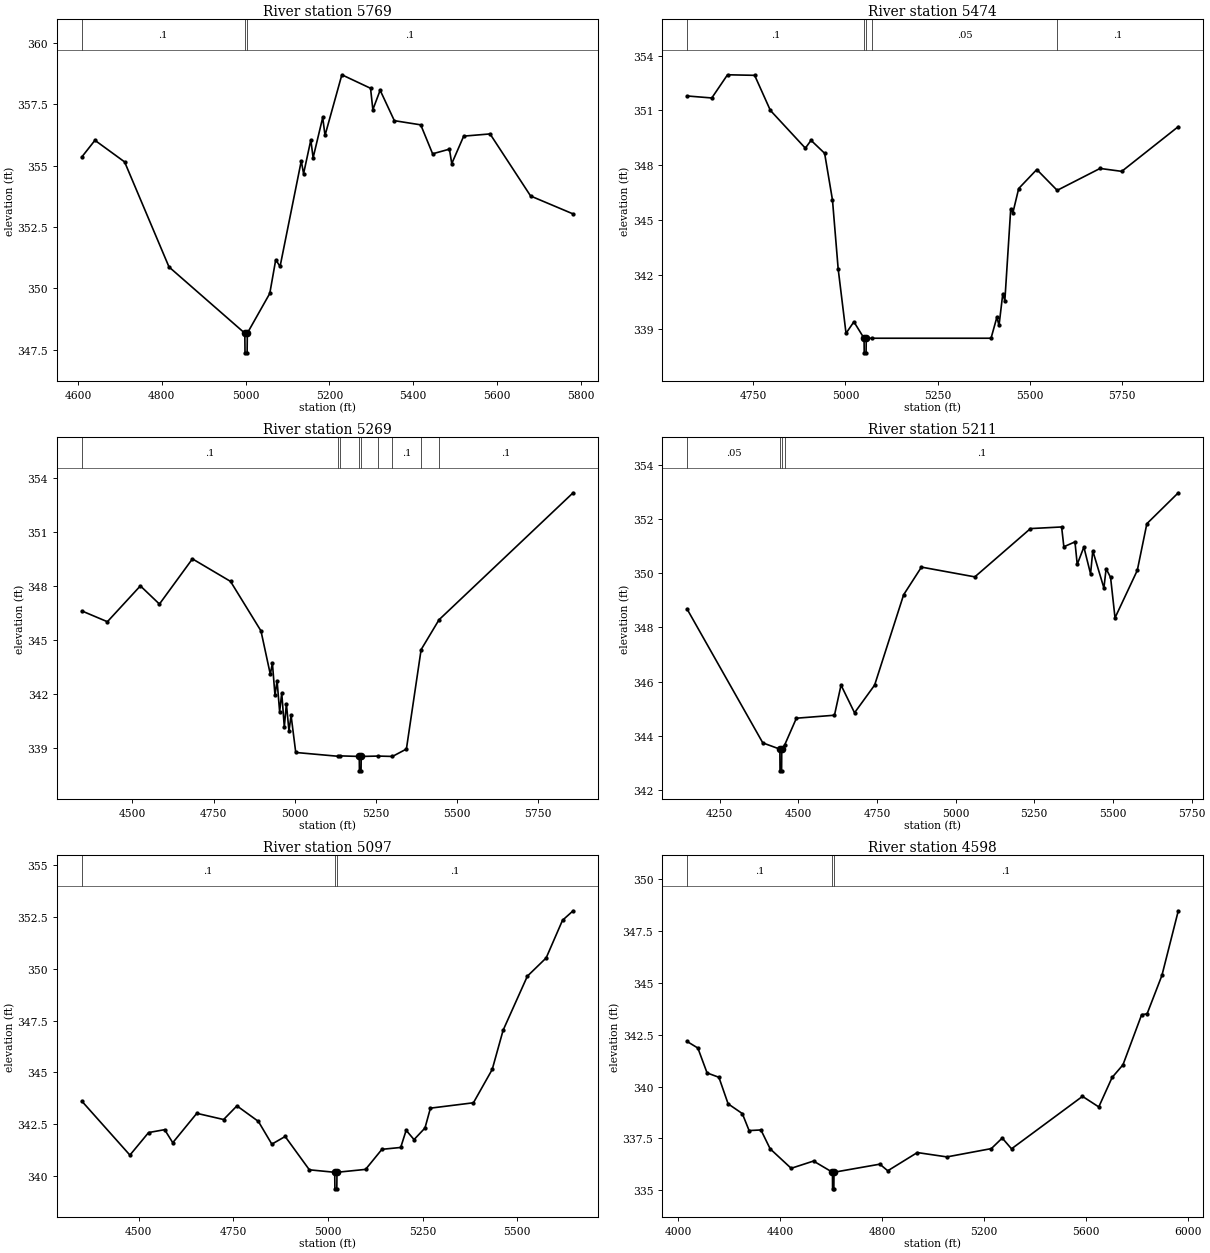
Type RM Length L Ch R = 1,5769,295,295,295
BEGIN DESCRIPTION:
UNT 081 in RCW 11.0
END DESCRIPTION:
XS GIS Cut Line= 3
      2066131.40     13422075.93      2066456.91     13421732.19
      2066753.04     13421098.36
#Sta/Elev= 30
  4608.9  355.35  4640.3  356.03  4711.1  355.15  4817.1  350.87  4998.1  348.17
  4998.6  347.37  5003.6  347.37  5004.1  348.17  5057.7  349.79  5071.9  351.16
  5082.3  350.89  5132.9  355.19  5138.4  354.67  5155.7  356.04  5161.2  355.32
  5184.1  356.96  5189.6  356.23  5229.8  358.70  5298.3  358.15  5303.8  357.28
  5321.2  358.07  5355.1  356.83  5418.1  356.66  5446.5  355.48  5486.6  355.67
  5492.2  355.08  5520.7  356.20  5583.6  356.29  5680.5  353.76  5781.9  353.03
#Mann=3,-1,0
  4608.9     0.1       0  4998.1    0.07       0  5004.1     0.1       0
Bank Sta=4998.1,5004.1
Exp/Cntr=0.3,0.1

Type RM Length L Ch R = 1,5474,205,205,205
BEGIN DESCRIPTION:
Mapping XS ae6321c5
END DESCRIPTION:
XS GIS Cut Line= 3
      2066233.35     13422225.49      2066806.30     13421874.77
      2067132.67     13421301.89
#Sta/Elev= 30
  4570.7  351.79  4637.9  351.68  4680.5  352.95  4754.0  352.92  4796.6  351.00
  4891.4  348.93  4906.8  349.36  4943.6  348.65  4964.9  346.09  4980.3  342.32
  5001.6  338.79  5022.9  339.42  5050.4  338.52  5050.9  337.72  5055.9  337.72
  5056.4  338.52  5071.1  338.52  5394.5  338.52  5410.3  339.67  5416.1  339.22
  5426.2  340.94  5431.9  340.58  5447.8  345.60  5453.5  345.38  5469.4  346.72
  5518.4  347.76  5573.7  346.62  5689.8  347.82  5748.6  347.66  5901.8  350.11
#Mann=5,-1,0
  4570.7     0.1       0  5050.4    0.07       0  5056.4     0.1       0
  5071.1    0.05       0  5573.7     0.1       0
Bank Sta=5050.4,5056.4
Exp/Cntr=0.3,0.1

Type RM Length L Ch R = 1,5269,58,58,58
BEGIN DESCRIPTION:
Mapping XS 699a47c9
END DESCRIPTION:
XS GIS Cut Line= 5
      2066254.22     13422451.16      2066698.66     13422190.74
      2066969.50     13421857.41      2067080.61     13421746.30
      2067285.07     13421389.35
#Sta/Elev= 30
  4344.0  346.60  4422.8  346.00  4524.4  347.99  4583.1  346.98  4684.7  349.49
  4802.0  348.24  4895.8  345.49  4924.6  343.08  4931.0  343.70  4939.0  341.91
  4945.4  342.73  4953.3  341.00  4959.8  342.04  4967.7  340.15  4974.1  341.44
  4982.1  339.93  4988.5  340.80  5002.9  338.74  5132.6  338.53  5140.4  338.55
  5198.5  338.52  5199.0  337.72  5204.0  337.72  5204.5  338.52  5256.6  338.54
  5300.8  338.52  5343.7  338.93  5389.0  344.45  5444.2  346.11  5857.1  353.16
#Mann=9,-1,0
  4344.0     0.1       0  5132.6    0.05       0  5140.4     0.1       0
  5198.5    0.07       0  5204.5     0.1       0  5256.6    0.05       0
  5300.8     0.1       0  5389.0    0.05       0  5444.2     0.1       0
Bank Sta=5198.5,5204.5
Exp/Cntr=0.3,0.1

Type RM Length L Ch R = 1,5211,114,114,114
BEGIN DESCRIPTION:
Mapping XS 9254cfb5
END DESCRIPTION:
XS GIS Cut Line= 4
      2066192.71     13422672.54      2066719.50     13422232.41
      2067261.16     13421676.85      2067305.45     13421588.28
#Sta/Elev= 30
  4146.2  348.68  4387.2  343.74  4441.4  343.51  4441.9  342.71  4446.9  342.71
  4447.4  343.51  4456.9  343.67  4493.9  344.65  4614.9  344.76  4635.8  345.87
  4678.7  344.85  4742.5  345.87  4834.7  349.20  4891.3  350.22  5061.0  349.86
  5237.8  351.64  5336.8  351.70  5343.9  350.97  5379.2  351.15  5386.4  350.32
  5407.5  350.96  5428.8  349.97  5435.8  350.82  5471.2  349.45  5478.2  350.16
  5492.4  349.84  5506.5  348.35  5577.3  350.10  5607.7  351.82  5707.6  352.96
#Mann=4,-1,0
  4146.2    0.05       0  4441.4    0.07       0  4447.4    0.05       0
  4456.9     0.1       0
Bank Sta=4441.4,4447.4
Exp/Cntr=0.3,0.1

Type RM Length L Ch R = 1,5097,499,499,499
BEGIN DESCRIPTION:
UNT 081 in RCW 10.0
END DESCRIPTION:
XS GIS Cut Line= 3
      2066448.65     13422628.25      2066925.00     13422175.00
      2067324.97     13421675.04
#Sta/Elev= 30
  4349.7  343.61  4476.8  341.00  4526.1  342.09  4568.6  342.23  4590.0  341.60
  4653.5  343.02  4724.3  342.72  4759.5  343.38  4816.1  342.63  4851.7  341.53
  4886.9  341.90  4950.8  340.29  5017.8  340.17  5018.3  339.37  5023.3  339.37
  5023.8  340.17  5099.3  340.31  5142.5  341.28  5192.1  341.37  5206.5  342.20
  5227.3  341.75  5256.2  342.31  5270.6  343.27  5384.2  343.53  5433.8  345.14
  5462.7  347.04  5526.7  349.65  5576.3  350.53  5619.5  352.35  5647.5  352.81
#Mann=3,-1,0
  4349.7     0.1       0  5017.8    0.07       0  5023.8     0.1       0
Bank Sta=5017.8,5023.8
Exp/Cntr=0.3,0.1

Type RM Length L Ch R = 1,4598,496,496,496
BEGIN DESCRIPTION:
Mapping XS 7e58d337
END DESCRIPTION:
XS GIS Cut Line= 3
      2066174.44     13423029.34      2066874.20     13422854.39
      2067504.22     13421826.15
#Sta/Elev= 30
  4034.9  342.18  4077.6  341.86  4113.7  340.66  4160.1  340.45  4196.2  339.17
  4251.9  338.70  4278.6  337.88  4325.0  337.91  4361.1  337.00  4443.6  336.06
  4531.2  336.41  4605.5  335.87  4606.0  335.07  4611.0  335.07  4611.5  335.87
  4791.5  336.26  4822.4  335.94  4938.4  336.82  5054.5  336.61  5228.6  337.01
  5271.5  337.52  5307.9  337.00  5586.3  339.53  5650.2  339.02  5702.4  340.44
  5745.0  341.05  5818.4  343.47  5839.7  343.51  5897.8  345.36  5962.1  348.48
#Mann=3,-1,0
  4034.9     0.1       0  4605.5    0.07       0  4611.5     0.1       0
Bank Sta=4605.5,4611.5
Exp/Cntr=0.3,0.1

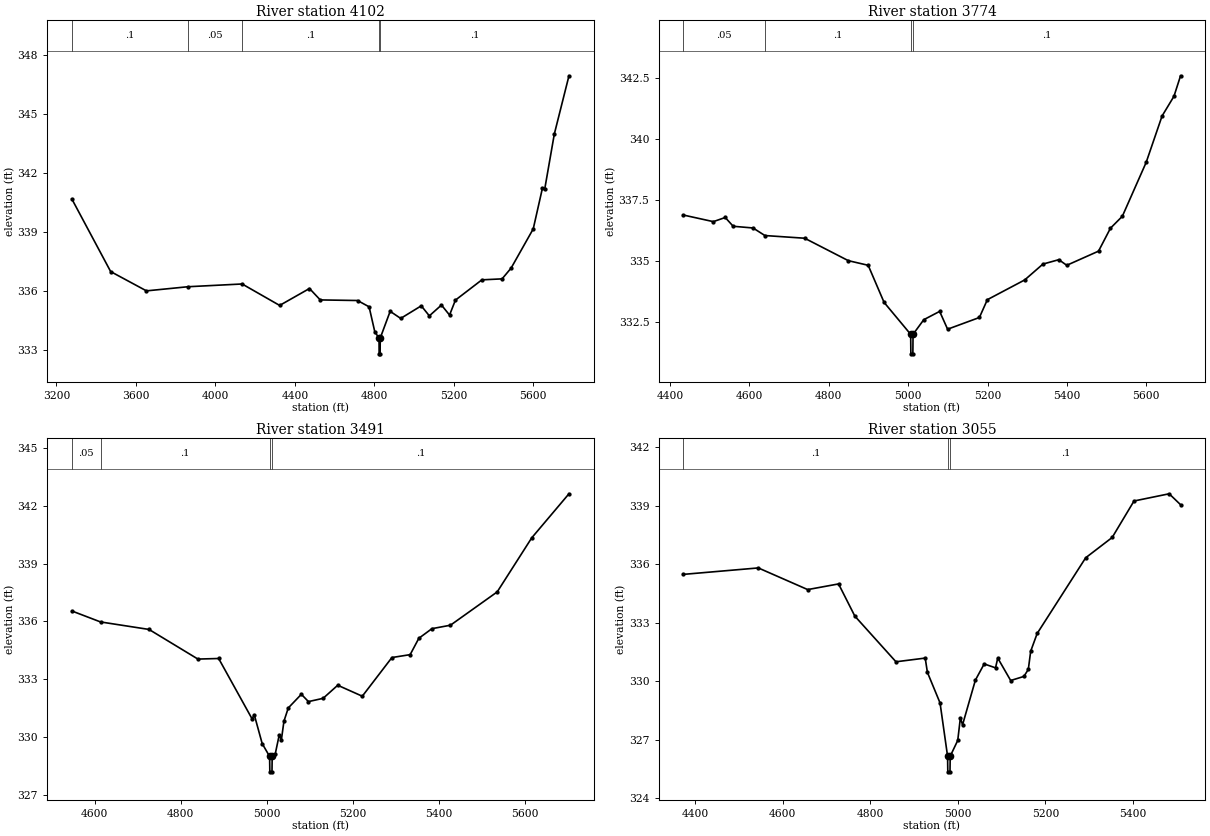
Type RM Length L Ch R = 1,4102,328,328,328
BEGIN DESCRIPTION:
UNT 081 in RCW 9.0
END DESCRIPTION:
XS GIS Cut Line= 3
      2066179.70     13423071.00      2067401.01     13423112.67
      2067632.69     13421853.93
#Sta/Elev= 30
  3277.5  340.69  3472.9  337.00  3653.0  336.02  3861.8  336.23  4134.5  336.37
  4323.4  335.28  4473.5  336.14  4527.7  335.56  4715.3  335.53  4773.5  335.21
  4802.2  333.94  4823.5  333.62  4824.0  332.82  4829.0  332.82  4829.5  333.62
  4879.5  334.98  4932.6  334.62  5036.1  335.26  5076.7  334.75  5137.7  335.30
  5178.4  334.79  5208.0  335.55  5341.1  336.58  5442.8  336.63  5488.4  337.18
  5599.6  339.17  5646.1  341.25  5657.7  341.21  5705.7  343.99  5779.4  346.95
#Mann=5,-1,0
  3277.5     0.1       0  3861.8    0.05       0  4134.5     0.1       0
  4823.5    0.07       0  4829.5     0.1       0
Bank Sta=4823.5,4829.5
Exp/Cntr=0.3,0.1

Type RM Length L Ch R = 1,3774,283,283,283
BEGIN DESCRIPTION:
Mapping XS cf24b86c
END DESCRIPTION:
XS GIS Cut Line= 2
      2067768.11     13423180.28      2067785.45     13421928.40
#Sta/Elev= 30
  4434.2  336.90  4509.5  336.63  4539.5  336.80  4559.5  336.44  4609.5  336.37
  4639.4  336.06  4739.5  335.95  4849.5  335.03  4899.5  334.84  4939.5  333.32
  5006.5  332.01  5007.0  331.21  5012.0  331.21  5012.5  332.01  5039.5  332.61
  5079.5  332.95  5099.5  332.22  5179.6  332.70  5199.6  333.43  5293.7  334.24
  5339.6  334.89  5379.6  335.07  5399.6  334.84  5479.6  335.42  5509.6  336.36
  5539.6  336.85  5599.6  339.06  5639.6  340.96  5669.6  341.77  5686.2  342.61
#Mann=4,-1,0
  4434.2    0.05       0  4639.4     0.1       0  5006.5    0.07       0
  5012.5     0.1       0
Bank Sta=5006.5,5012.5
Exp/Cntr=0.3,0.1

Type RM Length L Ch R = 1,3491,436,436,436
BEGIN DESCRIPTION:
Mapping XS b42a432e
END DESCRIPTION:
XS GIS Cut Line= 2
      2068094.50     13422982.39      2067917.41     13421840.03
#Sta/Elev= 30
  4546.8  336.54  4613.5  335.97  4726.3  335.58  4840.0  334.04  4888.2  334.07
  4966.0  330.93  4971.0  331.15  4989.4  329.65  5006.7  328.98  5007.2  328.18
  5012.2  328.18  5012.7  328.98  5019.8  329.11  5029.0  330.09  5034.0  329.83
  5040.0  330.81  5050.1  331.50  5080.5  332.21  5097.0  331.83  5131.1  332.00
  5165.1  332.68  5222.2  332.11  5291.1  334.12  5333.5  334.27  5353.7  335.12
  5384.1  335.62  5427.2  335.80  5535.9  337.53  5616.2  340.34  5702.8  342.63
#Mann=4,-1,0
  4546.8    0.05       0  4613.5     0.1       0  5006.7    0.07       0
  5012.7     0.1       0
Bank Sta=5006.7,5012.7
Exp/Cntr=0.3,0.1

Type RM Length L Ch R = 1,3055,0,0,0
BEGIN DESCRIPTION:
Mapping XS 0b8ae219
END DESCRIPTION:
XS GIS Cut Line= 3
      2068427.82     13422958.06      2068361.86     13422749.77
      2068247.28     13421840.05
#Sta/Elev= 30
  4373.1  335.48  4544.1  335.81  4656.9  334.70  4727.4  334.99  4764.6  333.34
  4858.5  331.00  4925.3  331.19  4930.3  330.46  4959.2  328.89  4976.4  326.16
  4976.9  325.36  4981.9  325.36  4982.4  326.16  4999.6  326.97  5005.6  328.12
  5010.6  327.77  5039.9  330.06  5060.0  330.89  5085.9  330.69  5091.0  331.19
  5120.5  330.04  5150.7  330.25  5160.8  330.61  5166.2  331.54  5181.0  332.45
  5291.8  336.33  5352.3  337.37  5402.2  339.24  5482.5  339.61  5508.5  339.05
#Mann=3,-1,0
  4373.1     0.1       0  4976.4    0.07       0  4982.4     0.1       0
Bank Sta=4976.4,4982.4
Exp/Cntr=0.3,0.1

Chan Stop Cuts=-1