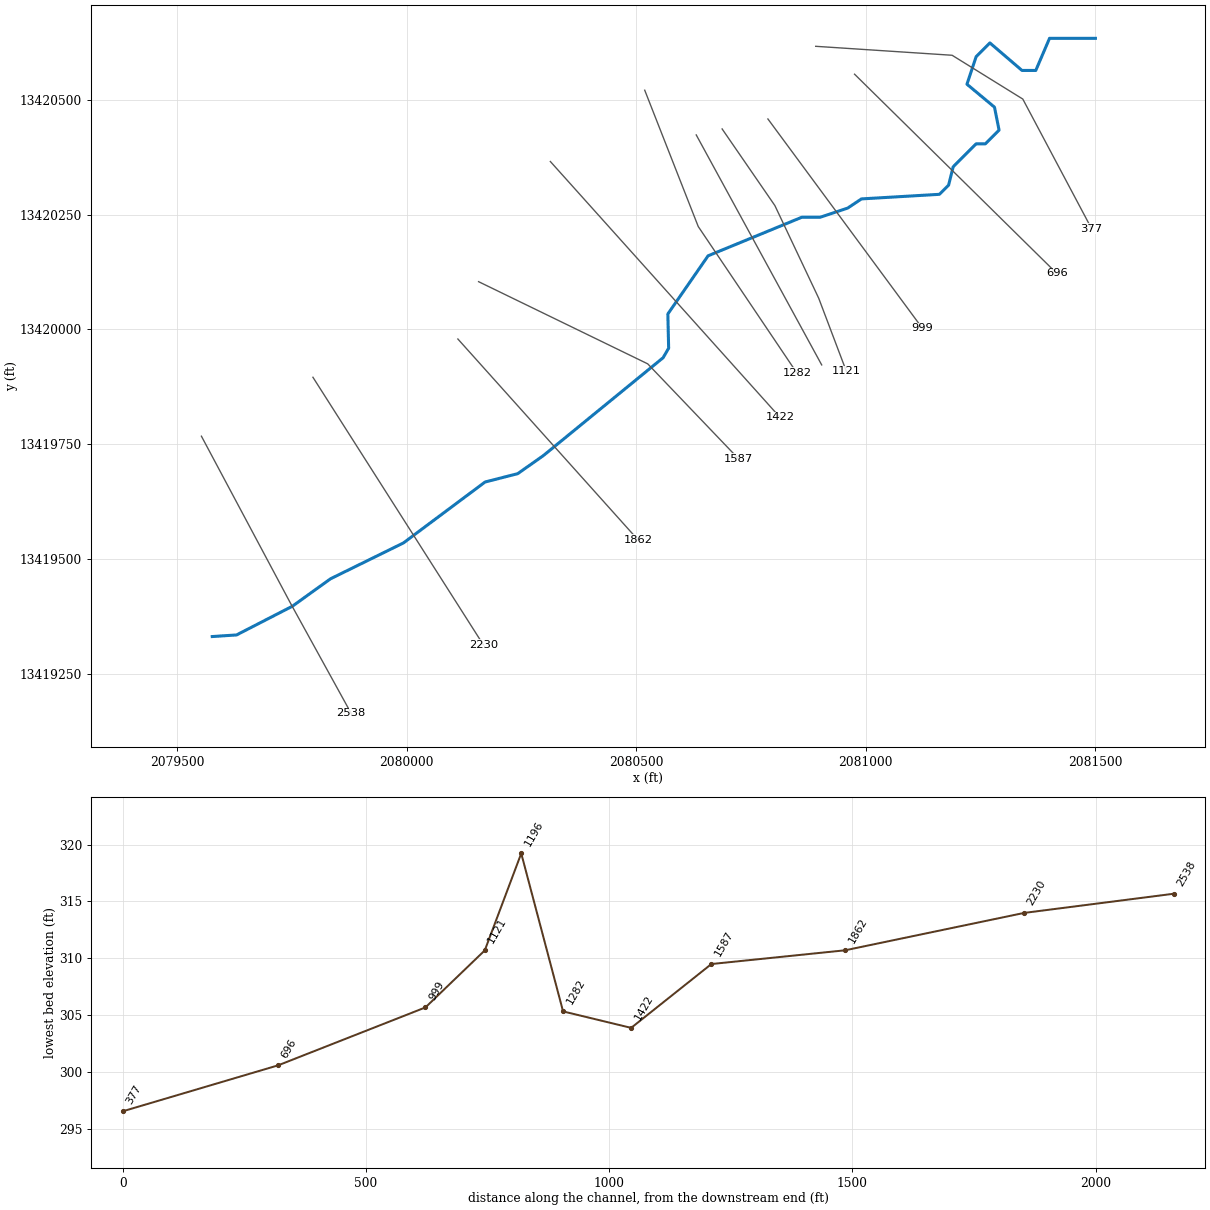
--- UNT 082 in RCW.prj (project) ---

Proj Title=UNT 082 in RCW Base Level Engineering
Current Plan=p01
Default Exp/Contr=0.3,0.1
English Units
Geom File=g01
Flow File=f01
Plan File=p01
BEGIN DESCRIPTION:
UNT 082 in RCW
END DESCRIPTION:

--- UNT 082 in RCW.p01 (plan) ---

Plan Title=Multiple Run
Short Identifier=Multiple
Geom File=g01
Flow File=f01
Subcritical Flow
K Sum by GR= 0
Std Step Tol= 0.01
Critical Tol= 0.01
Num of Std Step Trials= 20
Max Error Tol= 0.3
Flow Tol Ratio= 0.001
Split Flow NTrial= 30
Split Flow Tol= 0.02
Split Flow Ratio= 0.02
Log Output Level= 0
Friction Slope Method= 1
Unsteady Friction Slope Method= 2
Unsteady Bridges Friction Slope Method= 1
Parabolic Critical Depth
Global Vel Dist=  1 , 1 , 1
Global Log Level= 0
CheckData=True
Encroach Param= -1, 0, 0, 0
BEGIN DESCRIPTION:
Multiple Run
END DESCRIPTION:

--- UNT 082 in RCW.f01 (steady flow) ---

Flow Title=Multiple
Number of Profiles=7
Profile Names=10-year,25-year,50-year,1pct_min,100-year,1pct_plu,500-year
River Rch & RM= UNT 082 in RCW,Reach-1,2538
     110     146     175     105     209     418     304
Boundary for River Rch & Prof#=UNT 082 in RCW,Reach-1,1
Up Type=0
Dn Type=3
Dn Slope=0.005
Boundary for River Rch & Prof#=UNT 082 in RCW,Reach-1,2
Up Type=0
Dn Type=3
Dn Slope=0.005
Boundary for River Rch & Prof#=UNT 082 in RCW,Reach-1,3
Up Type=0
Dn Type=3
Dn Slope=0.005
Boundary for River Rch & Prof#=UNT 082 in RCW,Reach-1,4
Up Type=0
Dn Type=3
Dn Slope=0.005
Boundary for River Rch & Prof#=UNT 082 in RCW,Reach-1,5
Up Type=0
Dn Type=3
Dn Slope=0.005
Boundary for River Rch & Prof#=UNT 082 in RCW,Reach-1,6
Up Type=0
Dn Type=3
Dn Slope=0.005
Boundary for River Rch & Prof#=UNT 082 in RCW,Reach-1,7
Up Type=0
Dn Type=3
Dn Slope=0.005

--- UNT 082 in RCW.g01 (geometry) ---

Geom Title=Existing Conditions

River Reach=UNT 082 in RCW,Reach-1
Reach XY= 30
      2079575.80     13419330.64      2079628.75     13419334.11
      2079750.28     13419396.61      2079833.61     13419456.51
      2079992.47     13419534.63      2080170.42     13419667.44
      2080241.60     13419685.67      2080297.16     13419724.73
      2080558.44     13419938.28      2080570.59     13419959.11
      2080568.86     13420033.76      2080656.53     13420160.50
      2080860.80     13420244.54      2080900.80     13420244.54
      2080960.80     13420264.54      2080990.80     13420284.54
      2081160.80     13420294.54      2081180.80     13420314.54
      2081190.80     13420354.54      2081240.80     13420404.54
      2081260.80     13420404.54      2081290.80     13420434.54
      2081280.80     13420484.54      2081220.80     13420534.54
      2081240.80     13420594.54      2081270.80     13420624.54
      2081340.80     13420564.54      2081370.80     13420564.54
      2081400.80     13420634.54      2081500.80     13420634.54

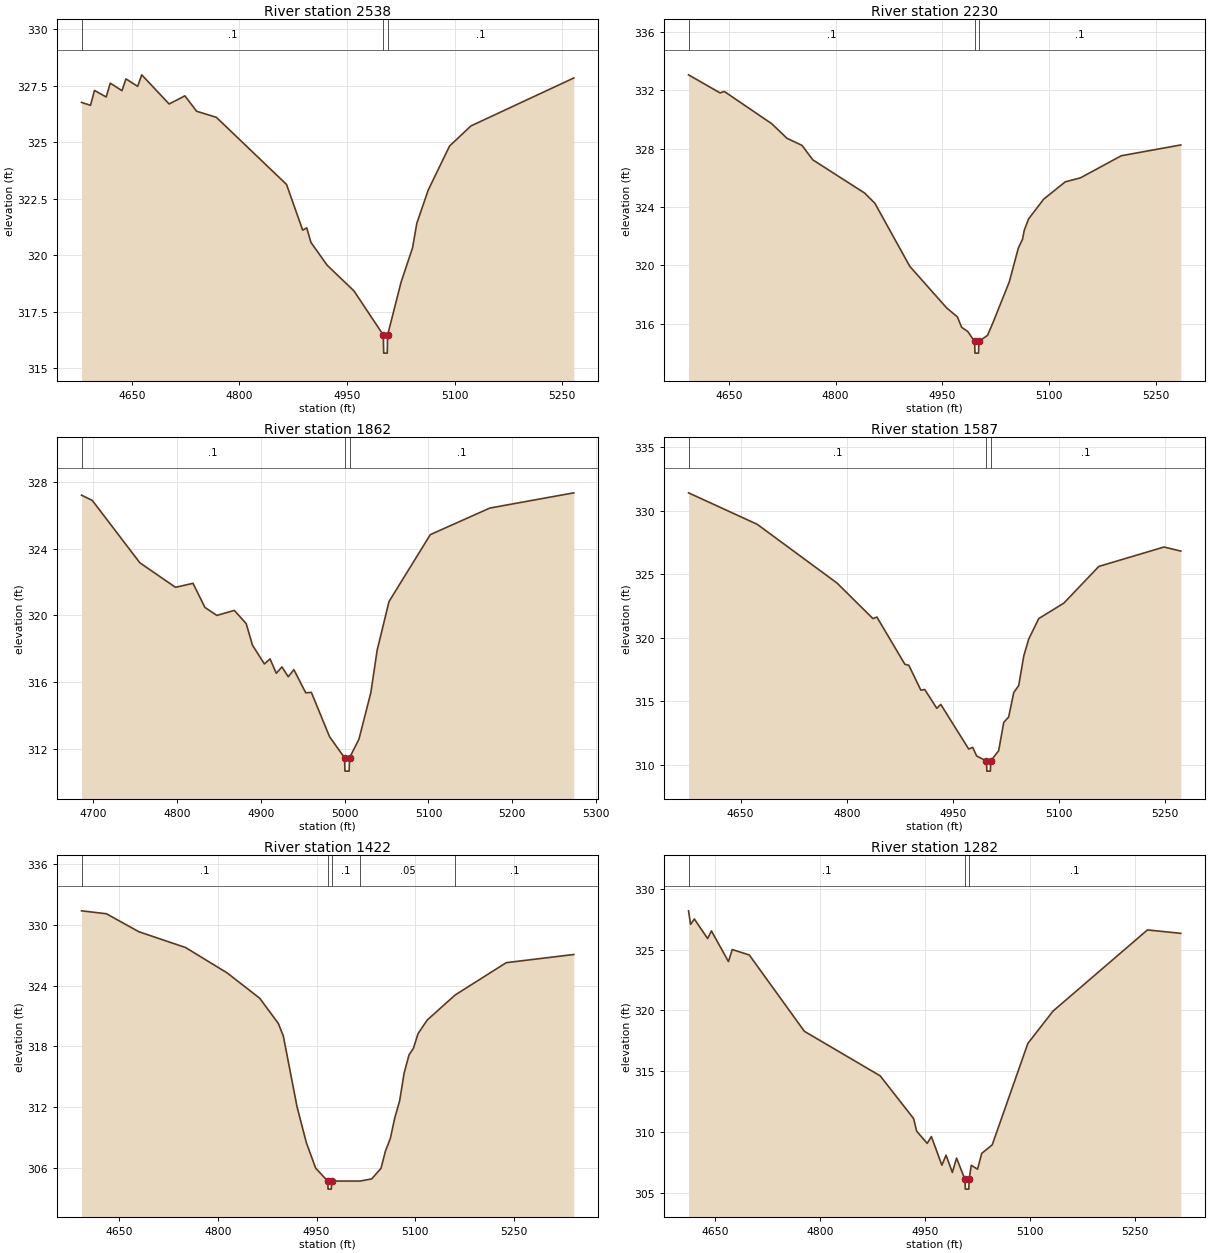
Type RM Length L Ch R = 1,2538,308,308,308
BEGIN DESCRIPTION:
UNT 082 in RCW 4.0
END DESCRIPTION:
XS GIS Cut Line= 3
      2079552.19     13419767.33      2079746.62     13419402.76
      2079878.57     13419163.17
#Sta/Elev= 30
  4579.7  326.76  4592.2  326.63  4597.8  327.29  4614.1  327.00  4619.8  327.61
  4636.1  327.28  4641.7  327.80  4658.0  327.47  4663.7  327.98  4701.9  326.69
  4723.9  327.05  4740.2  326.37  4767.8  326.10  4865.7  323.13  4888.2  321.11
  4893.9  321.21  4899.7  320.57  4922.3  319.56  4959.8  318.42  5000.7  316.47
  5001.2  315.67  5006.2  315.67  5006.7  316.47  5025.4  318.80  5041.5  320.33
  5047.4  321.41  5063.3  322.88  5093.1  324.83  5122.9  325.72  5266.4  327.84
#Mann=3,-1,0
  4579.7     0.1       0  5000.7    0.07       0  5006.7     0.1       0
Bank Sta=5000.7,5006.7
Exp/Cntr=0.3,0.1

Type RM Length L Ch R = 1,2230,368,368,368
BEGIN DESCRIPTION:
Mapping XS b7c4224b
END DESCRIPTION:
XS GIS Cut Line= 2
      2079795.25     13419895.79      2080166.78     13419312.46
#Sta/Elev= 30
  4593.5  333.07  4637.8  331.83  4643.7  331.93  4710.6  329.71  4731.7  328.72
  4752.9  328.23  4768.1  327.24  4840.9  324.96  4855.3  324.26  4904.4  319.93
  4956.0  317.09  4971.3  316.46  4977.2  315.75  4985.7  315.47  4995.4  314.78
  4995.9  313.98  5000.9  313.98  5001.4  314.78  5013.6  315.20  5021.3  316.08
  5044.1  318.86  5056.8  321.18  5062.7  321.79  5065.2  322.41  5071.2  323.18
  5092.4  324.54  5122.8  325.73  5144.0  326.00  5201.5  327.52  5285.1  328.26
#Mann=3,-1,0
  4593.5     0.1       0  4995.4    0.07       0  5001.4     0.1       0
Bank Sta=4995.4,5001.4
Exp/Cntr=0.3,0.1

Type RM Length L Ch R = 1,1862,275,275,275
BEGIN DESCRIPTION:
Mapping XS 06eacca7
END DESCRIPTION:
XS GIS Cut Line= 2
      2080111.19     13419979.17      2080503.57     13419541.64
#Sta/Elev= 30
  4685.8  327.19  4698.6  326.88  4755.4  323.15  4798.0  321.68  4818.9  321.92
  4833.1  320.48  4847.3  320.00  4868.2  320.30  4882.4  319.51  4889.9  318.22
  4904.1  317.10  4910.9  317.40  4918.3  316.54  4925.1  316.92  4932.6  316.33
  4939.3  316.76  4953.5  315.37  4960.2  315.40  4981.9  312.75  4999.8  311.49
  5000.3  310.69  5005.3  310.69  5005.8  311.49  5017.0  312.60  5031.2  315.38
  5038.7  317.91  5052.9  320.83  5102.2  324.83  5173.3  326.42  5273.5  327.33
#Mann=3,-1,0
  4685.8     0.1       0  4999.8    0.07       0  5005.8     0.1       0
Bank Sta=4999.8,5005.8
Exp/Cntr=0.3,0.1

Type RM Length L Ch R = 1,1587,165,165,165
BEGIN DESCRIPTION:
UNT 082 in RCW 3.0
END DESCRIPTION:
XS GIS Cut Line= 3
      2080156.32     13420104.16      2080525.00     13419925.00
      2080722.35     13419718.70
#Sta/Elev= 30
  4576.4  331.41  4673.4  328.93  4786.2  324.30  4836.9  321.50  4842.5  321.62
  4882.0  317.90  4887.6  317.82  4904.6  315.86  4910.1  315.91  4927.1  314.43
  4932.7  314.74  4972.2  311.22  4977.8  311.35  4983.5  310.67  4997.3  310.28
  4997.8  309.48  5002.8  309.48  5003.3  310.28  5014.5  311.09  5021.7  313.32
  5028.6  313.74  5035.8  315.67  5042.8  316.22  5050.0  318.56  5056.9  319.88
  5071.1  321.50  5106.6  322.72  5156.0  325.61  5248.1  327.14  5271.8  326.82
#Mann=3,-1,0
  4576.4     0.1       0  4997.3    0.07       0  5003.3     0.1       0
Bank Sta=4997.3,5003.3
Exp/Cntr=0.3,0.1

Type RM Length L Ch R = 1,1422,140,140,140
BEGIN DESCRIPTION:
Mapping XS 6e3f35a0
END DESCRIPTION:
XS GIS Cut Line= 2
      2080312.73     13420366.09      2080813.15     13419808.53
#Sta/Elev= 30
  4592.3  331.40  4630.2  331.11  4679.6  329.33  4750.6  327.77  4814.1  325.25
  4863.5  322.75  4891.9  320.25  4899.4  319.02  4920.3  312.01  4934.5  308.45
  4948.7  305.93  4967.0  304.66  4967.5  303.86  4972.5  303.86  4973.0  304.66
  5016.3  304.66  5033.9  304.87  5048.1  305.92  5054.8  307.62  5062.3  308.88
  5069.0  310.90  5076.5  312.61  5083.2  315.32  5090.7  317.14  5097.4  317.79
  5104.4  319.24  5118.4  320.59  5160.9  323.07  5238.7  326.27  5341.5  327.08
#Mann=5,-1,0
  4592.3     0.1       0  4967.0    0.07       0  4973.0     0.1       0
  5016.3    0.05       0  5160.9     0.1       0
Bank Sta=4967,4973
Exp/Cntr=0.3,0.1

Type RM Length L Ch R = 1,1282,86,86,86
BEGIN DESCRIPTION:
Mapping XS f0bc162e
END DESCRIPTION:
XS GIS Cut Line= 3
      2080518.45     13420521.47      2080635.08     13420224.37
      2080849.93     13419905.34
#Sta/Elev= 30
  4612.2  328.18  4615.1  327.07  4620.5  327.51  4639.5  325.90  4644.9  326.53
  4669.3  324.01  4674.7  325.00  4699.1  324.55  4777.8  318.28  4886.2  314.62
  4934.0  311.11  4938.4  310.07  4953.4  309.07  4959.4  309.63  4974.4  307.28
  4980.4  308.10  4989.4  306.68  4995.4  307.86  5007.4  306.11  5007.9  305.31
  5012.9  305.31  5013.4  306.11  5016.4  307.27  5025.4  306.95  5031.4  308.25
  5046.4  308.95  5097.3  317.28  5133.3  319.94  5268.3  326.61  5316.0  326.33
#Mann=3,-1,0
  4612.2     0.1       0  5007.4    0.07       0  5013.4     0.1       0
Bank Sta=5007.4,5013.4
Exp/Cntr=0.3,0.1

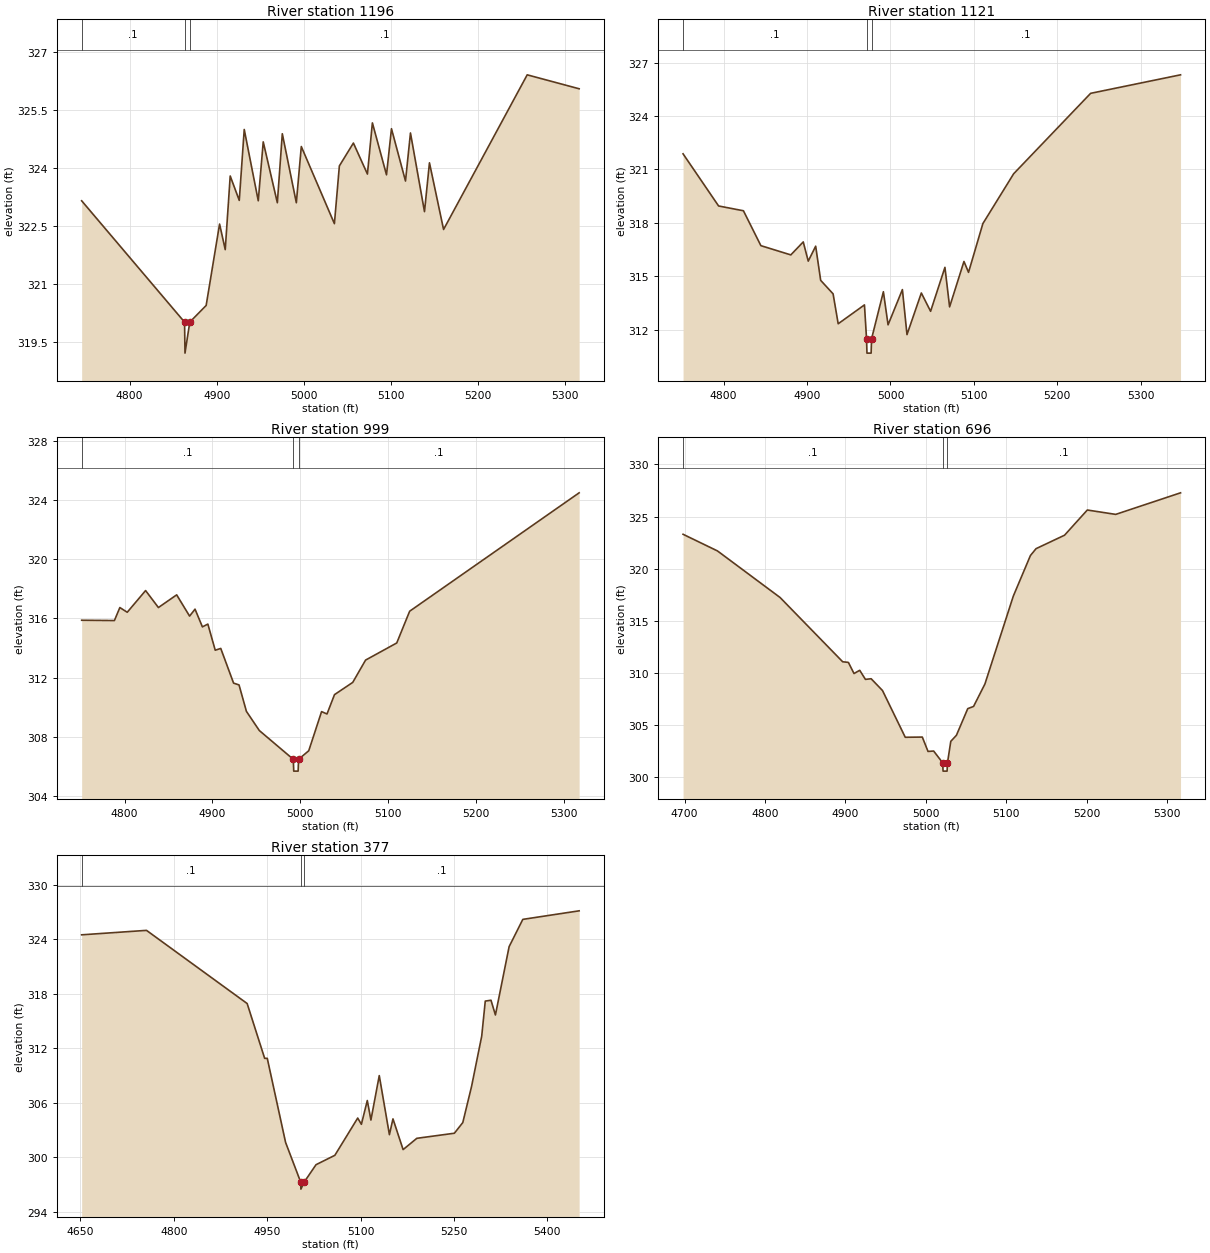
Type RM Length L Ch R = 1,1196,75,75,75
BEGIN DESCRIPTION:
Mapping XS cb73fe95
END DESCRIPTION:
XS GIS Cut Line= 2
      2080630.75     13420423.99      2080904.18     13419922.72
#Sta/Elev= 30
  4745.0  323.15  4863.1  320.02  4863.6  319.22  4869.1  320.02  4887.9  320.45
  4903.3  322.55  4909.8  321.89  4915.5  323.79  4925.9  323.16  4931.6  324.99
  4947.7  323.15  4953.4  324.67  4969.6  323.10  4975.3  324.88  4991.4  323.10
  4997.1  324.55  5035.1  322.56  5040.8  324.05  5056.9  324.64  5073.0  323.84
  5078.7  325.16  5094.9  323.82  5100.6  325.01  5116.7  323.66  5122.4  324.90
  5138.5  322.87  5144.2  324.13  5160.4  322.41  5256.4  326.40  5316.0  326.04
#Mann=3,-1,0
  4745.0     0.1       0  4863.1    0.07       0  4869.1     0.1       0
Bank Sta=4863.1,4869.1
Exp/Cntr=0.3,0.1

Type RM Length L Ch R = 1,1121,122,122,122
BEGIN DESCRIPTION:
Mapping XS 46a960a6
END DESCRIPTION:
XS GIS Cut Line= 4
      2080687.17     13420437.03      2080802.18     13420269.95
      2080897.66     13420068.12      2080957.96     13419908.76
#Sta/Elev= 30
  4751.3  321.88  4793.9  318.95  4823.7  318.68  4844.6  316.72  4880.5  316.20
  4895.4  316.93  4901.4  315.85  4910.3  316.69  4916.3  314.77  4931.2  314.01
  4937.3  312.33  4968.8  313.39  4971.3  311.48  4971.8  310.68  4976.8  310.68
  4977.3  311.48  4991.5  314.13  4997.1  312.27  5014.3  314.25  5019.8  311.72
  5037.0  314.06  5048.1  313.03  5065.3  315.50  5070.9  313.28  5088.1  315.83
  5093.6  315.22  5110.8  317.96  5147.7  320.76  5240.0  325.28  5347.8  326.32
#Mann=3,-1,0
  4751.3     0.1       0  4971.3    0.07       0  4977.3     0.1       0
Bank Sta=4971.3,4977.3
Exp/Cntr=0.3,0.1

Type RM Length L Ch R = 1,999,303,303,303
BEGIN DESCRIPTION:
Mapping XS b59b0c55
END DESCRIPTION:
XS GIS Cut Line= 2
      2080786.97     13420458.78      2081123.39     13420002.98
#Sta/Elev= 30
  4751.1  315.88  4788.4  315.86  4794.6  316.74  4803.0  316.42  4823.9  317.89
  4838.5  316.74  4859.3  317.60  4874.0  316.16  4880.2  316.63  4888.6  315.43
  4894.8  315.62  4903.2  313.85  4909.5  313.97  4924.1  311.62  4930.3  311.50
  4938.7  309.71  4953.4  308.41  4992.1  306.46  4992.6  305.66  4997.6  305.66
  4998.1  306.46  5009.7  307.04  5024.3  309.69  5030.5  309.53  5039.0  310.84
  5059.8  311.67  5074.4  313.18  5109.9  314.34  5124.6  316.49  5317.6  324.51
#Mann=3,-1,0
  4751.1     0.1       0  4992.1    0.07       0  4998.1     0.1       0
Bank Sta=4992.1,4998.1
Exp/Cntr=0.3,0.1

Type RM Length L Ch R = 1,696,319,319,319
BEGIN DESCRIPTION:
Mapping XS f8468c0a
END DESCRIPTION:
XS GIS Cut Line= 2
      2080975.81     13420556.38      2081416.33     13420122.38
#Sta/Elev= 30
  4698.2  323.30  4741.0  321.70  4818.8  317.23  4896.6  311.06  4903.7  311.00
  4910.7  309.93  4917.8  310.24  4924.9  309.37  4932.0  309.43  4946.1  308.30
  4974.4  303.81  4995.6  303.83  5002.7  302.45  5009.7  302.49  5020.9  301.36
  5021.4  300.56  5026.4  300.56  5026.9  301.36  5031.0  303.42  5038.0  304.00
  5052.1  306.56  5059.3  306.77  5073.4  308.92  5108.7  317.36  5130.0  321.26
  5137.0  321.92  5172.4  323.21  5200.7  325.63  5236.0  325.21  5316.6  327.28
#Mann=3,-1,0
  4698.2     0.1       0  5020.9    0.07       0  5026.9     0.1       0
Bank Sta=5020.9,5026.9
Exp/Cntr=0.3,0.1

Type RM Length L Ch R = 1,377,0,0,0
BEGIN DESCRIPTION:
UNT 082 in RCW 1.0
END DESCRIPTION:
XS GIS Cut Line= 4
      2080891.11     13420617.17      2081188.46     13420597.64
      2081342.54     13420502.15      2081492.30     13420220.00
#Sta/Elev= 30
  4652.2  324.50  4756.3  324.99  4917.9  316.94  4946.0  310.91  4950.2  310.91
  4979.6  301.66  5003.7  297.32  5004.2  296.52  5009.7  297.32  5028.5  299.21
  5058.7  300.24  5095.4  304.34  5101.3  303.65  5110.8  306.27  5116.6  304.12
  5130.0  309.01  5146.3  302.51  5152.0  304.25  5168.3  300.87  5190.3  302.11
  5250.6  302.67  5264.1  303.84  5278.2  307.82  5294.5  313.36  5300.2  317.21
  5309.4  317.30  5316.5  315.68  5338.5  323.20  5360.5  326.20  5450.9  327.14
#Mann=3,-1,0
  4652.2     0.1       0  5003.7    0.07       0  5009.7     0.1       0
Bank Sta=5003.7,5009.7
Exp/Cntr=0.3,0.1

Chan Stop Cuts=-1