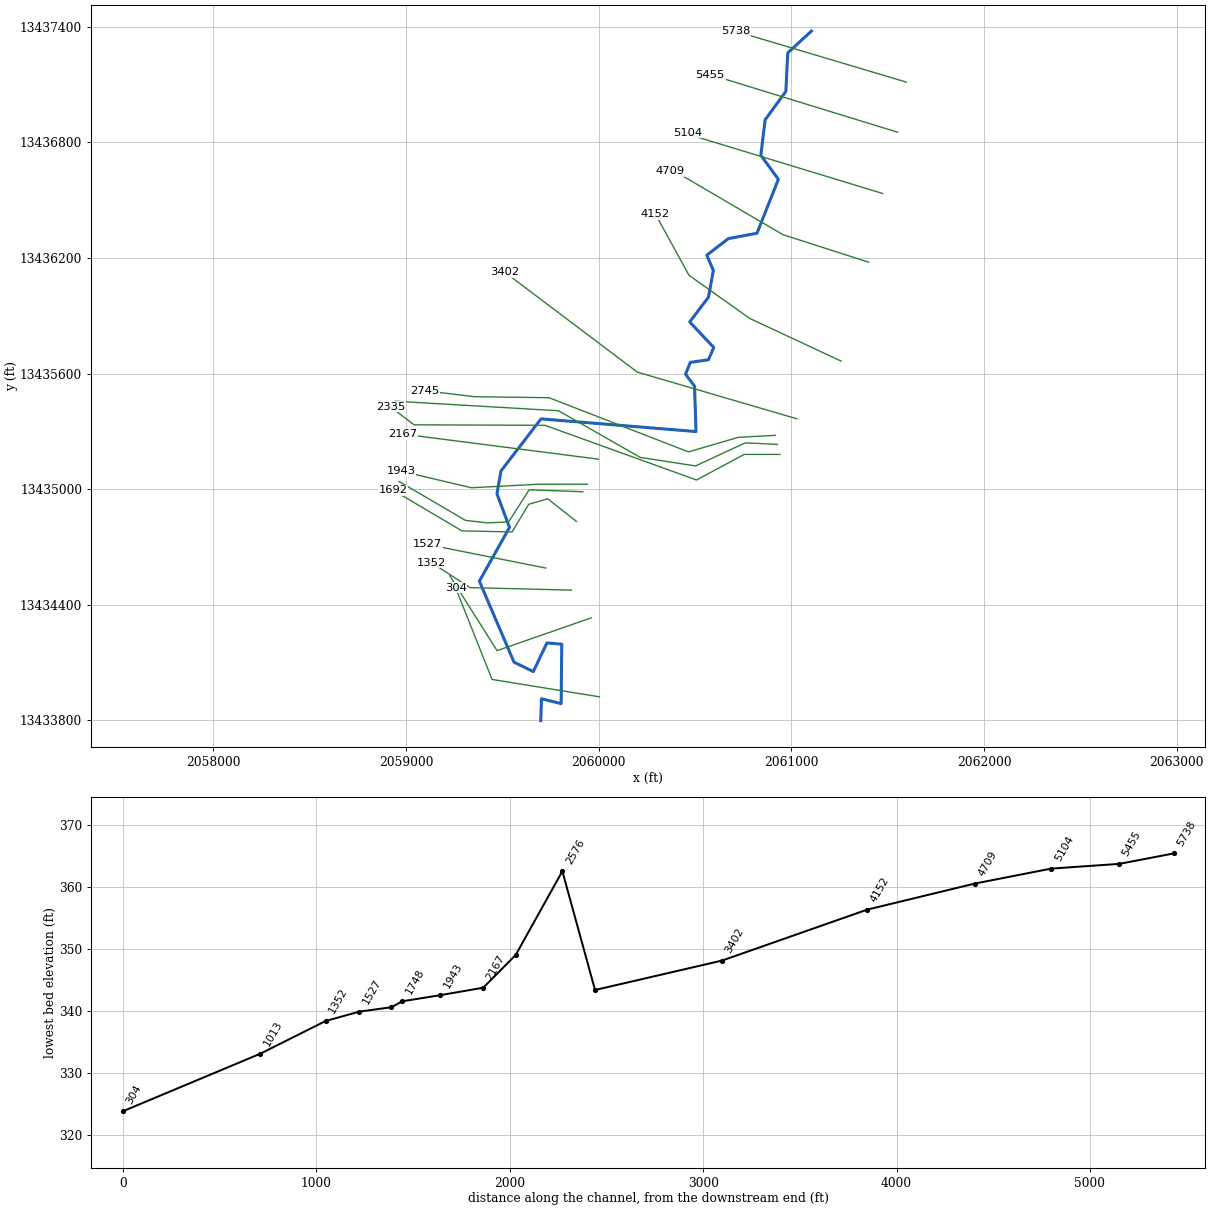
--- UNT 083 in RCW.prj (project) ---

Proj Title=UNT 083 in RCW Base Level Engineering
Current Plan=p01
Default Exp/Contr=0.3,0.1
English Units
Geom File=g01
Flow File=f01
Plan File=p01
BEGIN DESCRIPTION:
UNT 083 in RCW
END DESCRIPTION:

--- UNT 083 in RCW.p01 (plan) ---

Plan Title=Multiple Run
Short Identifier=Multiple
Geom File=g01
Flow File=f01
Subcritical Flow
K Sum by GR= 0
Std Step Tol= 0.01
Critical Tol= 0.01
Num of Std Step Trials= 20
Max Error Tol= 0.3
Flow Tol Ratio= 0.001
Split Flow NTrial= 30
Split Flow Tol= 0.02
Split Flow Ratio= 0.02
Log Output Level= 0
Friction Slope Method= 1
Unsteady Friction Slope Method= 2
Unsteady Bridges Friction Slope Method= 1
Parabolic Critical Depth
Global Vel Dist=  1 , 1 , 1
Global Log Level= 0
CheckData=True
Encroach Param= -1, 0, 0, 0
BEGIN DESCRIPTION:
Multiple Run
END DESCRIPTION:

--- UNT 083 in RCW.f01 (steady flow) ---

Flow Title=Multiple
Number of Profiles=7
Profile Names=10-year,25-year,50-year,1pct_min,100-year,1pct_plu,500-year
River Rch & RM= UNT 083 in RCW,Reach-1,5738
     197     271     332     203     406     810     613
River Rch & RM= UNT 083 in RCW,Reach-1,2745
     245     342     422     260     520    1037     798
Boundary for River Rch & Prof#=UNT 083 in RCW,Reach-1,1
Up Type=0
Dn Type=3
Dn Slope=0.005
Boundary for River Rch & Prof#=UNT 083 in RCW,Reach-1,2
Up Type=0
Dn Type=3
Dn Slope=0.005
Boundary for River Rch & Prof#=UNT 083 in RCW,Reach-1,3
Up Type=0
Dn Type=3
Dn Slope=0.005
Boundary for River Rch & Prof#=UNT 083 in RCW,Reach-1,4
Up Type=0
Dn Type=3
Dn Slope=0.005
Boundary for River Rch & Prof#=UNT 083 in RCW,Reach-1,5
Up Type=0
Dn Type=3
Dn Slope=0.005
Boundary for River Rch & Prof#=UNT 083 in RCW,Reach-1,6
Up Type=0
Dn Type=3
Dn Slope=0.005
Boundary for River Rch & Prof#=UNT 083 in RCW,Reach-1,7
Up Type=0
Dn Type=3
Dn Slope=0.005

--- UNT 083 in RCW.g01 (geometry) ---

Geom Title=Existing Conditions

River Reach=UNT 083 in RCW,Reach-1
Reach XY= 30
      2061103.73     13437377.47      2060980.80     13437264.54
      2060970.80     13437064.54      2060863.50     13436917.13
      2060840.93     13436733.10      2060931.90     13436608.10
      2060821.14     13436328.33      2060672.70     13436300.55
      2060560.72     13436214.61      2060594.58     13436134.75
      2060568.97     13435995.86      2060471.75     13435867.82
      2060596.75     13435735.44      2060568.97     13435671.64
      2060474.79     13435658.19      2060450.48     13435596.55
      2060496.92     13435534.49      2060504.59     13435299.06
      2059700.16     13435364.94      2059492.34     13435094.35
      2059471.50     13434975.86      2059536.61     13434801.38
      2059380.36     13434522.74      2059560.04     13434102.16
      2059660.30     13434053.34      2059730.83     13434201.99
      2059807.87     13434195.48      2059804.62     13433887.32
      2059702.62     13433912.28      2059698.81     13433798.78

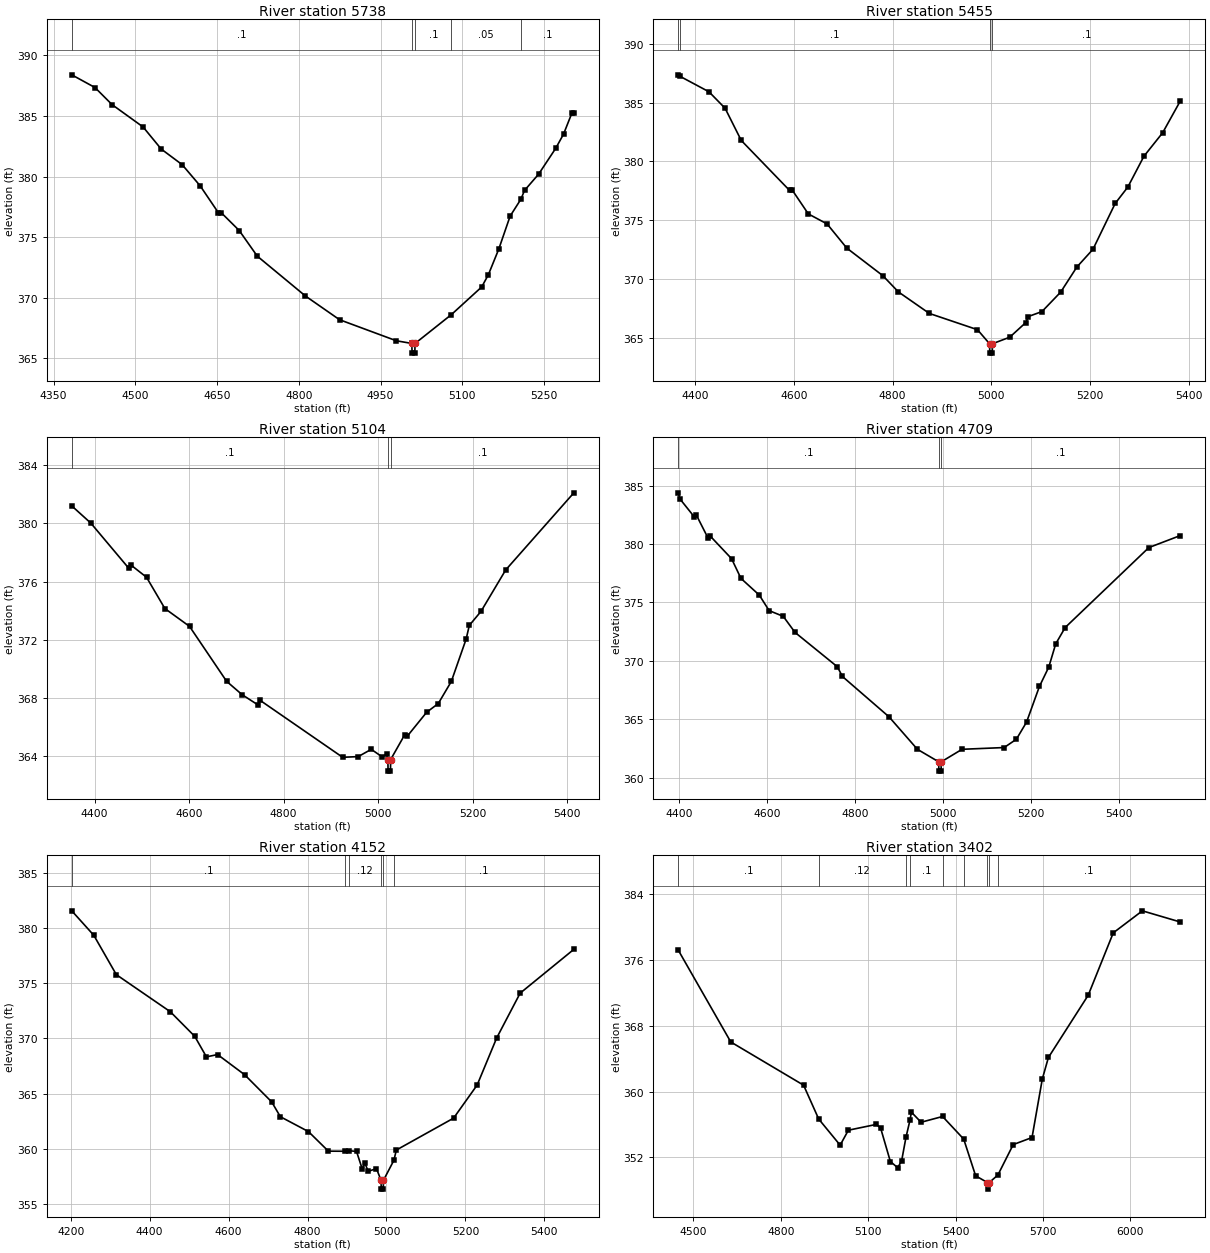
Type RM Length L Ch R = 1,5738,283,283,283
BEGIN DESCRIPTION:
UNT 083 in RCW 10.0
END DESCRIPTION:
XS GIS Cut Line= 2
      2061595.84     13437112.72      2060712.99     13437375.75
#Sta/Elev= 30
  4383.5  388.40  4426.1  387.35  4457.4  385.94  4514.4  384.09  4547.6  382.27
  4586.0  380.98  4619.1  379.23  4652.3  377.02  4657.5  377.02  4690.7  375.54
  4723.9  373.42  4812.2  370.13  4874.8  368.17  4979.1  366.43  5007.4  366.21
  5007.9  365.41  5012.9  365.41  5013.4  366.21  5080.2  368.60  5135.7  370.88
  5147.9  371.89  5167.0  374.01  5187.8  376.73  5207.5  378.12  5214.2  378.85
  5240.0  380.19  5271.3  382.32  5285.8  383.50  5301.0  385.23  5304.7  385.23
#Mann=5,-1,0
  4383.5     0.1       0  5007.4    0.07       0  5013.4     0.1       0
  5080.2    0.05       0  5207.5     0.1       0
Bank Sta=5007.4,5013.4
Exp/Cntr=0.3,0.1

Type RM Length L Ch R = 1,5455,351,351,351
BEGIN DESCRIPTION:
UNT 083 in RCW 9.0
END DESCRIPTION:
XS GIS Cut Line= 2
      2061551.53     13436852.31      2060578.78     13437151.42
#Sta/Elev= 30
  4365.5  387.35  4368.8  387.23  4427.8  385.91  4460.5  384.51  4493.2  381.78
  4591.3  377.53  4596.5  377.57  4629.2  375.54  4667.2  374.69  4707.1  372.64
  4780.4  370.29  4811.7  368.92  4874.5  367.09  4972.0  365.71  4996.5  364.52
  4997.0  363.72  5002.0  363.72  5002.5  364.52  5037.4  365.07  5070.1  366.32
  5075.3  366.83  5102.8  367.25  5140.7  368.90  5173.5  371.03  5206.2  372.54
  5251.2  376.43  5276.8  377.82  5309.5  380.44  5347.4  382.43  5383.2  385.13
#Mann=4,-1,0
  4365.5    0.05       0  4368.8     0.1       0  4996.5    0.07       0
  5002.5     0.1       0
Bank Sta=4996.5,5002.5
Exp/Cntr=0.3,0.1

Type RM Length L Ch R = 1,5104,395,395,395
BEGIN DESCRIPTION:
UNT 083 in RCW 8.0
END DESCRIPTION:
XS GIS Cut Line= 3
      2061473.45     13436534.59      2060515.10     13436826.26
      2060458.87     13436849.27
#Sta/Elev= 30
  4351.8  381.21  4392.0  380.03  4471.9  376.94  4477.1  377.14  4510.0  376.30
  4548.8  374.15  4601.0  372.92  4679.5  369.14  4712.3  368.22  4745.2  367.53
  4750.4  367.83  4925.1  363.91  4958.0  363.96  4985.6  364.46  5008.7  363.94
  5018.4  364.15  5020.7  363.76  5021.2  362.96  5026.2  362.96  5026.7  363.76
  5056.5  365.47  5061.7  365.36  5102.8  367.01  5127.4  367.61  5155.0  369.13
  5186.4  372.05  5193.1  372.99  5217.8  373.95  5270.0  376.80  5414.3  382.11
#Mann=3,-1,0
  4351.8     0.1       0  5020.7    0.07       0  5026.7     0.1       0
Bank Sta=5020.7,5026.7
Exp/Cntr=0.3,0.1

Type RM Length L Ch R = 1,4709,557,557,557
BEGIN DESCRIPTION:
UNT 083 in RCW 7.0
END DESCRIPTION:
XS GIS Cut Line= 4
      2061400.52     13436177.83      2060955.21     13436321.06
      2060408.33     13436641.37      2060368.29     13436648.88
#Sta/Elev= 30
  4398.3  384.39  4402.1  383.87  4434.2  382.36  4439.5  382.49  4466.3  380.50
  4471.5  380.67  4519.6  378.75  4541.0  377.06  4582.7  375.63  4605.1  374.30
  4637.2  373.81  4664.1  372.43  4760.3  369.49  4771.8  368.66  4877.9  365.20
  4942.4  362.42  4990.8  361.35  4991.3  360.55  4996.3  360.55  4996.8  361.35
  5044.0  362.42  5139.8  362.57  5167.6  363.28  5190.8  364.75  5220.0  367.80
  5241.4  369.47  5257.1  371.45  5278.6  372.85  5469.0  379.70  5540.6  380.73
#Mann=3,-1,0
  4398.3     0.1       0  4990.8    0.07       0  4996.8     0.1       0
Bank Sta=4990.8,4996.8
Exp/Cntr=0.3,0.1

Type RM Length L Ch R = 1,4152,750,750,750
BEGIN DESCRIPTION:
UNT 083 in RCW 6.0
END DESCRIPTION:
XS GIS Cut Line= 4
      2061257.31     13435664.80      2060783.33     13435886.16
      2060468.23     13436110.12      2060293.73     13436427.85
#Sta/Elev= 30
  4202.6  381.55  4258.5  379.33  4315.5  375.77  4452.3  372.41  4514.2  370.18
  4543.8  368.32  4572.1  368.53  4640.7  366.70  4709.2  364.24  4731.1  362.90
  4802.4  361.55  4852.8  359.78  4895.6  359.77  4905.9  359.82  4924.2  359.75
  4938.9  358.13  4945.1  358.72  4953.7  357.95  4974.6  358.20  4986.3  357.14
  4986.8  356.34  4991.9  356.34  4992.4  357.14  5018.9  358.96  5025.0  359.88
  5170.1  362.77  5229.8  365.77  5279.1  370.02  5338.7  374.09  5474.8  378.06
#Mann=6,-1,0
  4202.6     0.1       0  4895.6    0.05       0  4905.9    0.12       0
  4986.3    0.07       0  4992.4    0.12       0  5018.9     0.1       0
Bank Sta=4986.3,4992.4
Exp/Cntr=0.3,0.1

Type RM Length L Ch R = 1,3402,657,657,657
BEGIN DESCRIPTION:
UNT 083 in RCW 5.0
END DESCRIPTION:
XS GIS Cut Line= 3
      2061028.14     13435365.32      2060200.00     13435607.51
      2059512.48     13436125.76
#Sta/Elev= 30
  4447.8  377.22  4628.2  366.04  4878.2  360.78  4930.1  356.66  5003.7  353.48
  5031.9  355.30  5128.3  356.01  5142.6  355.57  5176.1  351.49  5201.2  350.74
  5214.7  351.55  5229.7  354.44  5244.0  356.60  5248.2  357.50  5281.6  356.27
  5355.4  356.97  5427.9  354.22  5468.9  349.75  5509.5  348.93  5510.0  348.13
  5515.6  348.93  5545.3  349.85  5597.9  353.55  5662.5  354.41  5697.8  361.53
  5718.7  364.15  5855.4  371.73  5941.4  379.32  6041.3  382.00  6171.6  380.64
#Mann=9,-1,0
  4447.8     0.1       0  4930.1    0.12       0  5229.7    0.07       0
  5244.0     0.1       0  5355.4    0.07       0  5427.9    0.05       0
  5509.5    0.07       0  5515.6    0.05       0  5545.3     0.1       0
Bank Sta=5509.5,5515.6
Exp/Cntr=0.3,0.1

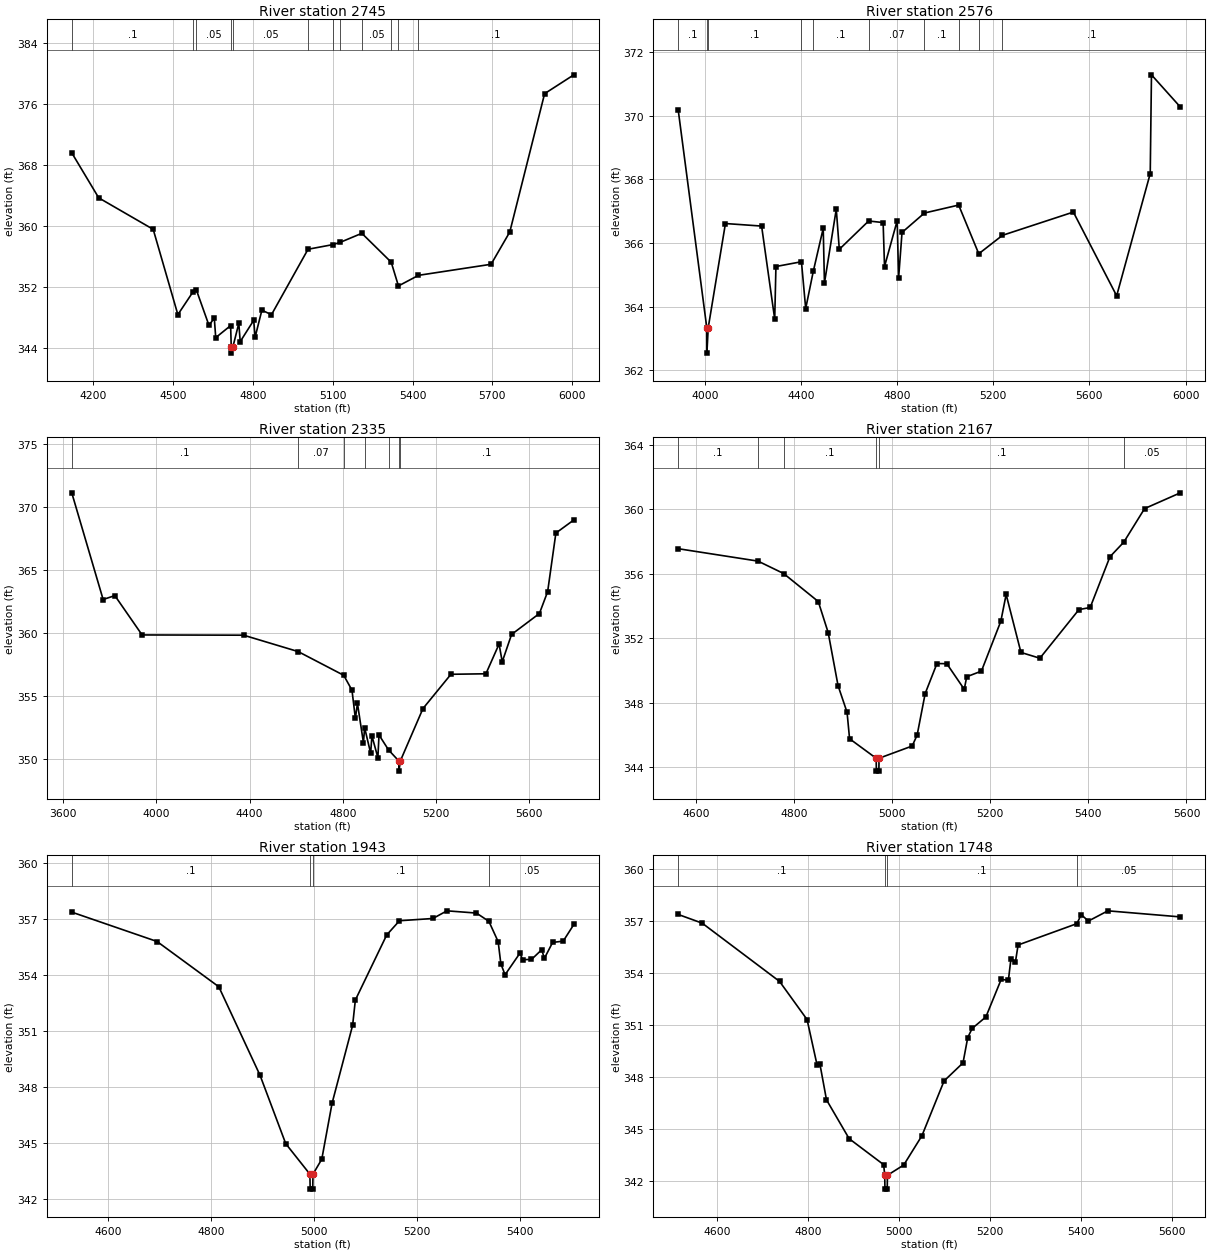
Type RM Length L Ch R = 1,2745,169,169,169
BEGIN DESCRIPTION:
UNT 083 in RCW 4.0
END DESCRIPTION:
XS GIS Cut Line= 6
      2060916.16     13435279.39      2060723.44     13435268.97
      2060465.62     13435193.45      2059741.67     13435474.70
      2059356.25     13435479.91      2059095.88     13435511.15
#Sta/Elev= 30
  4119.5  369.64  4220.8  363.74  4425.5  359.61  4518.2  348.43  4574.1  351.36
  4588.2  351.62  4635.1  347.02  4655.1  347.98  4660.5  345.41  4716.5  346.99
  4718.8  344.18  4719.3  343.38  4724.9  344.18  4747.2  347.29  4752.5  344.89
  4803.2  347.68  4808.5  345.47  4833.9  349.01  4870.0  348.42  5007.4  357.00
  5101.1  357.61  5128.6  357.91  5209.6  359.09  5320.0  355.30  5347.1  352.19
  5422.5  353.58  5695.3  355.03  5765.5  359.26  5896.4  377.40  6006.3  379.87
#Mann=12,-1,0
  4119.5     0.1       0  4574.1    0.07       0  4588.2    0.05       0
  4718.8   0.035       0  4724.9    0.05       0  5007.4    0.07       0
  5101.1     0.1       0  5128.6    0.07       0  5209.6    0.05       0
  5320.0    0.07       0  5347.1    0.05       0  5422.5     0.1       0
Bank Sta=4718.8,4724.9
Exp/Cntr=0.3,0.1

Type RM Length L Ch R = 1,2576,241,241,241
BEGIN DESCRIPTION:
UNT 083 in RCW 3.0
END DESCRIPTION:
XS GIS Cut Line= 6
      2060926.60     13435232.51      2060759.90     13435240.33
      2060502.08     13435120.53      2060215.62     13435164.81
      2059791.15     13435406.99      2058944.79     13435456.47
#Sta/Elev= 30
  3889.6  370.17  4008.3  363.34  4008.8  362.54  4014.4  363.34  4085.9  366.61
  4236.4  366.53  4290.9  363.61  4296.0  365.26  4402.1  365.41  4419.8  363.94
  4451.4  365.11  4492.7  366.46  4497.8  364.74  4547.0  367.06  4559.6  365.80
  4681.7  366.69  4741.9  366.64  4747.7  365.26  4800.4  366.70  4806.2  364.89
  4820.5  366.33  4913.7  366.94  5056.1  367.19  5139.7  365.66  5238.4  366.24
  5533.2  366.97  5713.3  364.34  5853.0  368.18  5858.1  371.28  5978.1  370.27
#Mann=10,-1,0
  3889.6     0.1       0  4008.3    0.07       0  4014.4     0.1       0
  4402.1    0.07       0  4451.4     0.1       0  4681.7    0.07       0
  4913.7     0.1       0  5056.1    0.05       0  5139.7    0.07       0
  5238.4     0.1       0
Bank Sta=4008.3,4014.4
Exp/Cntr=0.3,0.1

Type RM Length L Ch R = 1,2335,168,168,168
BEGIN DESCRIPTION:
UNT 083 in RCW 2.0
END DESCRIPTION:
XS GIS Cut Line= 6
      2060939.56     13435180.43      2060754.69     13435180.43
      2060507.29     13435047.62      2059720.83     13435331.47
      2059041.15     13435334.08      2058919.35     13435427.36
#Sta/Elev= 30
  3636.8  371.11  3771.4  362.65  3821.7  362.96  3938.6  359.84  4374.4  359.82
  4608.6  358.52  4804.0  356.64  4839.5  355.46  4854.1  353.22  4863.0  354.41
  4888.7  351.29  4893.8  352.49  4919.7  350.45  4925.0  351.84  4950.7  350.11
  4955.5  351.91  4996.5  350.72  5040.8  349.84  5041.3  349.04  5046.9  349.84
  5144.1  354.00  5264.3  356.72  5414.4  356.76  5470.9  359.12  5484.4  357.71
  5524.5  359.88  5644.0  361.54  5679.3  363.27  5714.7  367.92  5791.8  368.96
#Mann=7,-1,0
  3636.8     0.1       0  4608.6    0.07       0  4804.0     0.1       0
  4893.8    0.07       0  4996.5     0.1       0  5040.8    0.07       0
  5046.9     0.1       0
Bank Sta=5040.8,5046.9
Exp/Cntr=0.3,0.1

Type RM Length L Ch R = 1,2167,224,224,224
BEGIN DESCRIPTION:
Mapping XS 34189ead
END DESCRIPTION:
XS GIS Cut Line= 2
      2059998.27     13435155.80      2058982.68     13435286.00
#Sta/Elev= 30
  4563.6  357.56  4726.3  356.79  4778.5  356.02  4849.2  354.28  4869.4  352.35
  4889.5  349.06  4907.9  347.40  4913.0  345.76  4967.2  344.55  4967.7  343.75
  4972.7  343.75  4973.2  344.55  5040.7  345.31  5050.8  345.99  5067.2  348.57
  5091.2  350.43  5111.3  350.42  5146.9  348.83  5151.9  349.61  5181.9  349.96
  5221.5  353.06  5232.3  354.72  5262.5  351.12  5301.1  350.76  5380.8  353.78
  5403.7  353.91  5444.0  357.06  5472.3  357.97  5514.6  360.05  5587.5  361.03
#Mann=6,-1,0
  4563.6     0.1       0  4726.3    0.07       0  4778.5     0.1       0
  4967.2    0.07       0  4973.2     0.1       0  5472.3    0.05       0
Bank Sta=4967.2,4973.2
Exp/Cntr=0.3,0.1

Type RM Length L Ch R = 1,1943,195,195,195
BEGIN DESCRIPTION:
Mapping XS 0c3e22e0
END DESCRIPTION:
XS GIS Cut Line= 4
      2059940.94     13435025.59      2059685.77     13435025.59
      2059339.42     13435007.36      2058974.81     13435093.30
#Sta/Elev= 30
  4529.1  357.35  4695.0  355.78  4815.1  353.36  4895.4  348.62  4945.3  344.97
  4992.3  343.34  4992.8  342.54  4997.8  342.54  4998.3  343.34  5015.4  344.14
  5035.4  347.13  5075.4  351.30  5080.7  352.65  5141.7  356.13  5166.5  356.89
  5231.5  357.01  5258.9  357.42  5316.2  357.30  5340.4  356.86  5358.5  355.77
  5363.7  354.59  5371.9  354.00  5400.9  355.16  5406.0  354.81  5423.3  354.82
  5443.2  355.34  5448.4  354.88  5464.4  355.73  5485.0  355.80  5505.7  356.69
#Mann=4,-1,0
  4529.1     0.1       0  4992.3    0.07       0  4998.3     0.1       0
  5340.4    0.05       0
Bank Sta=4992.3,4998.3
Exp/Cntr=0.3,0.1

Type RM Length L Ch R = 1,1748,56,56,56
BEGIN DESCRIPTION:
Mapping XS e8f4542f
END DESCRIPTION:
XS GIS Cut Line= 6
      2059917.56     13434986.53      2059638.90     13434996.94
      2059532.13     13434830.28      2059422.75     13434825.07
      2059308.17     13434838.09      2058962.83     13435040.62
#Sta/Elev= 30
  4515.2  357.40  4567.8  356.90  4737.9  353.54  4798.4  351.34  4820.3  348.73
  4826.6  348.78  4841.1  346.71  4890.9  344.47  4966.8  342.97  4969.1  342.36
  4969.6  341.56  4974.6  341.56  4975.1  342.36  5010.9  342.95  5050.9  344.64
  5099.6  347.80  5141.2  348.84  5151.6  350.30  5161.4  350.83  5191.5  351.49
  5225.2  353.66  5240.9  353.60  5246.7  354.86  5256.5  354.67  5262.3  355.64
  5391.5  356.87  5401.1  357.39  5416.8  357.02  5459.7  357.61  5618.9  357.26
#Mann=4,-1,0
  4515.2     0.1       0  4969.1    0.07       0  4975.1     0.1       0
  5391.5    0.05       0
Bank Sta=4969.1,4975.1
Exp/Cntr=0.3,0.1

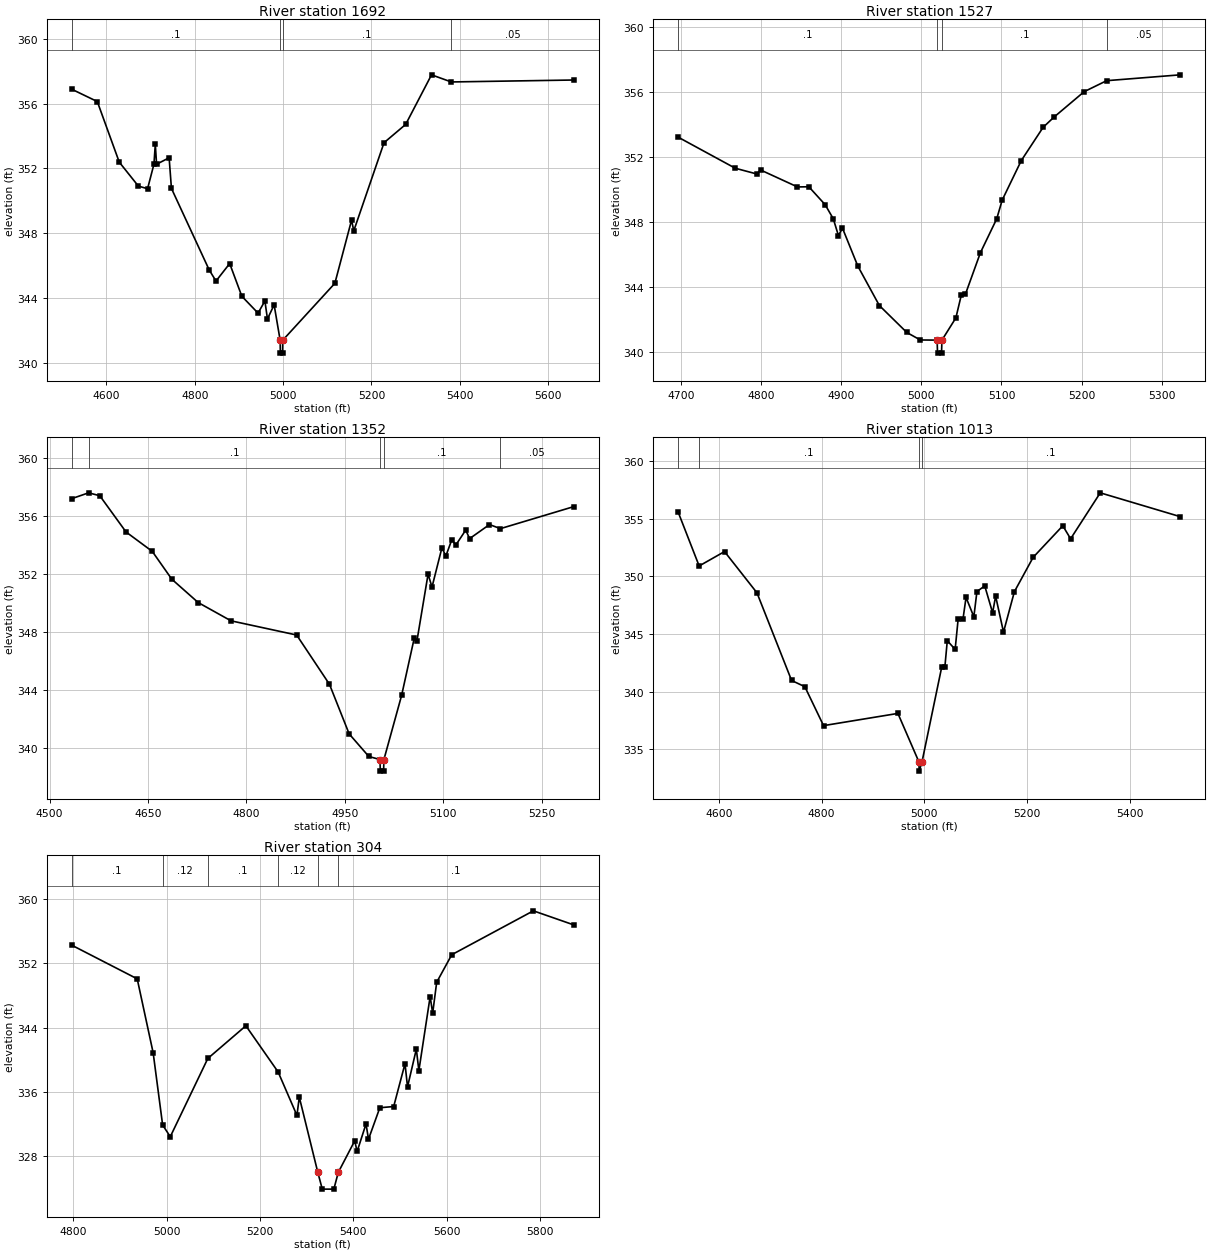
Type RM Length L Ch R = 1,1692,165,165,165
BEGIN DESCRIPTION:
Mapping XS b86d7cd8
END DESCRIPTION:
XS GIS Cut Line= 6
      2059883.69     13434832.88      2059735.25     13434950.07
      2059636.30     13434921.42      2059550.36     13434778.19
      2059289.94     13434783.40      2058933.21     13434994.32
#Sta/Elev= 30
  4521.6  356.89  4579.4  356.13  4629.1  352.39  4672.4  350.91  4693.2  350.75
  4707.6  352.26  4710.7  353.49  4713.6  352.26  4742.0  352.66  4747.2  350.77
  4832.8  345.73  4848.1  345.05  4879.1  346.13  4906.6  344.11  4943.3  343.07
  4958.8  343.82  4964.6  342.71  4979.7  343.58  4993.3  341.40  4993.8  340.60
  4998.8  340.60  4999.3  341.40  5117.2  344.91  5155.0  348.81  5160.0  348.15
  5228.5  353.59  5277.5  354.72  5336.0  357.78  5380.8  357.34  5658.2  357.46
#Mann=4,-1,0
  4521.6     0.1       0  4993.3    0.07       0  4999.3     0.1       0
  5380.8    0.05       0
Bank Sta=4993.3,4999.3
Exp/Cntr=0.3,0.1

Type RM Length L Ch R = 1,1527,175,175,175
BEGIN DESCRIPTION:
Mapping XS 99e27ec2
END DESCRIPTION:
XS GIS Cut Line= 2
      2059724.82     13434590.70      2059110.28     13434713.08
#Sta/Elev= 30
  4696.6  353.19  4767.8  351.28  4794.4  350.93  4799.5  351.17  4845.4  350.13
  4859.6  350.14  4879.9  349.04  4890.1  348.17  4896.5  347.14  4901.6  347.59
  4920.7  345.26  4947.6  342.83  4981.9  341.17  4998.7  340.71  5019.7  340.70
  5020.2  339.90  5025.2  339.90  5025.7  340.70  5043.1  342.07  5049.8  343.46
  5054.9  343.51  5073.7  346.08  5094.1  348.17  5100.9  349.32  5124.7  351.75
  5152.0  353.80  5165.4  354.42  5203.1  355.99  5231.3  356.67  5323.2  357.03
#Mann=4,-1,0
  4696.6     0.1       0  5019.7    0.07       0  5025.7     0.1       0
  5231.3    0.05       0
Bank Sta=5019.7,5025.7
Exp/Cntr=0.3,0.1

Type RM Length L Ch R = 1,1352,339,339,339
BEGIN DESCRIPTION:
Mapping XS 070e9887
END DESCRIPTION:
XS GIS Cut Line= 3
      2059857.67     13434476.11      2059331.61     13434489.13
      2059131.09     13434619.33
#Sta/Elev= 30
  4533.9  357.18  4559.6  357.58  4576.6  357.38  4616.6  354.88  4656.6  353.54
  4686.4  351.62  4726.6  350.01  4776.6  348.75  4876.7  347.77  4926.7  344.37
  4956.7  340.95  4986.7  339.39  5003.7  339.18  5004.2  338.38  5009.2  338.38
  5009.7  339.18  5036.7  343.61  5055.9  347.55  5060.1  347.38  5077.0  351.97
  5083.0  351.08  5098.1  353.79  5104.1  353.22  5113.3  354.36  5119.2  353.97
  5134.4  355.01  5140.3  354.42  5170.6  355.39  5187.3  355.11  5299.2  356.63
#Mann=5,-1,0
  4533.9    0.05       0  4559.6     0.1       0  5003.7    0.07       0
  5009.7     0.1       0  5187.3    0.05       0
Bank Sta=5003.7,5009.7
Exp/Cntr=0.3,0.1

Type RM Length L Ch R = 1,1013,709,709,709
BEGIN DESCRIPTION:
Mapping XS b666cc4c
END DESCRIPTION:
XS GIS Cut Line= 3
      2059960.11     13434332.02      2059472.23     13434161.87
      2059226.51     13434551.22
#Sta/Elev= 30
  4520.9  355.56  4561.6  350.90  4611.0  352.15  4674.1  348.57  4741.5  340.96
  4767.3  340.42  4803.7  337.04  4948.4  338.10  4989.3  333.89  4989.8  333.09
  4995.3  333.89  5033.5  342.09  5039.7  342.09  5044.5  344.41  5059.8  343.66
  5065.7  346.32  5075.1  346.30  5081.0  348.17  5096.2  346.49  5102.2  348.68
  5117.4  349.17  5132.7  346.84  5138.6  348.28  5153.9  345.16  5175.1  348.67
  5211.6  351.65  5269.3  354.39  5284.5  353.26  5342.2  357.25  5498.0  355.18
#Mann=4,-1,0
  4520.9    0.05       0  4561.6     0.1       0  4989.3    0.07       0
  4995.3     0.1       0
Bank Sta=4989.3,4995.3
Exp/Cntr=0.3,0.1

Type RM Length L Ch R = 1,304,0,0,0
BEGIN DESCRIPTION:
UNT 083 in RCW 1.0
END DESCRIPTION:
XS GIS Cut Line= 3
      2060003.45     13433922.30      2059446.19     13434012.57
      2059256.95     13434488.28
#Sta/Elev= 30
  4796.5  354.28  4936.8  350.08  4971.0  340.85  4991.3  331.84  5007.7  330.37
  5088.2  340.14  5169.8  344.22  5239.0  338.45  5279.3  333.03  5284.3  335.32
  5324.0  325.93  5333.6  323.83  5358.4  323.83  5368.0  325.93  5403.1  329.85
  5408.4  328.54  5427.4  331.97  5432.7  330.06  5457.0  333.99  5486.7  334.14
  5511.0  339.49  5516.4  336.59  5535.3  341.31  5540.7  338.61  5564.9  347.87
  5570.3  345.78  5578.9  349.65  5611.2  353.09  5786.2  358.57  5873.0  356.81
#Mann=6,-1,0
  4796.5     0.1       0  4991.3    0.12       0  5088.2     0.1       0
  5239.0    0.12       0  5324.0    0.07       0  5368.0     0.1       0
Bank Sta=5324,5368
Exp/Cntr=0.3,0.1

Chan Stop Cuts=-1