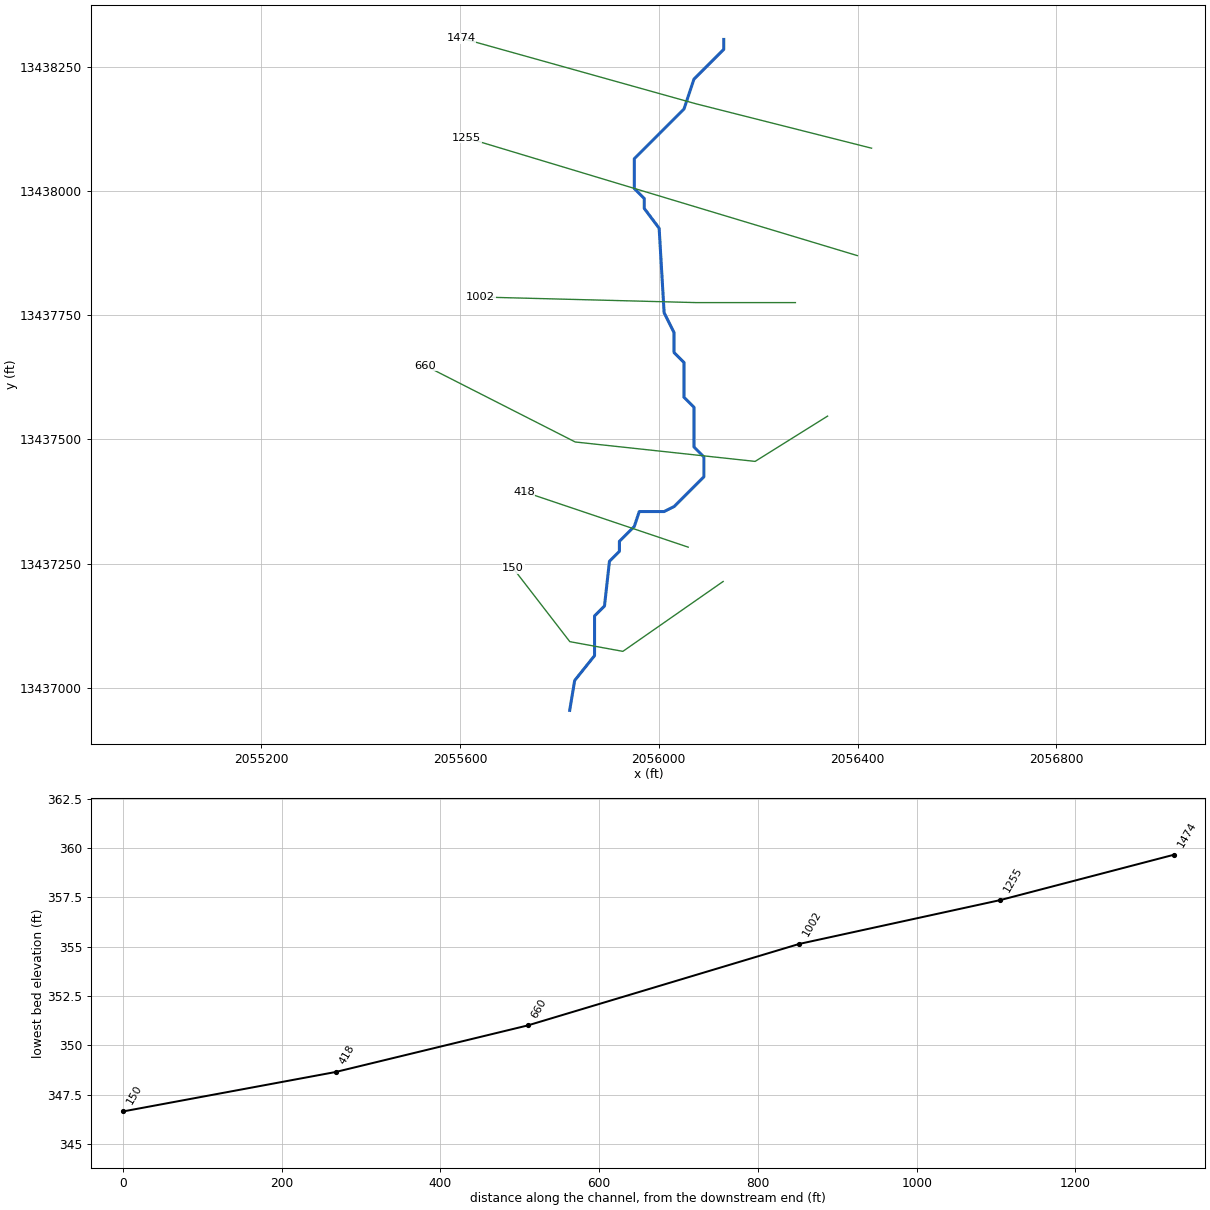
--- UNT 084 in RCW.prj (project) ---

Proj Title=UNT 084 in RCW Base Level Engineering
Current Plan=p01
Default Exp/Contr=0.3,0.1
English Units
Geom File=g01
Flow File=f01
Plan File=p01
BEGIN DESCRIPTION:
UNT 084 in RCW
END DESCRIPTION:

--- UNT 084 in RCW.p01 (plan) ---

Plan Title=Multiple Run
Short Identifier=Multiple
Geom File=g01
Flow File=f01
Subcritical Flow
K Sum by GR= 0
Std Step Tol= 0.01
Critical Tol= 0.01
Num of Std Step Trials= 20
Max Error Tol= 0.3
Flow Tol Ratio= 0.001
Split Flow NTrial= 30
Split Flow Tol= 0.02
Split Flow Ratio= 0.02
Log Output Level= 0
Friction Slope Method= 1
Unsteady Friction Slope Method= 2
Unsteady Bridges Friction Slope Method= 1
Parabolic Critical Depth
Global Vel Dist=  1 , 1 , 1
Global Log Level= 0
CheckData=True
Encroach Param= -1, 0, 0, 0
BEGIN DESCRIPTION:
Multiple Run
END DESCRIPTION:

--- UNT 084 in RCW.f01 (steady flow) ---

Flow Title=Multiple
Number of Profiles=7
Profile Names=10-year,25-year,50-year,1pct_min,100-year,1pct_plu,500-year
River Rch & RM= UNT 084 in RCW,Reach-1,1474
      82     108     128      76     152     303     218
Boundary for River Rch & Prof#=UNT 084 in RCW,Reach-1,1
Up Type=0
Dn Type=3
Dn Slope=0.005
Boundary for River Rch & Prof#=UNT 084 in RCW,Reach-1,2
Up Type=0
Dn Type=3
Dn Slope=0.005
Boundary for River Rch & Prof#=UNT 084 in RCW,Reach-1,3
Up Type=0
Dn Type=3
Dn Slope=0.005
Boundary for River Rch & Prof#=UNT 084 in RCW,Reach-1,4
Up Type=0
Dn Type=3
Dn Slope=0.005
Boundary for River Rch & Prof#=UNT 084 in RCW,Reach-1,5
Up Type=0
Dn Type=3
Dn Slope=0.005
Boundary for River Rch & Prof#=UNT 084 in RCW,Reach-1,6
Up Type=0
Dn Type=3
Dn Slope=0.005
Boundary for River Rch & Prof#=UNT 084 in RCW,Reach-1,7
Up Type=0
Dn Type=3
Dn Slope=0.005

--- UNT 084 in RCW.g01 (geometry) ---

Geom Title=Existing Conditions

River Reach=UNT 084 in RCW,Reach-1
Reach XY= 30
      2056130.80     13438304.54      2056130.80     13438284.54
      2056070.80     13438224.54      2056050.80     13438164.54
      2055950.80     13438064.54      2055950.80     13438004.54
      2055970.80     13437984.54      2055970.80     13437964.54
      2056000.80     13437924.54      2056010.80     13437754.54
      2056030.80     13437714.54      2056030.80     13437674.54
      2056050.80     13437654.54      2056050.80     13437584.54
      2056070.80     13437564.54      2056070.80     13437484.54
      2056090.80     13437464.54      2056090.80     13437424.54
      2056030.80     13437364.54      2056010.80     13437354.54
      2055960.80     13437354.54      2055950.80     13437324.54
      2055920.80     13437294.54      2055920.80     13437274.54
      2055900.80     13437254.54      2055890.80     13437164.54
      2055870.80     13437144.54      2055870.80     13437064.54
      2055830.80     13437014.54      2055820.80     13436954.54

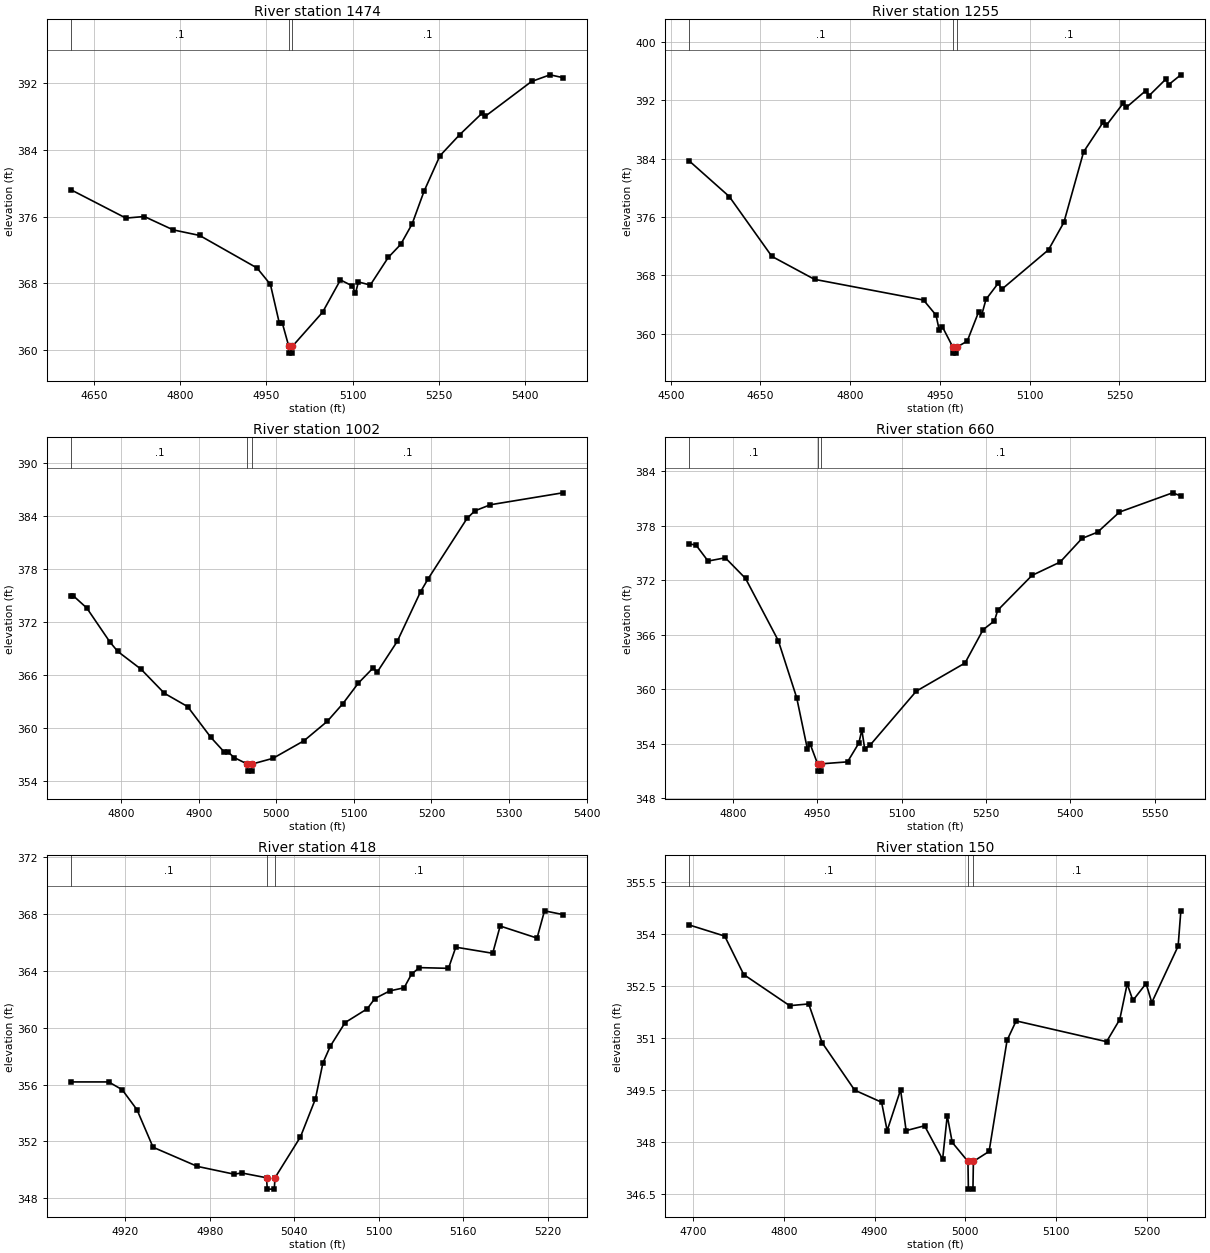
Type RM Length L Ch R = 1,1474,219,219,219
BEGIN DESCRIPTION:
UNT 084 in RCW 3.0
END DESCRIPTION:
XS GIS Cut Line= 3
      2056428.26     13438085.69      2056075.00     13438175.00
      2055602.78     13438307.03
#Sta/Elev= 30
  4610.5  379.22  4705.6  375.84  4737.6  376.03  4787.7  374.43  4833.8  373.76
  4933.6  369.86  4956.9  367.89  4972.3  363.28  4977.5  363.28  4988.9  360.45
  4989.4  359.65  4994.4  359.65  4994.9  360.45  5047.6  364.55  5078.7  368.43
  5099.5  367.70  5104.8  366.80  5109.9  368.19  5130.6  367.81  5161.8  371.12
  5183.4  372.68  5203.3  375.13  5224.1  379.06  5251.7  383.31  5285.9  385.83
  5325.2  388.43  5330.4  388.04  5411.0  392.22  5443.2  393.02  5465.2  392.69
#Mann=3,-1,0
  4610.5     0.1       0  4988.9    0.07       0  4994.9     0.1       0
Bank Sta=4988.9,4994.9
Exp/Cntr=0.3,0.1

Type RM Length L Ch R = 1,1255,253,253,253
BEGIN DESCRIPTION:
Mapping XS 900a70e4
END DESCRIPTION:
XS GIS Cut Line= 2
      2056399.66     13437869.53      2055613.19     13438106.51
#Sta/Elev= 30
  4531.2  383.69  4597.8  378.83  4669.0  370.62  4740.3  367.47  4922.5  364.63
  4943.4  362.56  4948.7  360.53  4953.9  360.98  4971.7  358.15  4972.2  357.35
  4977.2  357.35  4977.7  358.15  4995.6  359.00  5014.7  363.02  5019.9  362.63
  5026.9  364.72  5047.7  366.97  5052.9  366.08  5131.4  371.52  5157.1  375.28
  5190.1  384.96  5223.1  389.06  5228.3  388.61  5256.1  391.60  5261.3  391.04
  5294.3  393.37  5299.5  392.66  5327.3  394.91  5332.5  394.19  5352.6  395.52
#Mann=3,-1,0
  4531.2     0.1       0  4971.7    0.07       0  4977.7     0.1       0
Bank Sta=4971.7,4977.7
Exp/Cntr=0.3,0.1

Type RM Length L Ch R = 1,1002,342,342,342
BEGIN DESCRIPTION:
UNT 084 in RCW 2.0
END DESCRIPTION:
XS GIS Cut Line= 3
      2056274.98     13437775.00      2056075.00     13437775.00
      2055641.82     13437786.21
#Sta/Elev= 30
  4735.8  374.98  4738.3  374.98  4755.8  373.59  4785.8  369.72  4795.8  368.67
  4825.8  366.66  4855.8  363.94  4885.8  362.43  4915.8  358.94  4933.3  357.26
  4938.3  357.26  4945.8  356.66  4962.8  355.93  4963.3  355.13  4968.3  355.13
  4968.8  355.93  4995.8  356.58  5035.8  358.57  5065.8  360.77  5085.8  362.76
  5105.8  365.09  5125.0  366.82  5130.0  366.32  5155.9  369.81  5185.9  375.42
  5195.9  376.92  5245.9  383.73  5255.9  384.58  5275.9  385.27  5369.1  386.62
#Mann=3,-1,0
  4735.8     0.1       0  4962.8    0.07       0  4968.8     0.1       0
Bank Sta=4962.8,4968.8
Exp/Cntr=0.3,0.1

Type RM Length L Ch R = 1,660,242,242,242
BEGIN DESCRIPTION:
Mapping XS 78e05a59
END DESCRIPTION:
XS GIS Cut Line= 4
      2056339.73     13437546.62      2056193.90     13437455.48
      2055831.92     13437494.54      2055529.89     13437648.16
#Sta/Elev= 30
  4722.0  376.02  4734.0  375.86  4755.2  374.12  4785.9  374.48  4821.9  372.21
  4880.2  365.37  4913.0  359.08  4932.1  353.42  4937.1  353.96  4950.2  351.80
  4950.7  351.00  4955.7  351.00  4956.2  351.80  5003.5  352.02  5023.6  354.08
  5029.0  355.54  5034.0  353.48  5043.7  353.86  5125.9  359.80  5212.7  362.90
  5244.9  366.57  5265.1  367.54  5270.8  368.70  5331.9  372.54  5382.0  374.01
  5420.9  376.61  5448.7  377.30  5487.6  379.51  5582.2  381.63  5596.9  381.29
#Mann=3,-1,0
  4722.0     0.1       0  4950.2    0.07       0  4956.2     0.1       0
Bank Sta=4950.2,4956.2
Exp/Cntr=0.3,0.1

Type RM Length L Ch R = 1,418,268,268,268
BEGIN DESCRIPTION:
Mapping XS cc32e6ad
END DESCRIPTION:
XS GIS Cut Line= 2
      2056059.29     13437282.88      2055728.59     13437394.41
#Sta/Elev= 30
  4881.5  356.19  4908.1  356.19  4917.7  355.64  4928.2  354.23  4939.6  351.59
  4971.1  350.24  4997.3  349.69  5002.5  349.78  5020.2  349.44  5020.7  348.64
  5025.7  348.64  5026.2  349.44  5044.3  352.32  5054.9  354.99  5060.2  357.52
  5065.5  358.71  5076.0  360.37  5091.7  361.34  5097.1  362.06  5107.7  362.60
  5117.9  362.82  5123.2  363.79  5128.8  364.24  5149.4  364.19  5154.6  365.68
  5180.8  365.25  5186.1  367.17  5212.3  366.32  5217.6  368.24  5230.5  367.98
#Mann=3,-1,0
  4881.5     0.1       0  5020.2    0.07       0  5026.2     0.1       0
Bank Sta=5020.2,5026.2
Exp/Cntr=0.3,0.1

Type RM Length L Ch R = 1,150,0,0,0
BEGIN DESCRIPTION:
UNT 084 in RCW 1.0
END DESCRIPTION:
XS GIS Cut Line= 4
      2056129.60     13437213.86      2055927.79     13437073.24
      2055821.02     13437092.77      2055706.88     13437240.64
#Sta/Elev= 30
  4696.1  354.27  4735.0  353.95  4755.9  352.84  4806.5  351.94  4827.5  351.99
  4842.3  350.87  4878.1  349.50  4907.8  349.15  4913.9  348.33  4928.7  349.51
  4934.8  348.33  4955.1  348.47  4975.0  347.50  4980.1  348.76  4985.6  347.99
  5002.9  347.44  5003.4  346.64  5008.4  346.64  5008.9  347.44  5026.2  347.73
  5046.0  350.94  5056.0  351.50  5155.6  350.90  5170.1  351.54  5178.3  352.57
  5184.6  352.09  5199.1  352.58  5205.4  352.03  5234.4  353.66  5237.4  354.68
#Mann=3,-1,0
  4696.1     0.1       0  5002.9    0.07       0  5008.9     0.1       0
Bank Sta=5002.9,5008.9
Exp/Cntr=0.3,0.1

Chan Stop Cuts=-1