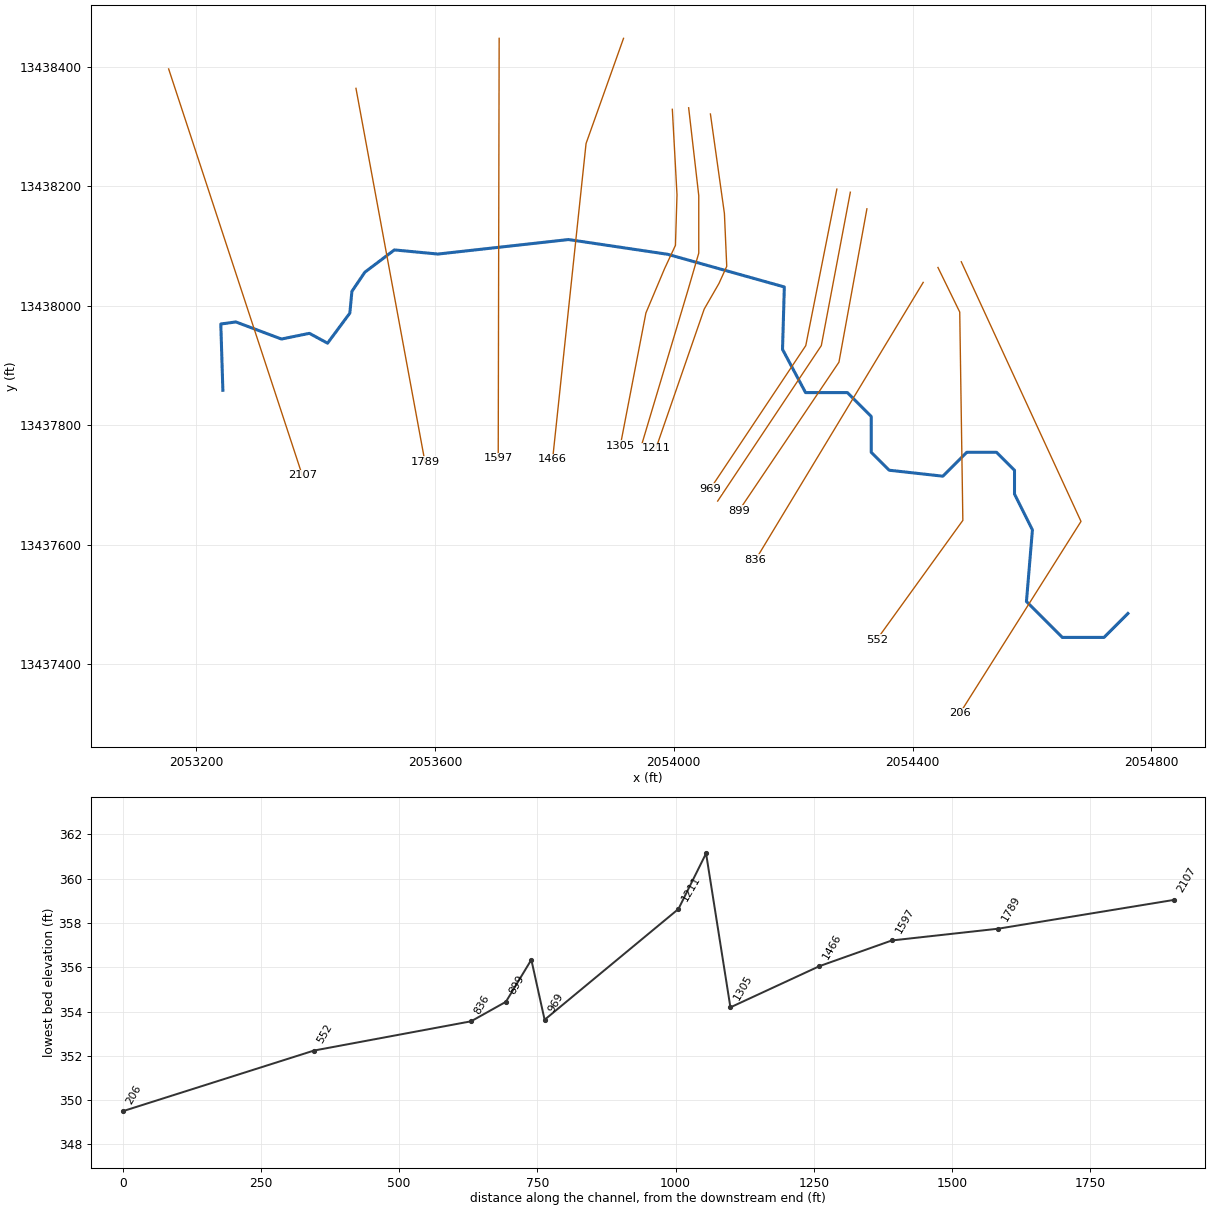
--- UNT 085 in RCW.prj (project) ---

Proj Title=UNT 085 in RCW Base Level Engineering
Current Plan=p01
Default Exp/Contr=0.3,0.1
English Units
Geom File=g01
Flow File=f01
Plan File=p01
BEGIN DESCRIPTION:
UNT 085 in RCW
END DESCRIPTION:

--- UNT 085 in RCW.p01 (plan) ---

Plan Title=Multiple Run
Short Identifier=Multiple
Geom File=g01
Flow File=f01
Subcritical Flow
K Sum by GR= 0
Std Step Tol= 0.01
Critical Tol= 0.01
Num of Std Step Trials= 20
Max Error Tol= 0.3
Flow Tol Ratio= 0.001
Split Flow NTrial= 30
Split Flow Tol= 0.02
Split Flow Ratio= 0.02
Log Output Level= 0
Friction Slope Method= 1
Unsteady Friction Slope Method= 2
Unsteady Bridges Friction Slope Method= 1
Parabolic Critical Depth
Global Vel Dist=  1 , 1 , 1
Global Log Level= 0
CheckData=True
Encroach Param= -1, 0, 0, 0
BEGIN DESCRIPTION:
Multiple Run
END DESCRIPTION:

--- UNT 085 in RCW.f01 (steady flow) ---

Flow Title=Multiple
Number of Profiles=7
Profile Names=10-year,25-year,50-year,1pct_min,100-year,1pct_plu,500-year
River Rch & RM= UNT 085 in RCW,Reach-1,2107
      90     116     136      80     159     318     221
Boundary for River Rch & Prof#=UNT 085 in RCW,Reach-1,1
Up Type=0
Dn Type=3
Dn Slope=0.005
Boundary for River Rch & Prof#=UNT 085 in RCW,Reach-1,2
Up Type=0
Dn Type=3
Dn Slope=0.005
Boundary for River Rch & Prof#=UNT 085 in RCW,Reach-1,3
Up Type=0
Dn Type=3
Dn Slope=0.005
Boundary for River Rch & Prof#=UNT 085 in RCW,Reach-1,4
Up Type=0
Dn Type=3
Dn Slope=0.005
Boundary for River Rch & Prof#=UNT 085 in RCW,Reach-1,5
Up Type=0
Dn Type=3
Dn Slope=0.005
Boundary for River Rch & Prof#=UNT 085 in RCW,Reach-1,6
Up Type=0
Dn Type=3
Dn Slope=0.005
Boundary for River Rch & Prof#=UNT 085 in RCW,Reach-1,7
Up Type=0
Dn Type=3
Dn Slope=0.005

--- UNT 085 in RCW.g01 (geometry) ---

Geom Title=Existing Conditions

River Reach=UNT 085 in RCW,Reach-1
Reach XY= 30
      2053244.69     13437858.36      2053241.22     13437969.47
      2053266.40     13437972.94      2053342.78     13437944.30
      2053389.66     13437953.84      2053420.04     13437937.35
      2053457.37     13437987.70      2053460.84     13438024.16
      2053482.54     13438056.27      2053532.02     13438093.60
      2053604.94     13438086.66      2053823.69     13438110.96
      2053989.92     13438086.22      2054185.23     13438031.54
      2054182.19     13437926.97      2054220.80     13437854.54
      2054290.80     13437854.54      2054330.80     13437814.54
      2054330.80     13437754.54      2054360.80     13437724.54
      2054450.80     13437714.54      2054490.80     13437754.54
      2054540.80     13437754.54      2054570.80     13437724.54
      2054570.80     13437684.54      2054600.80     13437624.54
      2054590.80     13437504.54      2054650.80     13437444.54
      2054720.80     13437444.54      2054760.80     13437484.54

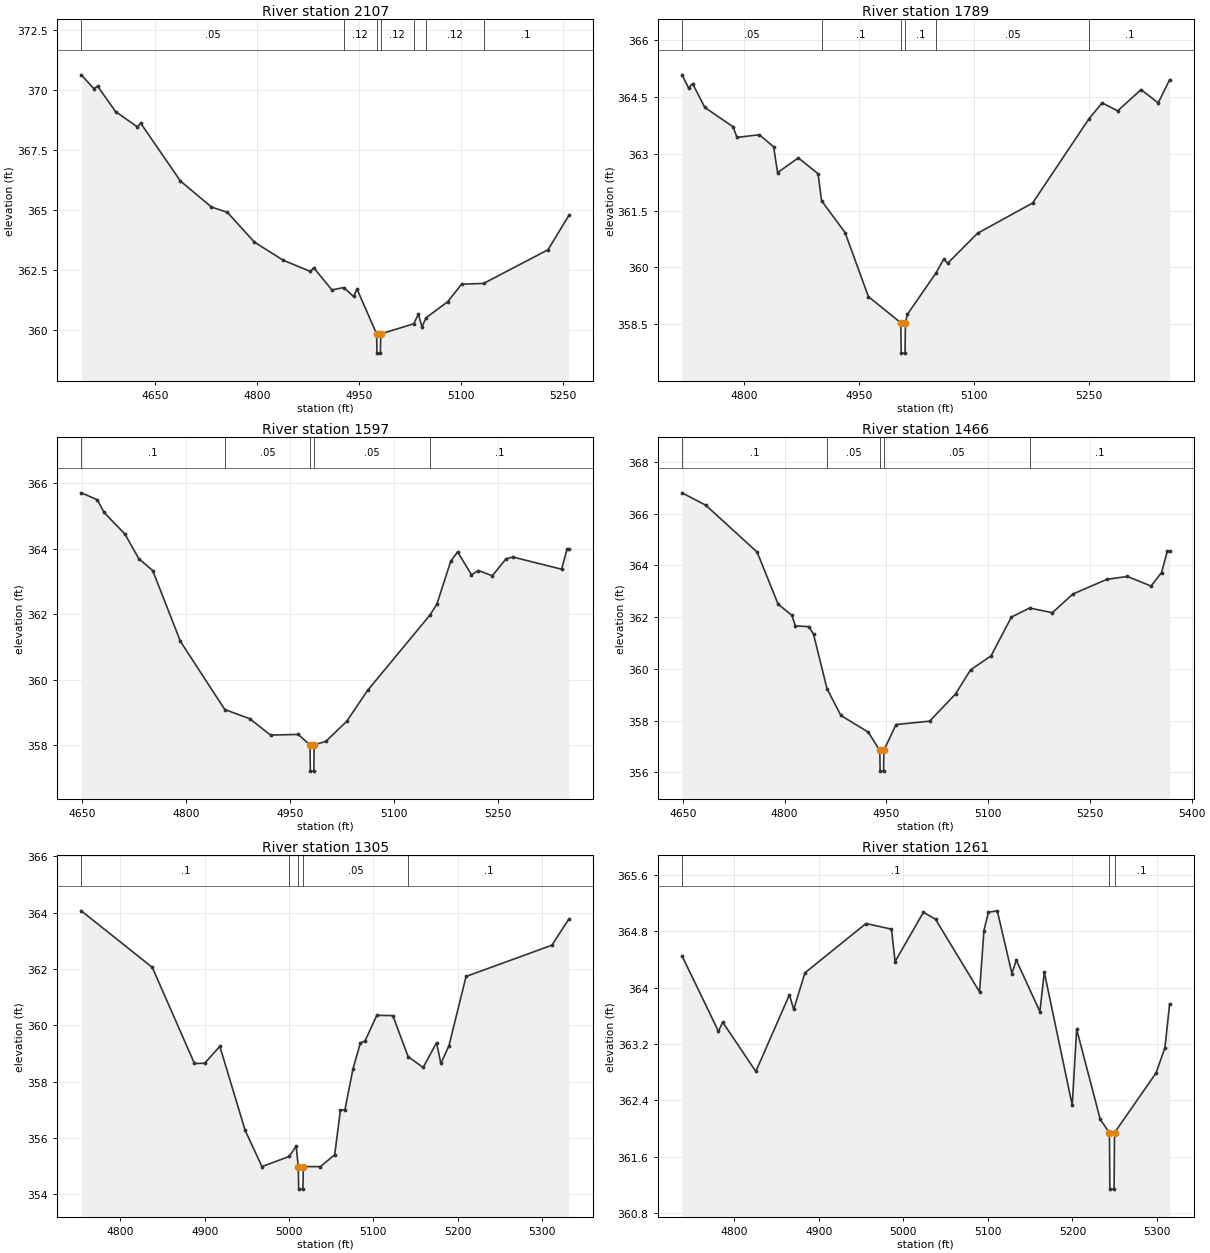
Type RM Length L Ch R = 1,2107,318,318,318
BEGIN DESCRIPTION:
UNT 085 in RCW 5.0
END DESCRIPTION:
XS GIS Cut Line= 2
      2053153.87     13438396.77      2053377.81     13437715.85
#Sta/Elev= 30
  4541.5  370.62  4560.1  370.04  4565.4  370.15  4591.9  369.09  4623.7  368.46
  4629.0  368.60  4687.3  366.20  4732.8  365.12  4756.2  364.90  4796.0  363.66
  4838.1  362.91  4878.1  362.44  4883.3  362.59  4909.9  361.67  4927.4  361.77
  4941.7  361.40  4946.9  361.70  4975.7  359.84  4976.2  359.04  4981.2  359.04
  4981.7  359.84  5030.2  360.26  5037.1  360.66  5042.3  360.13  5048.3  360.51
  5080.2  361.18  5100.6  361.91  5133.0  361.94  5227.6  363.34  5258.3  364.77
#Mann=7,-1,0
  4541.5    0.05       0  4927.4    0.12       0  4975.7    0.07       0
  4981.7    0.12       0  5030.2    0.05       0  5048.3    0.12       0
  5133.0     0.1       0
Bank Sta=4975.7,4981.7
Exp/Cntr=0.3,0.1

Type RM Length L Ch R = 1,1789,192,192,192
BEGIN DESCRIPTION:
UNT 085 in RCW 6.0
END DESCRIPTION:
XS GIS Cut Line= 2
      2053467.66     13438364.24      2053583.24     13437738.32
#Sta/Elev= 30
  4718.6  365.08  4727.2  364.73  4732.3  364.85  4748.3  364.22  4785.2  363.71
  4790.3  363.43  4819.5  363.50  4838.2  363.18  4843.3  362.50  4870.4  362.89
  4896.2  362.47  4900.7  361.76  4931.4  360.92  4961.9  359.23  5004.2  358.54
  5004.7  357.74  5009.7  357.74  5010.2  358.54  5012.7  358.76  5050.3  359.86
  5060.2  360.22  5065.3  360.11  5104.3  360.90  5176.3  361.70  5249.8  363.92
  5267.0  364.34  5287.3  364.13  5317.8  364.69  5340.2  364.34  5355.1  364.95
#Mann=6,-1,0
  4718.6    0.05       0  4900.7     0.1       0  5004.2    0.07       0
  5010.2     0.1       0  5050.3    0.05       0  5249.8     0.1       0
Bank Sta=5004.2,5010.2
Exp/Cntr=0.3,0.1

Type RM Length L Ch R = 1,1597,131,131,131
BEGIN DESCRIPTION:
UNT 085 in RCW 7.0
END DESCRIPTION:
XS GIS Cut Line= 2
      2053707.51     13438448.00      2053705.94     13437744.50
#Sta/Elev= 30
  4648.3  365.70  4671.3  365.49  4681.3  365.10  4711.3  364.44  4731.3  363.69
  4751.3  363.33  4791.3  361.17  4855.3  359.09  4891.3  358.81  4921.3  358.31
  4961.3  358.33  4978.3  358.01  4978.8  357.21  4983.8  357.21  4984.3  358.01
  5001.3  358.12  5031.3  358.73  5061.3  359.67  5151.3  361.97  5161.3  362.30
  5181.3  363.61  5191.3  363.90  5211.3  363.20  5221.3  363.33  5241.3  363.17
  5261.3  363.69  5271.3  363.74  5341.3  363.37  5349.1  363.98  5351.8  363.98
#Mann=5,-1,0
  4648.3     0.1       0  4855.3    0.05       0  4978.3   0.033       0
  4984.3    0.05       0  5151.3     0.1       0
Bank Sta=4978.3,4984.3
Exp/Cntr=0.3,0.1

Type RM Length L Ch R = 1,1466,161,161,161
BEGIN DESCRIPTION:
UNT 085 in RCW 8.0
END DESCRIPTION:
XS GIS Cut Line= 3
      2053915.85     13438448.02      2053853.08     13438271.81
      2053797.08     13437743.12
#Sta/Elev= 30
  4648.8  366.80  4683.9  366.32  4759.5  364.51  4790.4  362.50  4810.6  362.07
  4815.9  361.66  4835.9  361.63  4842.7  361.33  4862.4  359.24  4882.9  358.20
  4923.1  357.56  4940.3  356.85  4940.8  356.05  4945.8  356.05  4946.3  356.85
  4964.2  357.85  5013.7  357.98  5051.9  359.03  5074.0  359.96  5104.2  360.50
  5134.3  362.00  5161.0  362.35  5194.7  362.17  5224.8  362.89  5275.1  363.46
  5305.3  363.57  5340.1  363.20  5355.6  363.72  5364.0  364.54  5367.5  364.54
#Mann=5,-1,0
  4648.8     0.1       0  4862.4    0.05       0  4940.3   0.033       0
  4946.3    0.05       0  5161.0     0.1       0
Bank Sta=4940.3,4946.3
Exp/Cntr=0.3,0.1

Type RM Length L Ch R = 1,1305,44,44,44
BEGIN DESCRIPTION:
UNT 085 in RCW 9.0
END DESCRIPTION:
XS GIS Cut Line= 6
      2053997.61     13438329.14      2054005.42     13438185.88
      2054002.82     13438101.24      2053984.59     13438062.18
      2053953.34     13437987.96      2053910.36     13437765.26
#Sta/Elev= 30
  4753.5  364.07  4837.8  362.06  4887.8  358.65  4899.9  358.66  4917.9  359.26
  4947.9  356.28  4967.9  354.99  5000.3  355.35  5008.5  355.72  5011.0  354.99
  5011.5  354.19  5016.5  354.19  5017.0  354.99  5037.3  354.99  5054.2  355.41
  5061.0  356.99  5066.4  357.01  5075.9  358.46  5084.7  359.38  5090.2  359.45
  5104.2  360.36  5123.2  360.35  5141.4  358.89  5159.2  358.51  5175.1  359.39
  5180.2  358.65  5189.8  359.28  5210.1  361.74  5312.0  362.85  5332.1  363.78
#Mann=5,-1,0
  4753.5     0.1       0  5000.3    0.05       0  5011.0    0.07       0
  5017.0    0.05       0  5141.4     0.1       0
Bank Sta=5011,5017
Exp/Cntr=0.3,0.1

Type RM Length L Ch R = 1,1261,50,50,50
BEGIN DESCRIPTION:
UNT 085 in RCW 11.0
END DESCRIPTION:
XS GIS Cut Line= 5
      2054024.95     13438331.71      2054041.88     13438184.57
      2054041.88     13438088.22      2054023.65     13438025.72
      2053946.95     13437769.63
#Sta/Elev= 30
  4738.1  364.45  4781.2  363.38  4786.2  363.51  4825.4  362.81  4865.2  363.90
  4870.2  363.69  4883.5  364.21  4955.8  364.91  4985.9  364.83  4990.2  364.37
  5023.7  365.07  5038.0  364.97  5090.1  363.94  5095.3  364.81  5100.6  365.07
  5111.1  365.09  5128.4  364.20  5133.6  364.39  5161.5  363.66  5166.7  364.22
  5199.8  362.33  5205.0  363.41  5232.9  362.13  5243.8  361.94  5244.3  361.14
  5249.3  361.14  5249.8  361.94  5299.0  362.79  5309.5  363.15  5315.0  363.77
#Mann=3,-1,0
  4738.1     0.1       0  5243.8    0.07       0  5249.8     0.1       0
Bank Sta=5243.8,5249.8
Exp/Cntr=0.3,0.1

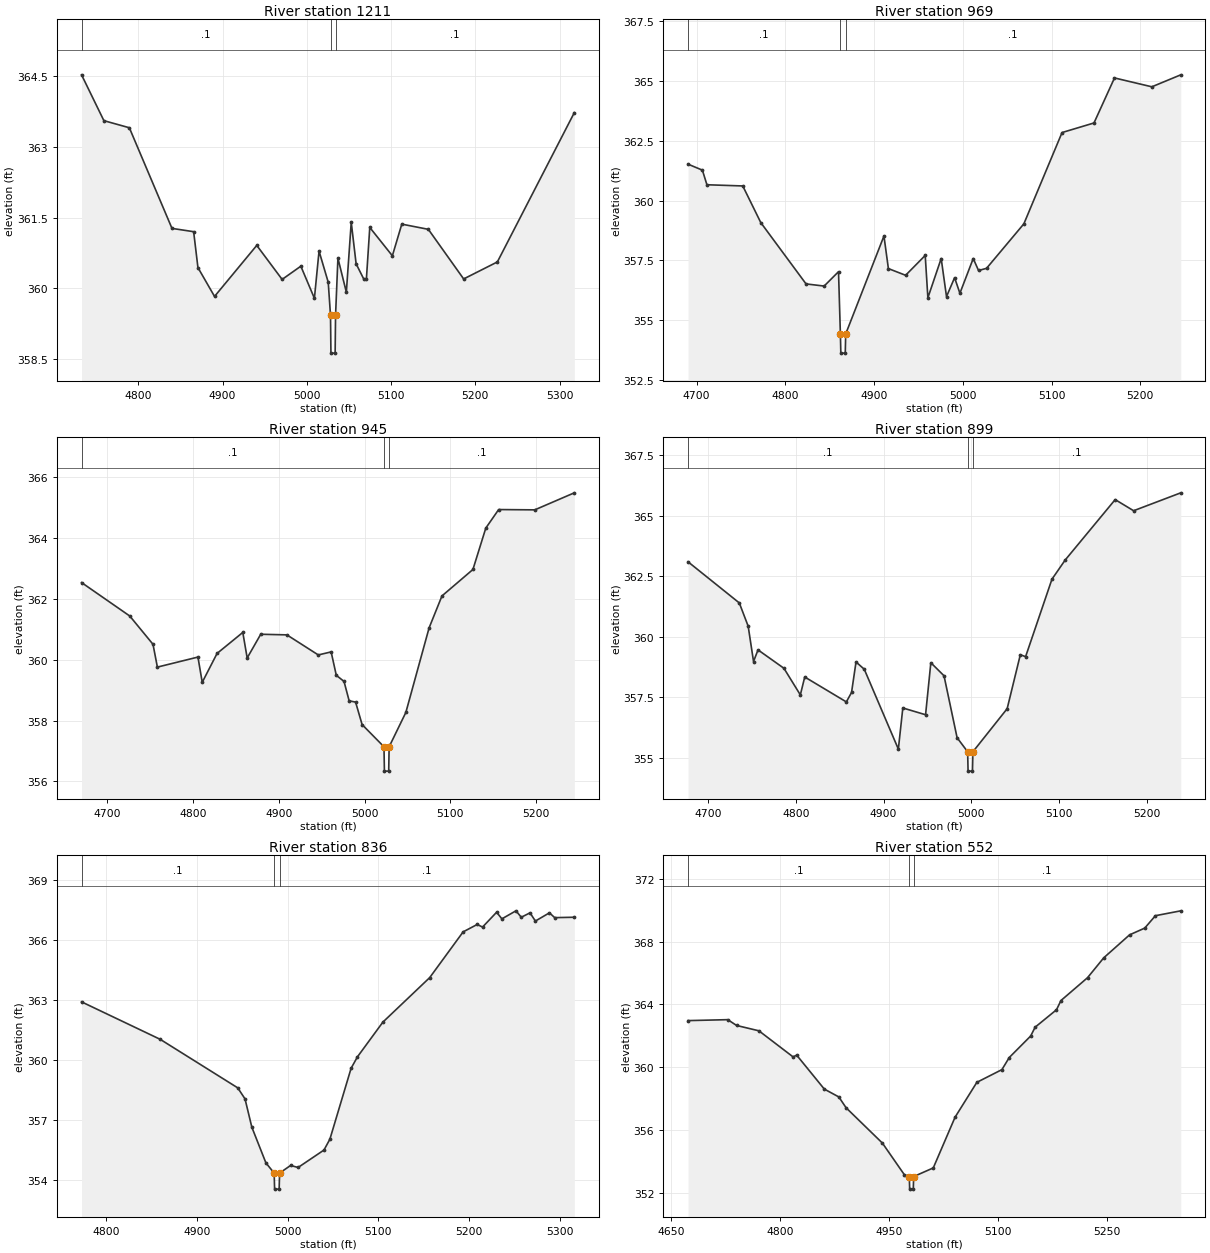
Type RM Length L Ch R = 1,1211,242,242,242
BEGIN DESCRIPTION:
UNT 085 in RCW 10.0
END DESCRIPTION:
XS GIS Cut Line= 6
      2054061.41     13438321.26      2054084.85     13438154.63
      2054088.75     13438066.08      2054075.73     13438037.44
      2054050.99     13437994.47      2053970.25     13437761.35
#Sta/Elev= 30
  4732.7  364.52  4759.2  363.55  4789.4  363.40  4840.0  361.27  4865.7  361.20
  4870.8  360.44  4890.5  359.83  4940.6  360.91  4970.7  360.19  4992.9  360.47
  5009.0  359.79  5014.5  360.79  5025.4  360.13  5028.1  359.43  5028.6  358.63
  5033.6  358.63  5034.1  359.43  5036.9  360.64  5046.9  359.92  5052.7  361.40
  5058.5  360.52  5067.5  360.20  5070.7  360.20  5074.7  361.29  5101.5  360.69
  5112.7  361.36  5144.2  361.25  5186.1  360.20  5226.1  360.56  5317.4  363.72
#Mann=3,-1,0
  4732.7     0.1       0  5028.1    0.07       0  5034.1     0.1       0
Bank Sta=5028.1,5034.1
Exp/Cntr=0.3,0.1

Type RM Length L Ch R = 1,969,24,24,24
BEGIN DESCRIPTION:
UNT 085 in RCW 3.0
END DESCRIPTION:
XS GIS Cut Line= 3
      2054273.23     13438195.47      2054221.13     13437933.27
      2054061.39     13437693.66
#Sta/Elev= 30
  4690.3  361.52  4706.5  361.27  4711.6  360.66  4752.0  360.61  4772.3  359.08
  4823.3  356.52  4843.7  356.43  4859.9  357.03  4862.0  354.43  4862.5  353.63
  4867.5  353.63  4868.0  354.43  4911.1  358.52  4916.1  357.16  4935.5  356.88
  4957.6  357.71  4960.6  355.94  4975.6  357.58  4981.6  355.99  4990.7  356.78
  4996.7  356.13  5011.7  357.58  5017.7  357.08  5026.7  357.17  5068.8  359.03
  5111.8  362.84  5147.8  363.24  5170.9  365.12  5213.0  364.75  5245.6  365.25
#Mann=3,-1,0
  4690.3     0.1       0  4862.0    0.07       0  4868.0     0.1       0
Bank Sta=4862,4868
Exp/Cntr=0.3,0.1

Type RM Length L Ch R = 1,945,46,46,46
BEGIN DESCRIPTION:
UNT 085 in RCW 4.0
END DESCRIPTION:
XS GIS Cut Line= 3
      2054295.79     13438190.25      2054247.17     13437933.27
      2054073.57     13437672.87
#Sta/Elev= 30
  4670.0  362.54  4726.2  361.44  4753.3  360.51  4758.4  359.76  4805.7  360.09
  4810.7  359.26  4828.0  360.21  4858.0  360.90  4863.1  360.06  4878.9  360.84
  4909.4  360.82  4946.0  360.16  4961.0  360.26  4967.0  359.49  4976.0  359.29
  4982.0  358.65  4989.5  358.61  4997.1  357.87  5022.6  357.14  5023.1  356.34
  5028.1  356.34  5028.6  357.14  5048.1  358.27  5075.2  361.05  5090.2  362.10
  5126.3  362.97  5141.3  364.33  5156.3  364.94  5198.4  364.93  5244.5  365.49
#Mann=3,-1,0
  4670.0     0.1       0  5022.6    0.07       0  5028.6     0.1       0
Bank Sta=5022.6,5028.6
Exp/Cntr=0.3,0.1

Type RM Length L Ch R = 1,899,63,63,63
BEGIN DESCRIPTION:
UNT 085 in RCW 2.0
END DESCRIPTION:
XS GIS Cut Line= 3
      2054323.56     13438162.41      2054276.69     13437905.49
      2054109.12     13437656.73
#Sta/Elev= 30
  4677.4  363.09  4735.8  361.39  4745.9  360.43  4752.0  358.97  4757.1  359.45
  4786.6  358.69  4805.3  357.59  4810.3  358.33  4857.7  357.30  4863.6  357.69
  4868.7  358.95  4878.1  358.65  4916.9  355.35  4922.0  357.05  4947.9  356.77
  4953.9  358.92  4968.9  358.38  4983.8  355.82  4995.8  355.24  4996.3  354.44
  5001.3  354.44  5001.8  355.24  5040.8  357.02  5055.8  359.25  5061.8  359.17
  5091.8  362.37  5106.8  363.16  5163.8  365.66  5184.8  365.20  5238.5  365.94
#Mann=3,-1,0
  4677.4     0.1       0  4995.8    0.07       0  5001.8     0.1       0
Bank Sta=4995.8,5001.8
Exp/Cntr=0.3,0.1

Type RM Length L Ch R = 1,836,284,284,284
BEGIN DESCRIPTION:
UNT 085 in RCW 12.0
END DESCRIPTION:
XS GIS Cut Line= 2
      2054417.85     13438039.17      2054137.04     13437574.54
#Sta/Elev= 30
  4773.0  362.90  4859.7  361.03  4945.1  358.61  4953.1  358.06  4960.6  356.65
  4976.1  354.87  4985.2  354.36  4985.7  353.56  4990.7  353.56  4991.2  354.36
  5003.3  354.74  5011.6  354.64  5040.1  355.51  5046.6  356.05  5070.0  359.59
  5077.0  360.16  5105.0  361.89  5156.6  364.11  5193.4  366.39  5208.9  366.76
  5214.8  366.63  5230.3  367.37  5236.1  367.04  5251.6  367.44  5257.5  367.12
  5267.1  367.34  5273.0  366.93  5288.5  367.34  5294.3  367.10  5315.9  367.12
#Mann=3,-1,0
  4773.0     0.1       0  4985.2    0.07       0  4991.2     0.1       0
Bank Sta=4985.2,4991.2
Exp/Cntr=0.3,0.1

Type RM Length L Ch R = 1,552,346,346,346
BEGIN DESCRIPTION:
UNT 085 in RCW 13.0
END DESCRIPTION:
XS GIS Cut Line= 4
      2054442.58     13438064.16      2054479.05     13437989.48
      2054484.26     13437640.52      2054340.19     13437440.90
#Sta/Elev= 30
  4673.8  362.97  4728.5  363.03  4740.7  362.66  4771.4  362.32  4818.4  360.66
  4823.4  360.77  4861.4  358.61  4881.4  358.11  4891.4  357.42  4941.4  355.17
  4971.4  353.17  4978.4  353.04  4978.9  352.24  4983.9  352.24  4984.4  353.04
  5011.4  353.59  5041.4  356.82  5071.4  359.04  5105.9  359.85  5116.0  360.62
  5145.5  361.99  5151.6  362.55  5181.0  363.66  5187.2  364.25  5223.7  365.70
  5246.1  366.97  5281.6  368.43  5302.5  368.86  5317.2  369.65  5352.1  369.96
#Mann=3,-1,0
  4673.8     0.1       0  4978.4    0.07       0  4984.4     0.1       0
Bank Sta=4978.4,4984.4
Exp/Cntr=0.3,0.1

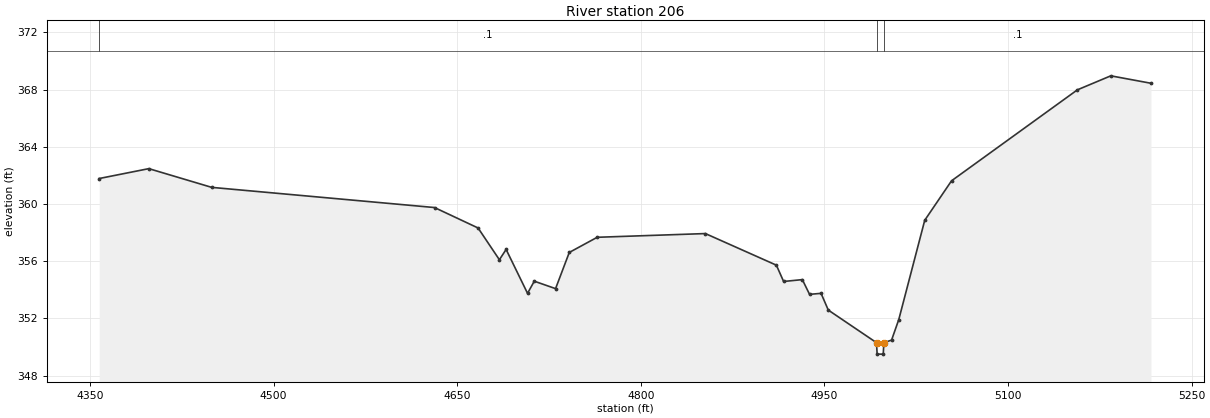
Type RM Length L Ch R = 1,206,0,0,0
BEGIN DESCRIPTION:
UNT 085 in RCW 1.0
END DESCRIPTION:
XS GIS Cut Line= 3
      2054481.64     13438073.71      2054682.18     13437638.78
      2054479.19     13437317.23
#Sta/Elev= 30
  4357.5  361.78  4398.0  362.47  4449.4  361.16  4631.4  359.75  4667.0  358.32
  4684.4  356.10  4689.9  356.82  4707.4  353.75  4712.9  354.60  4730.3  354.08
  4741.5  356.61  4764.3  357.67  4852.7  357.93  4910.7  355.72  4916.6  354.58
  4931.9  354.71  4937.8  353.68  4947.2  353.75  4953.1  352.58  4992.5  350.30
  4993.0  349.50  4998.0  349.50  4998.5  350.30  5004.8  350.48  5010.7  351.92
  5031.9  358.86  5053.8  361.62  5156.6  367.98  5183.9  368.96  5216.7  368.44
#Mann=3,-1,0
  4357.5     0.1       0  4992.5    0.07       0  4998.5     0.1       0
Bank Sta=4992.5,4998.5
Exp/Cntr=0.3,0.1

Chan Stop Cuts=-1