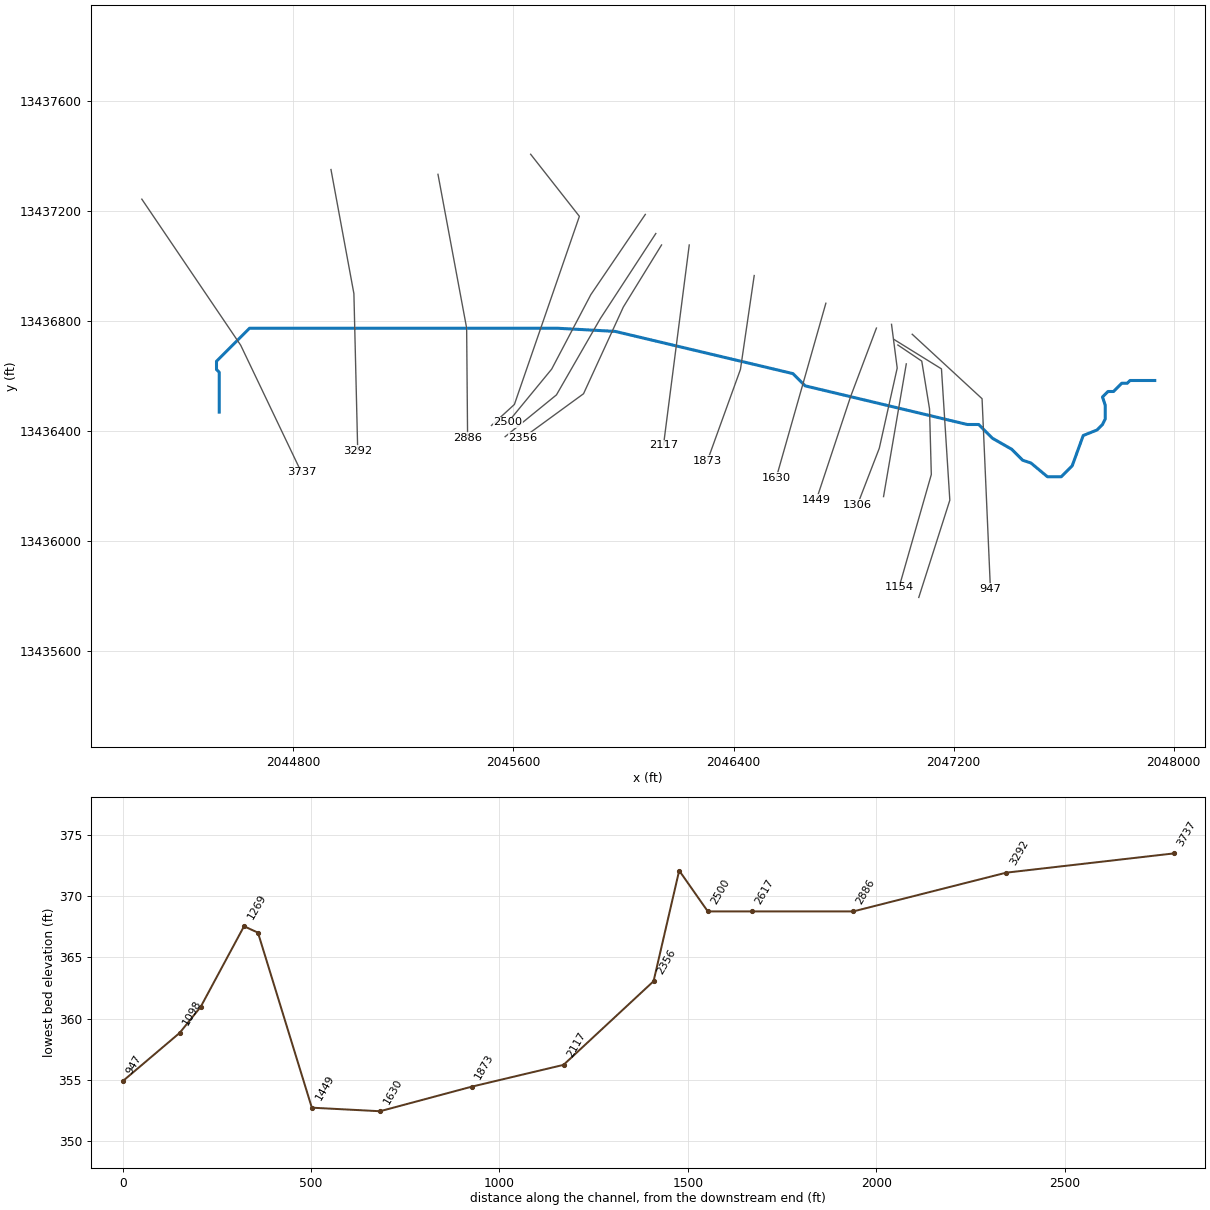
--- UNT 086 in RCW.prj (project) ---

Proj Title=UNT 086 in RCW Base Level Engineering
Current Plan=p01
Default Exp/Contr=0.3,0.1
English Units
Geom File=g01
Flow File=f01
Plan File=p01
BEGIN DESCRIPTION:
UNT 086 in RCW
END DESCRIPTION:

--- UNT 086 in RCW.p01 (plan) ---

Plan Title=Multiple Run
Short Identifier=Multiple
Geom File=g01
Flow File=f01
Subcritical Flow
K Sum by GR= 0
Std Step Tol= 0.01
Critical Tol= 0.01
Num of Std Step Trials= 20
Max Error Tol= 0.3
Flow Tol Ratio= 0.001
Split Flow NTrial= 30
Split Flow Tol= 0.02
Split Flow Ratio= 0.02
Log Output Level= 0
Friction Slope Method= 1
Unsteady Friction Slope Method= 2
Unsteady Bridges Friction Slope Method= 1
Parabolic Critical Depth
Global Vel Dist=  1 , 1 , 1
Global Log Level= 0
CheckData=True
Encroach Param= -1, 0, 0, 0
BEGIN DESCRIPTION:
Multiple Run
END DESCRIPTION:

--- UNT 086 in RCW.f01 (steady flow) ---

Flow Title=Multiple
Number of Profiles=7
Profile Names=10-year,25-year,50-year,1pct_min,100-year,1pct_plu,500-year
River Rch & RM= UNT 086 in RCW,Reach-1,3737
     134     180     218     132     263     524     387
Boundary for River Rch & Prof#=UNT 086 in RCW,Reach-1,1
Up Type=0
Dn Type=3
Dn Slope=0.005
Boundary for River Rch & Prof#=UNT 086 in RCW,Reach-1,2
Up Type=0
Dn Type=3
Dn Slope=0.005
Boundary for River Rch & Prof#=UNT 086 in RCW,Reach-1,3
Up Type=0
Dn Type=3
Dn Slope=0.005
Boundary for River Rch & Prof#=UNT 086 in RCW,Reach-1,4
Up Type=0
Dn Type=3
Dn Slope=0.005
Boundary for River Rch & Prof#=UNT 086 in RCW,Reach-1,5
Up Type=0
Dn Type=3
Dn Slope=0.005
Boundary for River Rch & Prof#=UNT 086 in RCW,Reach-1,6
Up Type=0
Dn Type=3
Dn Slope=0.005
Boundary for River Rch & Prof#=UNT 086 in RCW,Reach-1,7
Up Type=0
Dn Type=3
Dn Slope=0.005

--- UNT 086 in RCW.g01 (geometry) ---

Geom Title=Existing Conditions

River Reach=UNT 086 in RCW,Reach-1
Reach XY= 30
      2044530.80     13436469.54      2044530.80     13436614.54
      2044520.80     13436624.54      2044520.80     13436654.54
      2044640.80     13436774.54      2045760.80     13436774.54
      2045969.88     13436763.06      2046615.80     13436609.54
      2046660.30     13436565.03      2047249.39     13436424.54
      2047290.80     13436424.54      2047340.80     13436374.54
      2047410.80     13436334.54      2047450.80     13436294.54
      2047480.80     13436284.54      2047540.80     13436234.54
      2047590.80     13436234.54      2047630.80     13436274.54
      2047670.80     13436384.54      2047720.80     13436404.54
      2047740.80     13436424.54      2047750.80     13436444.54
      2047750.80     13436494.54      2047740.80     13436524.54
      2047760.80     13436544.54      2047780.80     13436544.54
      2047810.80     13436574.54      2047830.80     13436574.54
      2047840.80     13436584.54      2047930.80     13436584.54

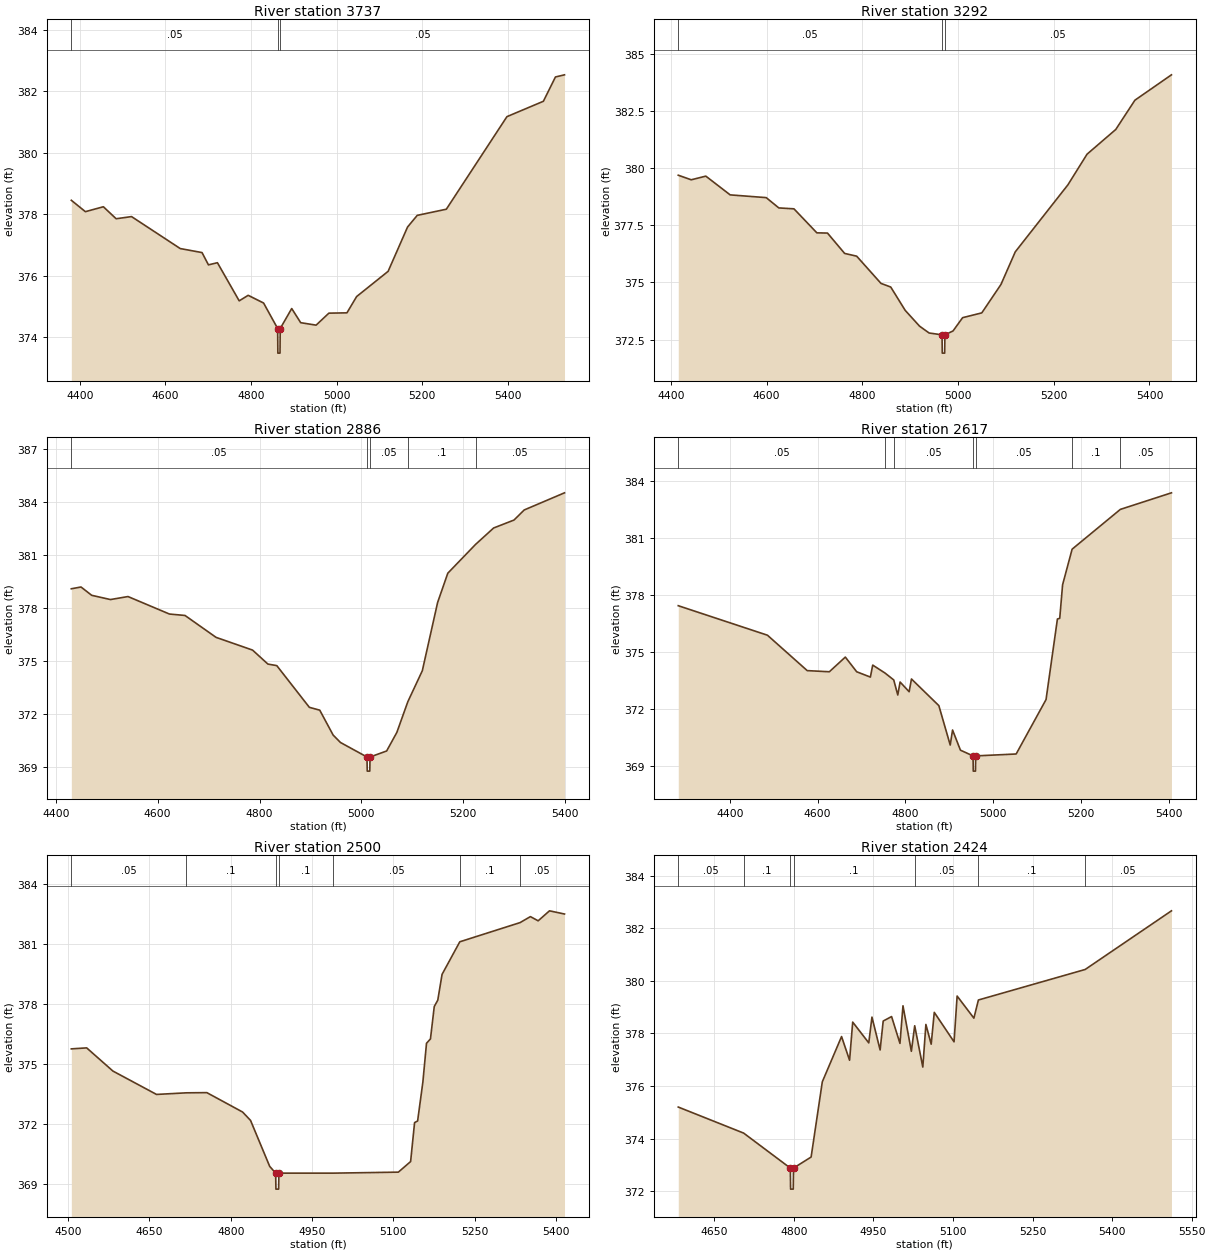
Type RM Length L Ch R = 1,3737,445,445,445
BEGIN DESCRIPTION:
UNT 086 in RCW 8.0
END DESCRIPTION:
XS GIS Cut Line= 3
      2044249.33     13437243.99      2044608.70     13436712.75
      2044829.17     13436250.96
#Sta/Elev= 30
  4380.0  378.45  4412.9  378.08  4454.9  378.24  4484.8  377.85  4520.8  377.92
  4634.7  376.88  4685.6  376.75  4700.6  376.35  4721.6  376.42  4772.5  375.18
  4793.5  375.36  4829.5  375.11  4862.4  374.28  4862.9  373.48  4867.9  373.48
  4868.4  374.28  4895.3  374.93  4916.3  374.47  4952.3  374.39  4982.2  374.78
  5024.4  374.79  5047.1  375.32  5120.7  376.14  5166.1  377.58  5188.8  377.96
  5256.8  378.16  5398.5  381.17  5483.7  381.67  5511.9  382.46  5533.1  382.53
#Mann=3,-1,0
  4380.0    0.05       0  4862.4    0.03       0  4868.4    0.05       0
Bank Sta=4862.4,4868.4
Exp/Cntr=0.3,0.1

Type RM Length L Ch R = 1,3292,406,406,406
BEGIN DESCRIPTION:
UNT 086 in RCW 7.0
END DESCRIPTION:
XS GIS Cut Line= 3
      2044936.82     13437351.67      2045020.16     13436900.25
      2045034.01     13436328.67
#Sta/Elev= 30
  4415.2  379.69  4442.3  379.49  4472.8  379.65  4523.7  378.83  4599.0  378.71
  4625.4  378.26  4657.0  378.22  4704.9  377.17  4727.1  377.16  4762.9  376.27
  4788.1  376.15  4838.9  374.96  4859.3  374.80  4889.5  373.78  4919.5  373.09
  4939.5  372.79  4966.5  372.71  4967.0  371.91  4972.0  371.91  4972.5  372.71
  4989.5  372.88  5009.5  373.46  5049.6  373.67  5089.6  374.91  5119.6  376.34
  5229.6  379.27  5269.6  380.61  5329.6  381.69  5369.6  382.97  5446.0  384.08
#Mann=3,-1,0
  4415.2    0.05       0  4966.5    0.03       0  4972.5    0.05       0
Bank Sta=4966.5,4972.5
Exp/Cntr=0.3,0.1

Type RM Length L Ch R = 1,2886,269,269,269
BEGIN DESCRIPTION:
UNT 086 in RCW 6.0
END DESCRIPTION:
XS GIS Cut Line= 3
      2045325.70     13437334.31      2045429.88     13436775.25
      2045433.35     13436375.95
#Sta/Elev= 30
  4430.6  379.07  4449.6  379.17  4470.6  378.70  4507.4  378.46  4541.8  378.63
  4623.2  377.64  4653.7  377.56  4714.7  376.32  4786.3  375.60  4816.4  374.81
  4833.9  374.72  4897.8  372.36  4918.2  372.20  4944.5  370.79  4958.9  370.37
  5010.9  369.55  5011.4  368.75  5016.4  368.75  5016.9  369.55  5049.5  369.89
  5069.5  370.94  5091.1  372.68  5119.5  374.43  5149.5  378.29  5169.5  379.95
  5224.0  381.58  5259.5  382.51  5299.5  382.96  5319.5  383.53  5398.6  384.50
#Mann=5,-1,0
  4430.6    0.05       0  5010.9   0.033       0  5016.9    0.05       0
  5091.1     0.1       0  5224.0    0.05       0
Bank Sta=5010.9,5016.9
Exp/Cntr=0.3,0.1

Type RM Length L Ch R = 1,2617,117,117,117
BEGIN DESCRIPTION:
Mapping XS f0169209
END DESCRIPTION:
XS GIS Cut Line= 4
      2045662.51     13437407.20      2045839.60     13437181.50
      2045603.49     13436497.47      2045520.13     13436421.05
#Sta/Elev= 30
  4282.6  377.44  4485.8  375.89  4576.4  374.03  4626.8  373.97  4663.2  374.74
  4689.1  373.97  4720.3  373.69  4725.6  374.32  4753.8  373.90  4773.5  373.54
  4782.7  372.75  4788.0  373.43  4808.6  372.92  4813.9  373.59  4876.3  372.19
  4902.2  370.12  4907.5  370.91  4925.5  369.85  4954.2  369.55  4954.7  368.75
  4959.7  368.75  4960.2  369.55  5052.4  369.65  5120.5  372.51  5146.4  376.74
  5151.7  376.78  5158.2  378.54  5179.9  380.41  5289.8  382.50  5406.2  383.37
#Mann=7,-1,0
  4282.6    0.05       0  4753.8     0.1       0  4773.5    0.05       0
  4954.2   0.033       0  4960.2    0.05       0  5179.9     0.1       0
  5289.8    0.05       0
Bank Sta=4954.2,4960.2
Exp/Cntr=0.3,0.1

Type RM Length L Ch R = 1,2500,76,76,76
BEGIN DESCRIPTION:
Mapping XS 7b05170f
END DESCRIPTION:
XS GIS Cut Line= 4
      2046079.21     13437188.47      2045881.27     13436896.77
      2045738.91     13436625.94      2045579.58     13436431.98
#Sta/Elev= 30
  4506.0  375.77  4534.3  375.82  4582.7  374.66  4663.1  373.49  4718.2  373.57
  4755.9  373.58  4821.8  372.61  4836.5  372.19  4871.8  369.89  4882.8  369.55
  4883.3  368.75  4888.3  368.75  4888.8  369.55  4988.7  369.55  5109.1  369.60
  5131.7  370.13  5139.0  372.08  5144.6  372.16  5154.3  374.11  5161.0  376.05
  5168.3  376.27  5175.3  377.89  5181.8  378.21  5189.7  379.50  5222.4  381.13
  5333.5  382.09  5352.6  382.39  5366.9  382.18  5387.8  382.68  5415.5  382.52
#Mann=7,-1,0
  4506.0    0.05       0  4718.2     0.1       0  4882.8   0.033       0
  4888.8     0.1       0  4988.7    0.05       0  5222.4     0.1       0
  5333.5    0.05       0
Bank Sta=4882.8,4888.8
Exp/Cntr=0.3,0.1

Type RM Length L Ch R = 1,2424,68,68,68
BEGIN DESCRIPTION:
Mapping XS 59560242
END DESCRIPTION:
XS GIS Cut Line= 4
      2046117.38     13437119.00      2045915.99     13436809.97
      2045756.27     13436532.19      2045569.73     13436380.20
#Sta/Elev= 30
  4582.0  375.20  4705.3  374.21  4793.3  372.88  4793.8  372.08  4798.8  372.08
  4799.3  372.88  4832.5  373.30  4853.6  376.16  4889.9  377.88  4905.0  376.98
  4910.9  378.43  4941.2  377.64  4947.2  378.62  4962.6  377.37  4968.4  378.47
  4984.2  378.64  5000.0  377.62  5005.7  379.05  5021.5  377.32  5027.8  378.29
  5043.1  376.72  5048.9  378.34  5058.9  377.59  5064.7  378.80  5102.0  377.68
  5107.8  379.42  5139.4  378.58  5147.9  379.27  5349.2  380.43  5511.9  382.66
#Mann=7,-1,0
  4582.0    0.05       0  4705.3     0.1       0  4793.3    0.07       0
  4799.3     0.1       0  5027.8    0.05       0  5147.9     0.1       0
  5349.2    0.05       0
Bank Sta=4793.3,4799.3
Exp/Cntr=0.3,0.1

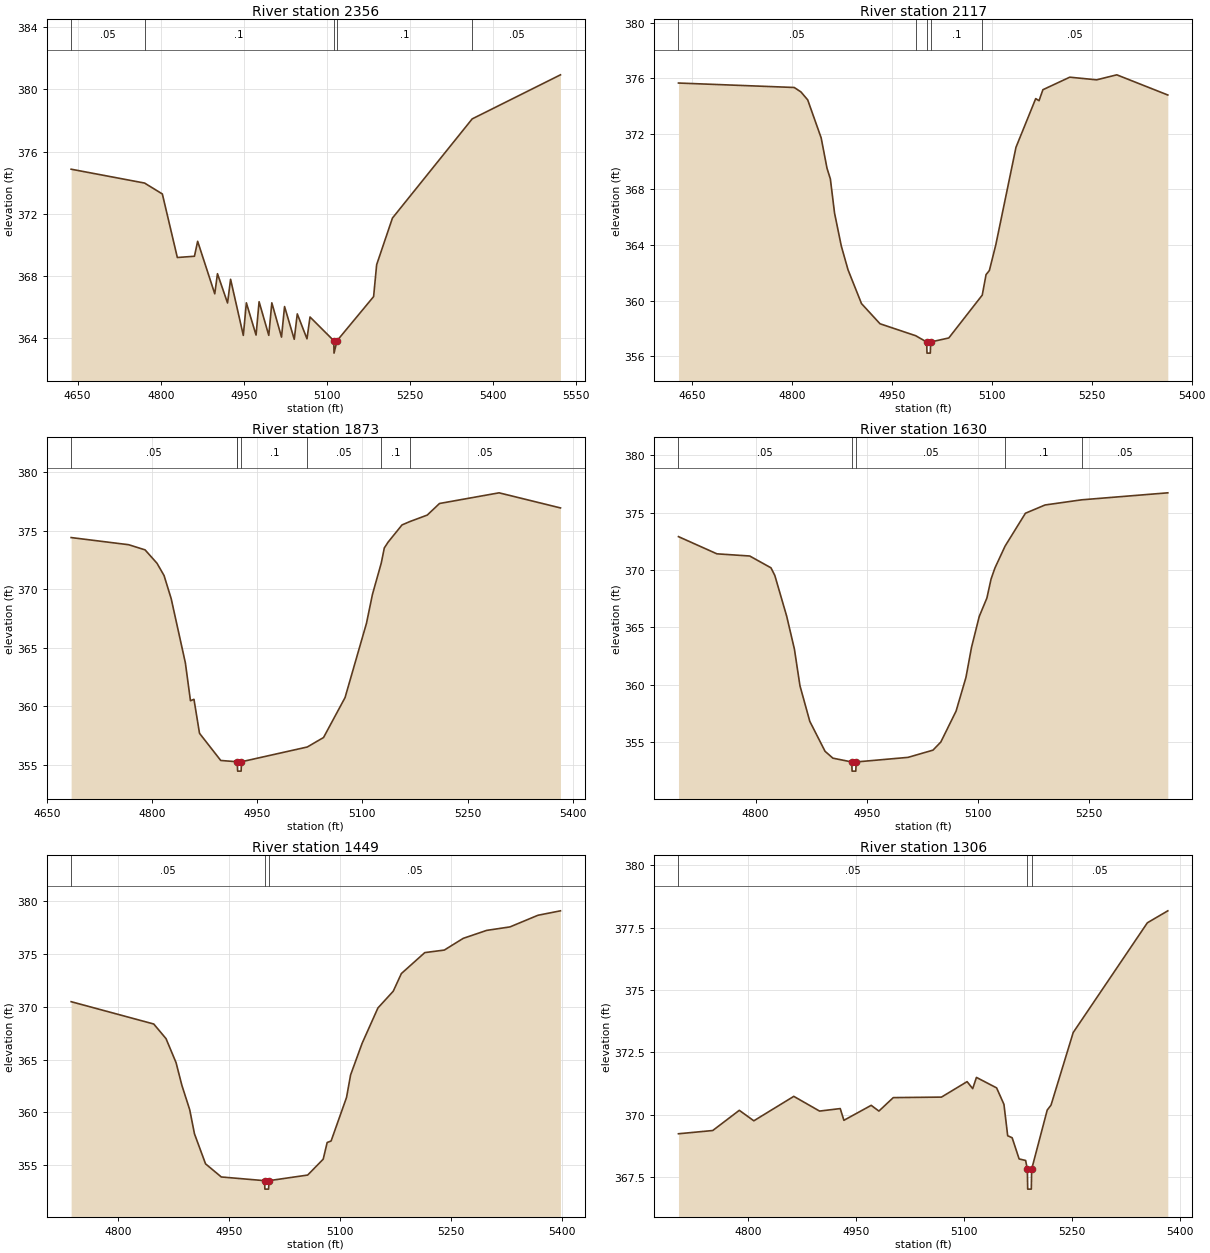
Type RM Length L Ch R = 1,2356,239,239,239
BEGIN DESCRIPTION:
UNT 086 in RCW 5.0
END DESCRIPTION:
XS GIS Cut Line= 4
      2046138.22     13437077.34      2045999.32     13436851.63
      2045854.72     13436536.40      2045634.75     13436375.95
#Sta/Elev= 30
  4638.2  374.87  4770.9  373.98  4803.0  373.28  4830.1  369.20  4861.0  369.28
  4866.8  370.24  4897.7  366.87  4902.6  368.16  4920.8  366.28  4926.3  367.80
  4949.3  364.20  4954.8  366.29  4972.3  364.22  4977.8  366.36  4995.3  364.20
  5000.8  366.29  5018.3  364.09  5023.8  366.05  5041.3  363.95  5046.8  365.58
  5064.3  363.98  5069.8  365.38  5112.7  363.86  5113.2  363.06  5118.7  363.86
  5184.7  366.69  5190.2  368.74  5218.7  371.73  5362.8  378.10  5522.3  380.93
#Mann=5,-1,0
  4638.2    0.05       0  4770.9     0.1       0  5112.7    0.07       0
  5118.7     0.1       0  5362.8    0.05       0
Bank Sta=5112.7,5118.7
Exp/Cntr=0.3,0.1

Type RM Length L Ch R = 1,2117,244,244,244
BEGIN DESCRIPTION:
Mapping XS fcf12f0f
END DESCRIPTION:
XS GIS Cut Line= 2
      2046238.90     13437077.31      2046145.28     13436349.11
#Sta/Elev= 30
  4630.0  375.65  4803.7  375.33  4813.8  375.01  4823.9  374.44  4844.1  371.71
  4852.9  369.52  4857.9  368.76  4864.2  366.30  4874.3  363.94  4884.4  362.23
  4904.6  359.80  4932.4  358.35  4986.0  357.49  5002.4  357.04  5002.9  356.24
  5007.9  356.24  5008.4  357.04  5035.6  357.33  5085.8  360.41  5091.5  361.88
  5096.5  362.18  5106.2  364.04  5136.4  371.03  5166.0  374.53  5171.0  374.38
  5176.8  375.17  5217.1  376.07  5257.4  375.88  5287.7  376.24  5364.2  374.79
#Mann=5,-1,0
  4630.0    0.05       0  4986.0     0.1       0  5002.4    0.07       0
  5008.4     0.1       0  5085.8    0.05       0
Bank Sta=5002.4,5008.4
Exp/Cntr=0.3,0.1

Type RM Length L Ch R = 1,1873,243,243,243
BEGIN DESCRIPTION:
UNT 086 in RCW 4.0
END DESCRIPTION:
XS GIS Cut Line= 3
      2046475.02     13436966.24      2046425.00     13436625.00
      2046304.89     13436292.63
#Sta/Elev= 30
  4684.3  374.40  4766.4  373.79  4789.8  373.35  4806.8  372.21  4816.9  371.16
  4827.1  369.18  4847.3  363.71  4854.6  360.47  4859.6  360.59  4867.5  357.69
  4897.8  355.37  4921.1  355.26  4921.4  355.26  4921.9  354.46  4926.9  354.46
  4927.4  355.26  5021.3  356.52  5044.5  357.33  5075.2  360.74  5105.8  367.09
  5114.3  369.55  5126.9  372.23  5131.2  373.51  5136.5  374.00  5156.5  375.48
  5167.4  375.76  5192.5  376.32  5210.0  377.31  5295.0  378.22  5382.6  376.93
#Mann=7,-1,0
  4684.3    0.05       0  4921.1     0.1       0  4921.4    0.07       0
  4927.4     0.1       0  5021.3    0.05       0  5126.9     0.1       0
  5167.4    0.05       0
Bank Sta=4921.4,4927.4
Exp/Cntr=0.3,0.1

Type RM Length L Ch R = 1,1630,181,181,181
BEGIN DESCRIPTION:
Mapping XS 9798b93f
END DESCRIPTION:
XS GIS Cut Line= 2
      2046735.44     13436865.54      2046554.87     13436230.09
#Sta/Elev= 30
  4695.9  372.91  4747.8  371.41  4792.1  371.22  4820.8  370.19  4826.0  369.52
  4842.0  365.97  4852.4  363.11  4859.9  359.91  4873.2  356.80  4893.8  354.19
  4904.4  353.59  4929.8  353.26  4930.3  352.46  4935.3  352.46  4935.8  353.26
  5005.8  353.66  5039.5  354.29  5050.1  355.00  5070.7  357.70  5084.0  360.63
  5091.5  363.25  5101.9  365.94  5112.3  367.56  5117.9  369.21  5123.1  370.17
  5136.8  372.08  5164.3  374.95  5190.8  375.67  5240.2  376.12  5356.5  376.73
#Mann=5,-1,0
  4695.9    0.05       0  4929.8   0.033       0  4935.8    0.05       0
  5136.8     0.1       0  5240.2    0.05       0
Bank Sta=4929.8,4935.8
Exp/Cntr=0.3,0.1

Type RM Length L Ch R = 1,1449,143,143,143
BEGIN DESCRIPTION:
UNT 086 in RCW 3.0
END DESCRIPTION:
XS GIS Cut Line= 3
      2046919.18     13436775.19      2046825.00     13436525.00
      2046700.70     13436150.21
#Sta/Elev= 30
  4736.2  370.47  4848.0  368.36  4864.6  366.98  4878.2  364.71  4886.0  362.58
  4896.7  360.25  4903.1  357.98  4918.1  355.14  4939.4  353.90  4997.9  353.55
  4998.4  352.75  5003.4  352.75  5003.9  353.55  5056.3  354.08  5077.3  355.58
  5082.7  357.16  5088.0  357.30  5108.9  361.42  5114.4  363.55  5130.0  366.54
  5151.4  369.88  5172.1  371.46  5183.1  373.13  5214.8  375.11  5241.2  375.35
  5266.9  376.46  5298.5  377.21  5330.1  377.54  5367.9  378.64  5398.4  379.06
#Mann=3,-1,0
  4736.2    0.05       0  4997.9   0.033       0  5003.9    0.05       0
Bank Sta=4997.9,5003.9
Exp/Cntr=0.3,0.1

Type RM Length L Ch R = 1,1306,37,37,37
BEGIN DESCRIPTION:
Mapping XS 65f478e5
END DESCRIPTION:
XS GIS Cut Line= 4
      2046974.07     13436788.78      2046994.71     13436629.82
      2046929.61     13436338.15      2046850.17     13436132.40
#Sta/Elev= 30
  4702.9  369.24  4750.5  369.37  4787.4  370.18  4807.6  369.76  4863.1  370.74
  4898.9  370.15  4927.6  370.25  4932.7  369.78  4970.6  370.38  4981.3  370.15
  5001.3  370.69  5068.2  370.71  5103.8  371.33  5111.6  371.05  5116.8  371.50
  5144.8  371.08  5155.0  370.42  5160.2  369.16  5166.4  369.08  5176.1  368.23
  5185.1  368.17  5187.5  367.82  5188.0  367.02  5193.0  367.02  5193.5  367.82
  5215.1  370.19  5220.4  370.39  5251.2  373.30  5354.2  377.70  5382.6  378.18
#Mann=3,-1,0
  4702.9    0.05       0  5187.5    0.03       0  5193.5    0.05       0
Bank Sta=5187.5,5193.5
Exp/Cntr=0.3,0.1

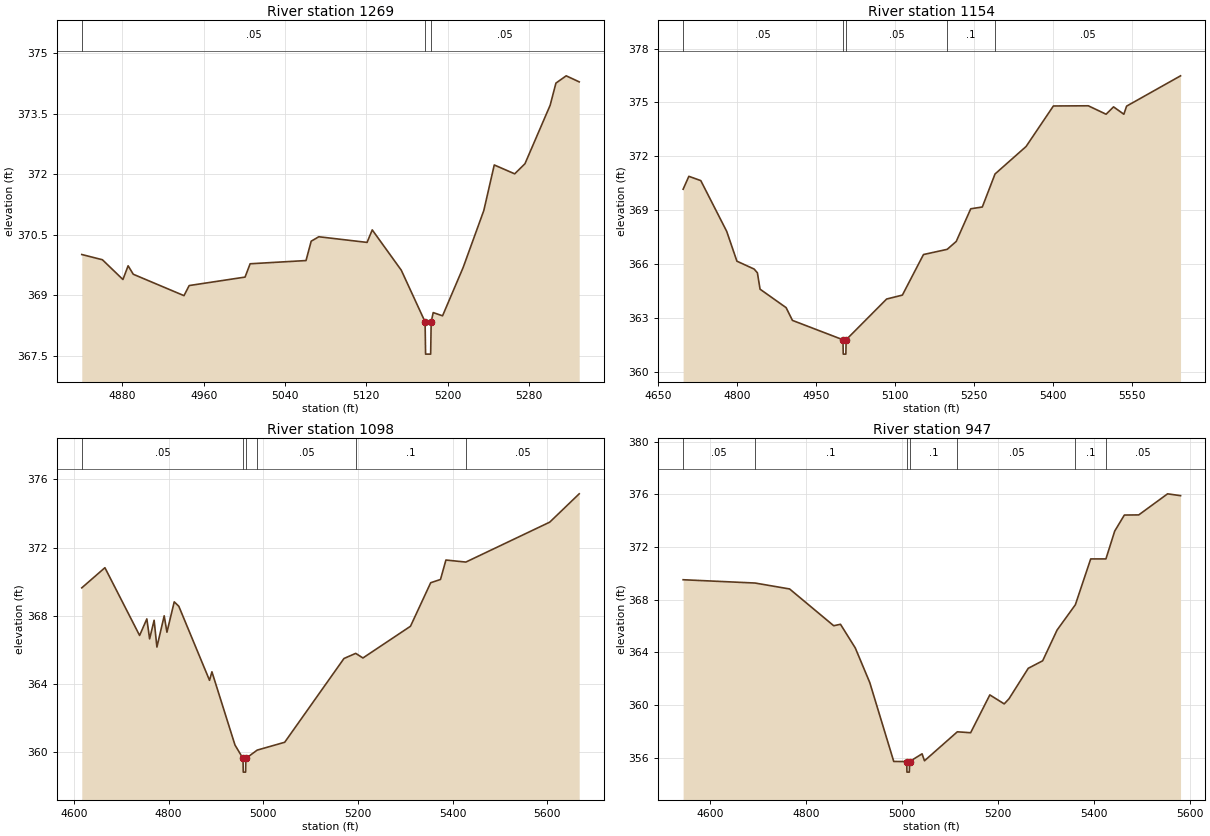
Type RM Length L Ch R = 1,1269,115,115,115
BEGIN DESCRIPTION:
Mapping XS b60be0a9
END DESCRIPTION:
XS GIS Cut Line= 2
      2047027.70     13436644.98      2046945.07     13436162.40
#Sta/Elev= 30
  4840.0  370.01  4860.3  369.88  4880.5  369.39  4885.6  369.73  4890.7  369.52
  4940.6  368.99  4945.7  369.24  5000.7  369.45  5005.7  369.78  5060.7  369.86
  5065.8  370.34  5073.3  370.45  5120.8  370.31  5125.9  370.62  5154.5  369.62
  5177.9  368.34  5178.4  367.54  5183.4  367.54  5183.9  368.34  5185.9  368.57
  5195.1  368.49  5215.4  369.69  5235.7  371.10  5246.0  372.23  5266.1  372.01
  5276.2  372.26  5301.0  373.71  5306.7  374.26  5316.8  374.44  5329.6  374.29
#Mann=3,-1,0
  4840.0    0.05       0  5177.9    0.03       0  5183.9    0.05       0
Bank Sta=5177.9,5183.9
Exp/Cntr=0.3,0.1

Type RM Length L Ch R = 1,1154,56,56,56
BEGIN DESCRIPTION:
Mapping XS f9e6a8d0
END DESCRIPTION:
XS GIS Cut Line= 5
      2046997.18     13436713.59      2047083.96     13436655.02
      2047112.17     13436481.41      2047118.68     13436242.69
      2047001.48     13435832.50
#Sta/Elev= 30
  4697.0  370.16  4707.9  370.88  4730.6  370.64  4779.9  367.81  4799.3  366.15
  4832.1  365.71  4838.3  365.50  4843.3  364.59  4892.9  363.56  4904.9  362.85
  5001.0  361.77  5001.5  360.97  5006.5  360.97  5007.0  361.77  5084.0  364.04
  5114.0  364.26  5154.1  366.52  5199.2  366.81  5216.4  367.25  5244.0  369.07
  5266.0  369.17  5290.2  371.01  5349.2  372.54  5401.2  374.80  5467.6  374.81
  5501.4  374.34  5515.6  374.75  5535.2  374.34  5540.4  374.79  5643.0  376.48
#Mann=5,-1,0
  4697.0    0.05       0  5001.0    0.04       0  5007.0    0.05       0
  5199.2     0.1       0  5290.2    0.05       0
Bank Sta=5001,5007
Exp/Cntr=0.3,0.1

Type RM Length L Ch R = 1,1098,151,151,151
BEGIN DESCRIPTION:
UNT 086 in RCW 2.0
END DESCRIPTION:
XS GIS Cut Line= 4
      2046984.15     13436733.13      2047155.57     13436626.81
      2047185.96     13436149.38      2047073.11     13435795.65
#Sta/Elev= 30
  4616.4  369.64  4665.3  370.82  4738.6  366.85  4753.9  367.82  4759.8  366.65
  4769.3  367.74  4775.2  366.17  4790.6  368.00  4796.4  367.04  4811.8  368.82
  4821.5  368.56  4886.4  364.22  4891.5  364.72  4940.2  360.43  4957.2  359.64
  4957.7  358.84  4962.7  358.84  4963.2  359.64  4987.1  360.13  5045.3  360.59
  5170.6  365.50  5195.4  365.80  5210.7  365.53  5311.2  367.39  5353.9  369.94
  5374.6  370.13  5386.1  371.27  5428.2  371.15  5605.5  373.49  5667.8  375.15
#Mann=6,-1,0
  4616.4    0.05       0  4957.2    0.03       0  4963.2    0.05       0
  4987.1    0.05       0  5195.4     0.1       0  5428.2    0.05       0
Bank Sta=4957.2,4963.2
Exp/Cntr=0.3,0.1

Type RM Length L Ch R = 1,947,0,0,0
BEGIN DESCRIPTION:
UNT 086 in RCW 1.0
END DESCRIPTION:
XS GIS Cut Line= 3
      2047049.26     13436752.66      2047303.14     13436518.30
      2047333.44     13435827.98
#Sta/Elev= 30
  4543.4  369.51  4693.4  369.26  4765.3  368.81  4857.2  366.02  4871.3  366.13
  4902.2  364.33  4932.3  361.71  4982.3  355.72  5009.3  355.71  5009.8  354.91
  5014.8  354.91  5015.3  355.71  5041.3  356.30  5046.3  355.77  5114.8  357.97
  5142.5  357.90  5182.5  360.77  5212.5  360.09  5222.5  360.48  5262.6  362.79
  5292.6  363.36  5322.6  365.69  5360.7  367.61  5392.7  371.09  5424.4  371.09
  5442.7  373.20  5462.8  374.42  5492.8  374.43  5552.9  376.03  5579.9  375.89
#Mann=7,-1,0
  4543.4    0.05       0  4693.4     0.1       0  5009.3    0.07       0
  5015.3     0.1       0  5114.8    0.05       0  5360.7     0.1       0
  5424.4    0.05       0
Bank Sta=5009.3,5015.3
Exp/Cntr=0.3,0.1

Chan Stop Cuts=-1