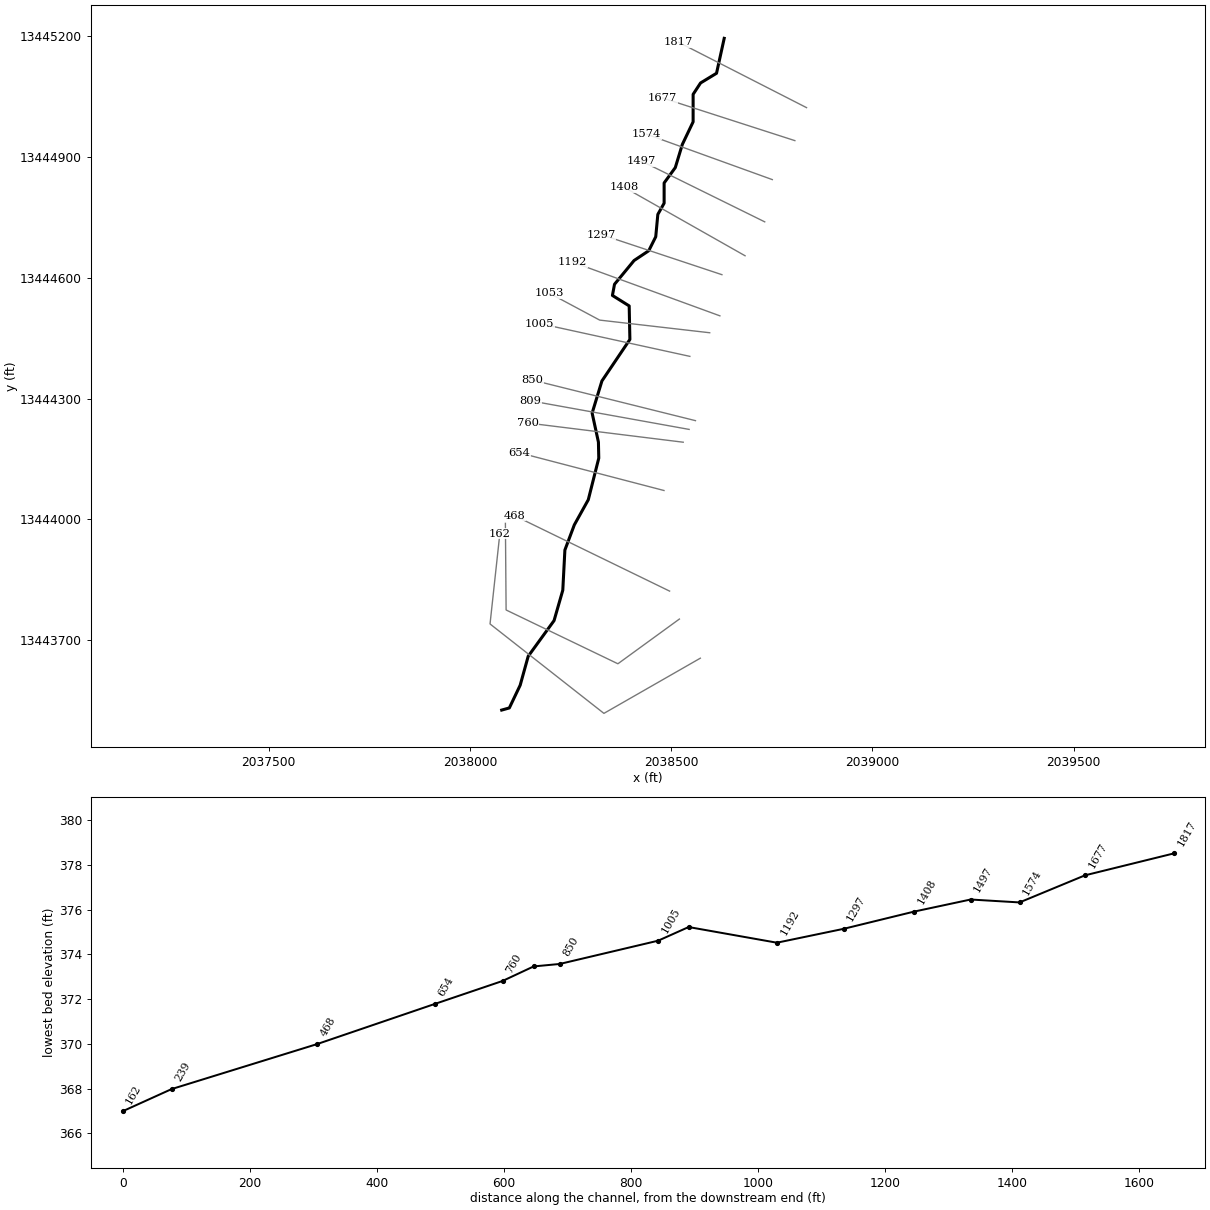
--- UNT 087 in RCW.prj (project) ---

Proj Title=UNT 087 in RCW Base Level Engineering
Current Plan=p01
Default Exp/Contr=0.3,0.1
English Units
Geom File=g01
Flow File=f01
Plan File=p01
BEGIN DESCRIPTION:
UNT 087 in RCW
END DESCRIPTION:

--- UNT 087 in RCW.p01 (plan) ---

Plan Title=Multiple Run
Short Identifier=Multiple
Geom File=g01
Flow File=f01
Subcritical Flow
K Sum by GR= 0
Std Step Tol= 0.01
Critical Tol= 0.01
Num of Std Step Trials= 20
Max Error Tol= 0.3
Flow Tol Ratio= 0.001
Split Flow NTrial= 30
Split Flow Tol= 0.02
Split Flow Ratio= 0.02
Log Output Level= 0
Friction Slope Method= 1
Unsteady Friction Slope Method= 2
Unsteady Bridges Friction Slope Method= 1
Parabolic Critical Depth
Global Vel Dist=  1 , 1 , 1
Global Log Level= 0
CheckData=True
Encroach Param= -1, 0, 0, 0
BEGIN DESCRIPTION:
Multiple Run
END DESCRIPTION:

--- UNT 087 in RCW.f01 (steady flow) ---

Flow Title=Multiple
Number of Profiles=7
Profile Names=10-year,25-year,50-year,1pct_min,100-year,1pct_plu,500-year
River Rch & RM= UNT 087 in RCW,Reach-1,1817
      14      15      17       9      18      36      21
Boundary for River Rch & Prof#=UNT 087 in RCW,Reach-1,1
Up Type=0
Dn Type=3
Dn Slope=0.005
Boundary for River Rch & Prof#=UNT 087 in RCW,Reach-1,2
Up Type=0
Dn Type=3
Dn Slope=0.005
Boundary for River Rch & Prof#=UNT 087 in RCW,Reach-1,3
Up Type=0
Dn Type=3
Dn Slope=0.005
Boundary for River Rch & Prof#=UNT 087 in RCW,Reach-1,4
Up Type=0
Dn Type=3
Dn Slope=0.005
Boundary for River Rch & Prof#=UNT 087 in RCW,Reach-1,5
Up Type=0
Dn Type=3
Dn Slope=0.005
Boundary for River Rch & Prof#=UNT 087 in RCW,Reach-1,6
Up Type=0
Dn Type=3
Dn Slope=0.005
Boundary for River Rch & Prof#=UNT 087 in RCW,Reach-1,7
Up Type=0
Dn Type=3
Dn Slope=0.005

--- UNT 087 in RCW.g01 (geometry) ---

Geom Title=Existing Conditions

River Reach=UNT 087 in RCW,Reach-1
Reach XY= 30
      2038632.00     13445195.35      2038612.91     13445108.54
      2038573.19     13445084.40      2038554.75     13445056.19
      2038554.75     13444987.83      2038527.84     13444931.46
      2038510.47     13444874.17      2038482.70     13444835.97
      2038482.70     13444785.62      2038467.07     13444757.85
      2038461.86     13444702.29      2038444.50     13444667.57
      2038408.04     13444643.26      2038359.43     13444584.23
      2038354.22     13444556.46      2038395.89     13444530.42
      2038397.63     13444447.08      2038328.12     13444343.96
      2038303.82     13444264.10      2038319.44     13444192.05
      2038320.31     13444152.12      2038294.27     13444048.82
      2038259.55     13443986.32      2038236.11     13443923.82
      2038230.90     13443823.99      2038209.20     13443748.47
      2038144.97     13443659.93      2038125.00     13443587.88
      2038098.09     13443531.46      2038079.09     13443526.14

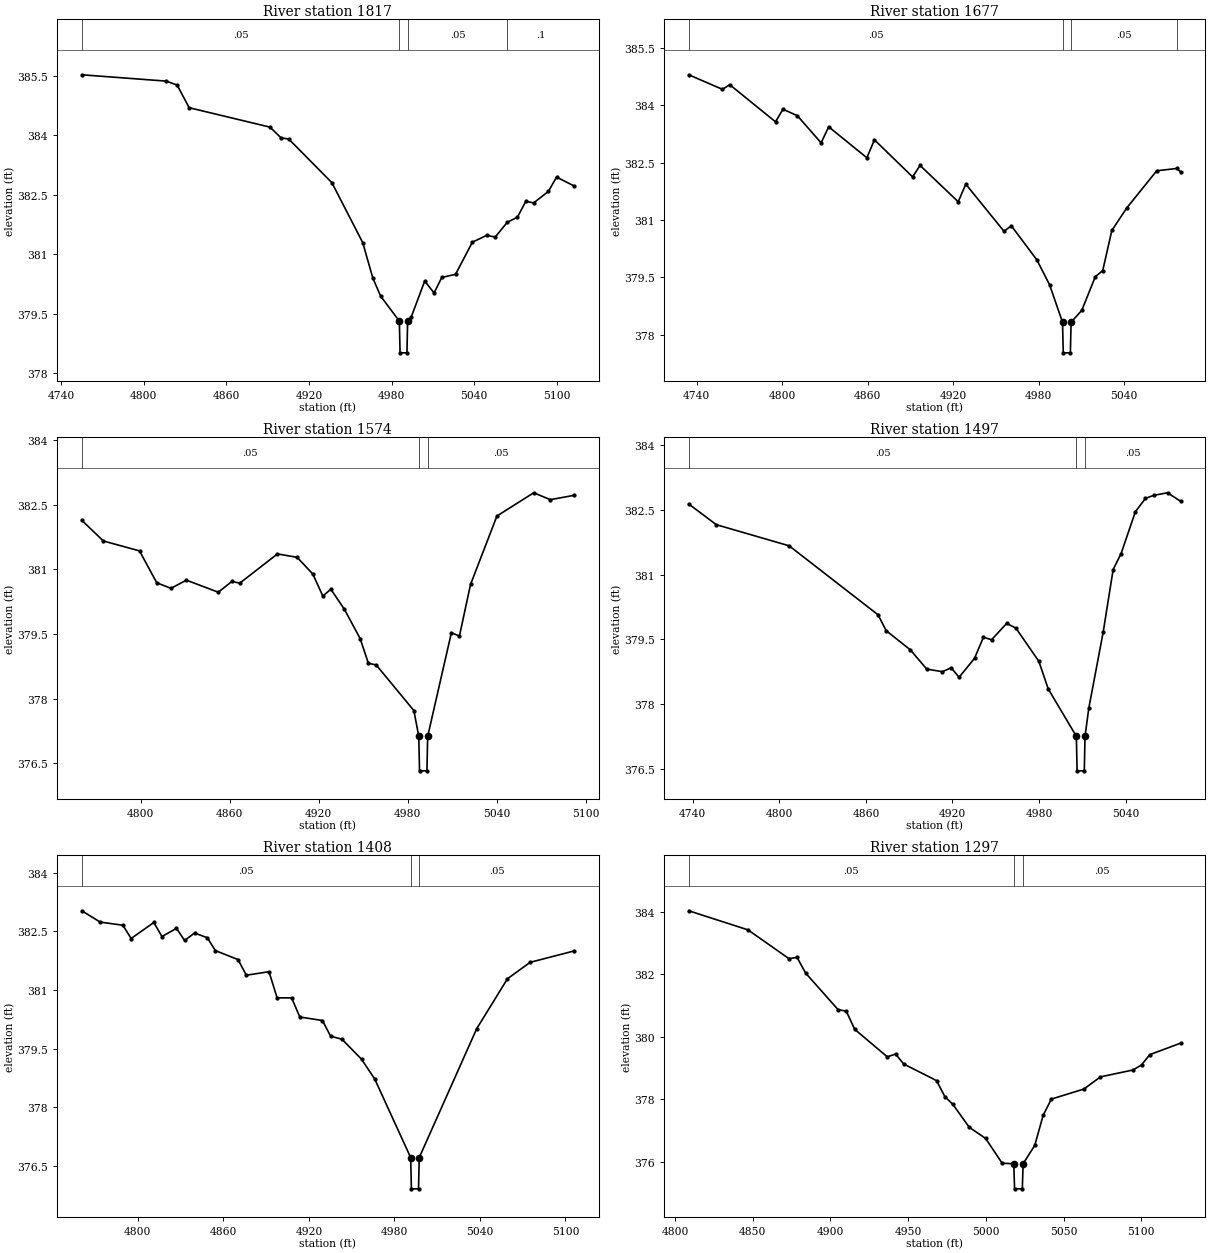
Type RM Length L Ch R = 1,1817,140,140,140
BEGIN DESCRIPTION:
UNT 087 in RCW 8.0
END DESCRIPTION:
XS GIS Cut Line= 2
      2038836.61     13445023.13      2038518.52     13445185.63
#Sta/Elev= 30
  4755.2  385.52  4816.5  385.36  4824.4  385.26  4833.1  384.69  4891.8  384.20
  4899.8  383.93  4905.4  383.90  4936.7  382.80  4959.1  381.29  4966.4  380.40
  4972.1  379.94  4985.7  379.31  4986.2  378.51  4991.2  378.51  4991.7  379.31
  4994.3  379.41  5004.1  380.32  5010.9  380.02  5016.5  380.41  5026.5  380.49
  5038.7  381.30  5049.0  381.47  5055.3  381.43  5064.0  381.80  5071.4  381.93
  5077.5  382.33  5083.2  382.29  5093.9  382.58  5099.8  382.94  5112.4  382.72
#Mann=4,-1,0
  4755.2    0.05       0  4985.7    0.03       0  4991.7    0.05       0
  5064.0     0.1       0
Bank Sta=4985.7,4991.7
Exp/Cntr=0.3,0.1

Type RM Length L Ch R = 1,1677,103,103,103
BEGIN DESCRIPTION:
Mapping XS fec7b289
END DESCRIPTION:
XS GIS Cut Line= 2
      2038807.54     13444941.18      2038478.89     13445047.13
#Sta/Elev= 30
  4734.4  384.80  4758.0  384.42  4763.2  384.54  4795.3  383.57  4800.5  383.90
  4810.6  383.73  4827.3  383.02  4832.6  383.44  4859.4  382.63  4864.7  383.10
  4891.5  382.13  4896.7  382.43  4923.5  381.48  4928.8  381.94  4955.6  380.71
  4960.8  380.85  4978.7  379.96  4987.6  379.31  4996.7  378.33  4997.2  377.53
  5002.2  377.53  5002.7  378.33  5010.2  378.64  5019.7  379.52  5024.9  379.68
  5031.3  380.73  5041.8  381.32  5062.8  382.29  5076.8  382.35  5079.7  382.26
#Mann=4,-1,0
  4734.4    0.05       0  4996.7    0.03       0  5002.7    0.05       0
  5076.8     0.1       0
Bank Sta=4996.7,5002.7
Exp/Cntr=0.3,0.1

Type RM Length L Ch R = 1,1574,77,77,77
BEGIN DESCRIPTION:
UNT 087 in RCW 28.0
END DESCRIPTION:
XS GIS Cut Line= 2
      2038751.55     13444844.31      2038439.47     13444957.01
#Sta/Elev= 30
  4760.3  382.14  4774.8  381.66  4799.2  381.43  4810.8  380.69  4820.4  380.56
  4830.8  380.75  4852.3  380.47  4861.5  380.72  4866.8  380.68  4892.2  381.36
  4905.5  381.28  4916.1  380.89  4922.8  380.38  4928.2  380.54  4937.4  380.07
  4948.0  379.39  4953.5  378.82  4958.8  378.78  4984.2  377.72  4987.5  377.12
  4988.0  376.32  4993.0  376.32  4993.5  377.12  5009.5  379.53  5014.9  379.45
  5022.4  380.65  5040.2  382.24  5065.0  382.78  5076.2  382.62  5092.1  382.72
#Mann=3,-1,0
  4760.3    0.05       0  4987.5    0.03       0  4993.5    0.05       0
Bank Sta=4987.5,4993.5
Exp/Cntr=0.3,0.1

Type RM Length L Ch R = 1,1497,89,89,89
BEGIN DESCRIPTION:
Mapping XS fdf8f370
END DESCRIPTION:
XS GIS Cut Line= 2
      2038732.66     13444739.37      2038426.71     13444890.18
#Sta/Elev= 30
  4737.2  382.64  4756.3  382.16  4806.8  381.67  4868.4  380.07  4874.1  379.70
  4890.7  379.26  4902.2  378.81  4913.0  378.75  4919.1  378.84  4924.6  378.62
  4935.3  379.06  4941.5  379.55  4947.1  379.49  4957.6  379.87  4964.0  379.76
  4979.9  378.99  4986.4  378.35  5005.9  377.25  5006.4  376.45  5011.4  376.45
  5011.9  377.25  5014.5  377.90  5024.5  379.67  5031.4  381.12  5036.9  381.49
  5046.8  382.46  5053.8  382.77  5059.4  382.84  5069.1  382.90  5078.3  382.70
#Mann=3,-1,0
  4737.2    0.05       0  5005.9    0.03       0  5011.9    0.05       0
Bank Sta=5005.9,5011.9
Exp/Cntr=0.3,0.1

Type RM Length L Ch R = 1,1408,111,111,111
BEGIN DESCRIPTION:
UNT 087 in RCW 7.0
END DESCRIPTION:
XS GIS Cut Line= 2
      2038683.82     13444655.08      2038383.47     13444825.22
#Sta/Elev= 30
  4760.7  383.03  4773.6  382.74  4789.5  382.66  4795.3  382.32  4811.2  382.73
  4816.9  382.37  4827.1  382.58  4832.8  382.27  4839.8  382.46  4848.7  382.34
  4854.4  382.01  4870.3  381.78  4876.1  381.38  4892.0  381.47  4897.7  380.80
  4907.9  380.80  4913.6  380.31  4929.5  380.22  4935.2  379.82  4943.2  379.74
  4956.9  379.23  4966.2  378.72  4991.4  376.71  4991.9  375.91  4996.9  375.91
  4997.4  376.71  5037.7  380.01  5059.3  381.29  5075.2  381.71  5105.9  382.00
#Mann=3,-1,0
  4760.7    0.05       0  4991.4    0.03       0  4997.4    0.05       0
Bank Sta=4991.4,4997.4
Exp/Cntr=0.3,0.1

Type RM Length L Ch R = 1,1297,105,105,105
BEGIN DESCRIPTION:
Mapping XS 7fb05ec7
END DESCRIPTION:
XS GIS Cut Line= 2
      2038626.34     13444608.07      2038325.78     13444707.89
#Sta/Elev= 30
  4808.8  384.03  4846.9  383.42  4873.3  382.50  4878.5  382.54  4884.0  382.04
  4904.9  380.87  4910.2  380.82  4915.6  380.24  4936.6  379.36  4941.9  379.45
  4947.2  379.13  4968.3  378.60  4973.6  378.09  4978.8  377.84  4989.3  377.11
  4999.9  376.75  5010.5  375.96  5018.0  375.94  5018.5  375.14  5023.5  375.14
  5024.0  375.94  5031.5  376.53  5036.9  377.49  5042.2  378.01  5063.1  378.33
  5073.8  378.72  5094.7  378.94  5100.2  379.10  5105.5  379.43  5125.5  379.80
#Mann=3,-1,0
  4808.8    0.05       0  5018.0    0.03       0  5024.0    0.05       0
Bank Sta=5018,5024
Exp/Cntr=0.3,0.1

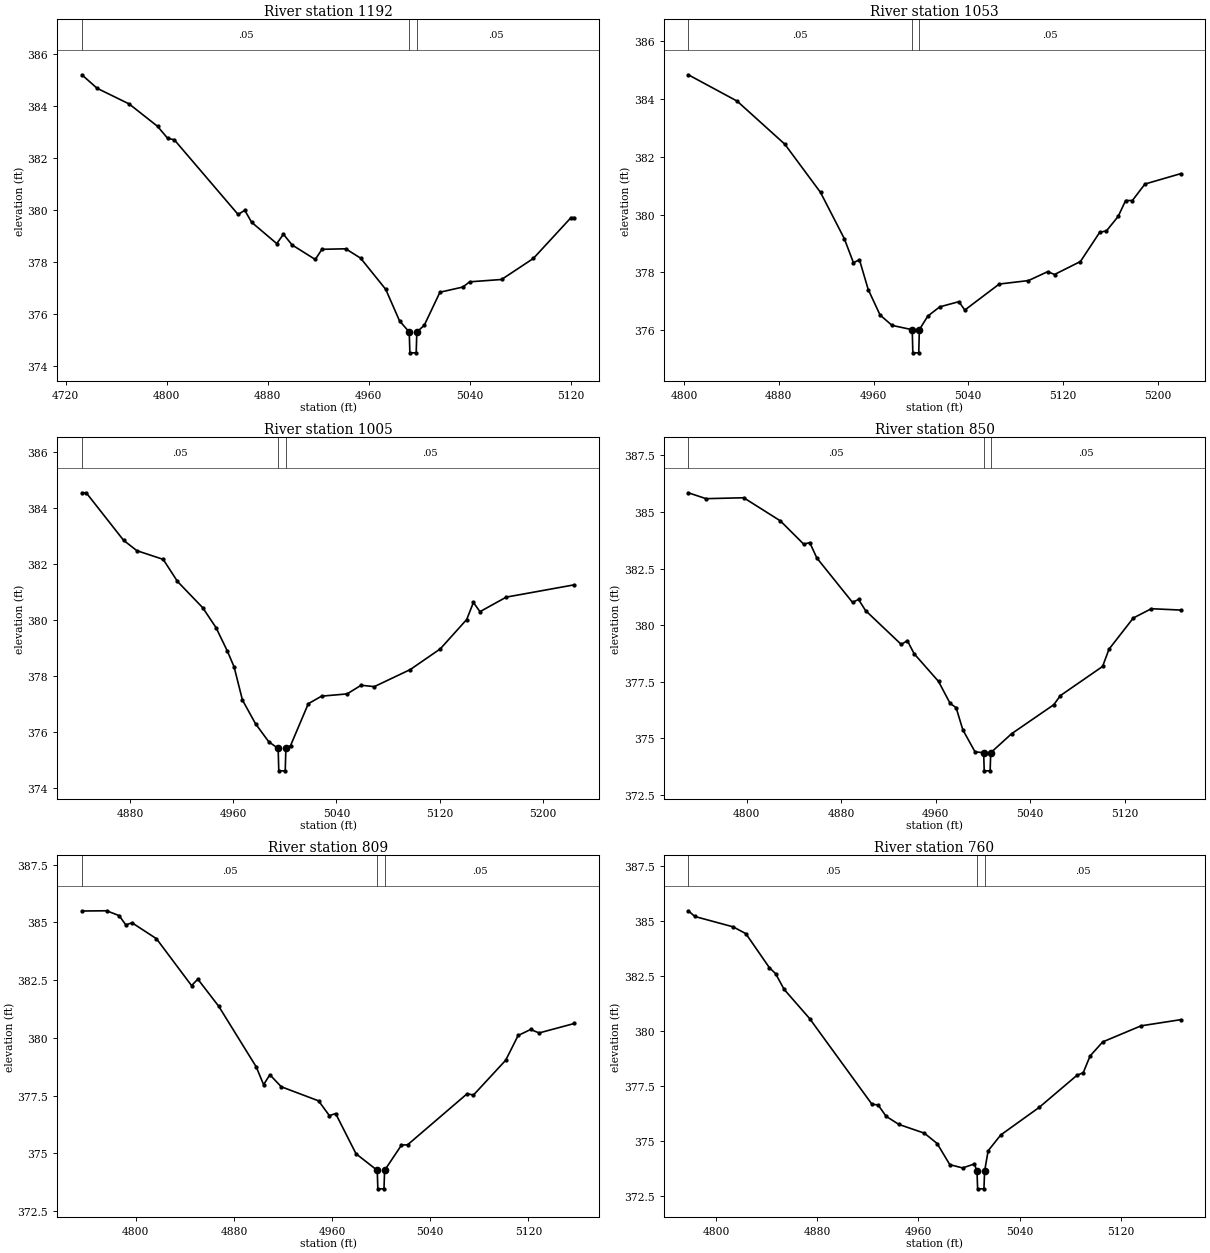
Type RM Length L Ch R = 1,1192,139,139,139
BEGIN DESCRIPTION:
UNT 087 in RCW 6.0
END DESCRIPTION:
XS GIS Cut Line= 2
      2038621.28     13444505.79      2038255.00     13444639.46
#Sta/Elev= 30
  4732.8  385.21  4744.9  384.69  4770.2  384.09  4792.7  383.23  4800.7  382.77
  4806.0  382.71  4856.5  379.84  4861.8  380.00  4867.2  379.54  4887.1  378.72
  4892.4  379.08  4899.2  378.67  4917.6  378.11  4922.9  378.50  4941.7  378.52
  4953.5  378.16  4973.4  376.96  4984.3  375.75  4992.0  375.32  4992.5  374.52
  4997.5  374.52  4998.0  375.32  5003.9  375.58  5016.3  376.85  5034.5  377.05
  5039.8  377.25  5065.1  377.34  5090.3  378.15  5120.1  379.72  5122.7  379.72
#Mann=3,-1,0
  4732.8    0.05       0  4992.0    0.03       0  4998.0    0.05       0
Bank Sta=4992,4998
Exp/Cntr=0.3,0.1

Type RM Length L Ch R = 1,1053,48,48,48
BEGIN DESCRIPTION:
Mapping XS 6aeda9f1
END DESCRIPTION:
XS GIS Cut Line= 3
      2038595.97     13444463.75      2038322.54     13444495.21
      2038198.31     13444561.61
#Sta/Elev= 30
  4803.5  384.84  4844.7  383.93  4885.0  382.44  4915.2  380.77  4935.3  379.17
  4943.0  378.34  4948.1  378.44  4955.5  377.41  4965.5  376.53  4975.6  376.17
  4992.7  376.02  4993.2  375.22  4998.2  375.22  4998.7  376.02  5005.8  376.49
  5015.9  376.81  5032.1  376.99  5037.1  376.70  5066.2  377.60  5090.9  377.72
  5107.2  378.03  5112.9  377.93  5134.8  378.38  5151.1  379.39  5156.8  379.44
  5166.7  379.94  5173.0  380.49  5178.7  380.49  5189.3  381.06  5219.6  381.42
#Mann=3,-1,0
  4803.5    0.05       0  4992.7    0.03       0  4998.7    0.05       0
Bank Sta=4992.7,4998.7
Exp/Cntr=0.3,0.1

Type RM Length L Ch R = 1,1005,155,155,155
BEGIN DESCRIPTION:
UNT 087 in RCW 5.0
END DESCRIPTION:
XS GIS Cut Line= 2
      2038546.68     13444405.08      2038173.39     13444486.69
#Sta/Elev= 30
  4842.5  384.55  4845.9  384.55  4874.9  382.85  4885.2  382.48  4905.6  382.17
  4916.7  381.38  4936.3  380.44  4946.6  379.73  4955.4  378.89  4960.6  378.33
  4967.1  377.14  4977.3  376.29  4987.5  375.65  4994.8  375.41  4995.3  374.61
  5000.3  374.61  5000.8  375.41  5004.4  375.51  5018.2  377.01  5028.5  377.28
  5048.3  377.36  5059.2  377.67  5069.4  377.62  5097.3  378.23  5120.6  378.97
  5141.1  380.02  5146.3  380.63  5151.4  380.30  5171.8  380.82  5224.6  381.26
#Mann=3,-1,0
  4842.5    0.05       0  4994.8    0.03       0  5000.8    0.05       0
Bank Sta=4994.8,5000.8
Exp/Cntr=0.3,0.1

Type RM Length L Ch R = 1,850,41,41,41
BEGIN DESCRIPTION:
UNT 087 in RCW 4.0
END DESCRIPTION:
XS GIS Cut Line= 2
      2038560.55     13444245.36      2038156.00     13444346.07
#Sta/Elev= 30
  4750.6  385.85  4765.6  385.59  4797.5  385.63  4828.5  384.61  4848.3  383.58
  4853.4  383.65  4859.4  382.97  4889.6  381.01  4894.7  381.14  4900.6  380.65
  4930.9  379.15  4936.0  379.32  4941.8  378.74  4962.4  377.52  4972.2  376.55
  4977.3  376.36  4983.0  375.38  4993.3  374.41  5000.6  374.37  5001.1  373.57
  5006.1  373.57  5006.6  374.37  5024.3  375.21  5060.0  376.49  5065.5  376.89
  5101.3  378.18  5106.7  378.94  5127.3  380.32  5142.6  380.73  5167.5  380.67
#Mann=3,-1,0
  4750.6    0.05       0  5000.6    0.03       0  5006.6    0.05       0
Bank Sta=5000.6,5006.6
Exp/Cntr=0.3,0.1

Type RM Length L Ch R = 1,809,49,49,49
BEGIN DESCRIPTION:
Mapping XS 54f8b6c5
END DESCRIPTION:
XS GIS Cut Line= 2
      2038544.88     13444223.57      2038149.94     13444294.75
#Sta/Elev= 30
  4756.1  385.49  4776.3  385.50  4786.5  385.29  4791.9  384.89  4797.0  384.98
  4816.9  384.29  4845.5  382.26  4850.6  382.54  4867.7  381.36  4898.2  378.74
  4904.2  377.97  4909.3  378.40  4918.6  377.88  4949.0  377.27  4957.8  376.63
  4962.9  376.72  4979.5  374.98  4996.8  374.26  4997.3  373.46  5002.3  373.46
  5002.8  374.26  5016.5  375.35  5021.6  375.37  5070.1  377.58  5075.2  377.52
  5101.5  379.03  5111.6  380.10  5121.8  380.36  5128.7  380.21  5157.4  380.62
#Mann=3,-1,0
  4756.1    0.05       0  4996.8    0.03       0  5002.8    0.05       0
Bank Sta=4996.8,5002.8
Exp/Cntr=0.3,0.1

Type RM Length L Ch R = 1,760,106,106,106
BEGIN DESCRIPTION:
Mapping XS ba362e4d
END DESCRIPTION:
XS GIS Cut Line= 2
      2038530.17     13444191.74      2038143.81     13444239.49
#Sta/Elev= 30
  4778.2  385.45  4783.4  385.19  4813.6  384.72  4823.7  384.41  4842.2  382.87
  4847.2  382.59  4853.9  381.88  4874.1  380.55  4923.3  376.66  4928.3  376.62
  4934.5  376.11  4944.6  375.74  4964.8  375.34  4974.9  374.87  4984.9  373.91
  4995.0  373.76  5004.3  373.94  5006.4  373.61  5006.9  372.81  5011.9  372.81
  5012.4  373.61  5015.2  374.54  5025.2  375.26  5055.5  376.51  5085.4  377.97
  5090.4  378.09  5095.8  378.85  5105.8  379.49  5136.1  380.22  5167.5  380.50
#Mann=3,-1,0
  4778.2    0.05       0  5006.4    0.03       0  5012.4    0.05       0
Bank Sta=5006.4,5012.4
Exp/Cntr=0.3,0.1

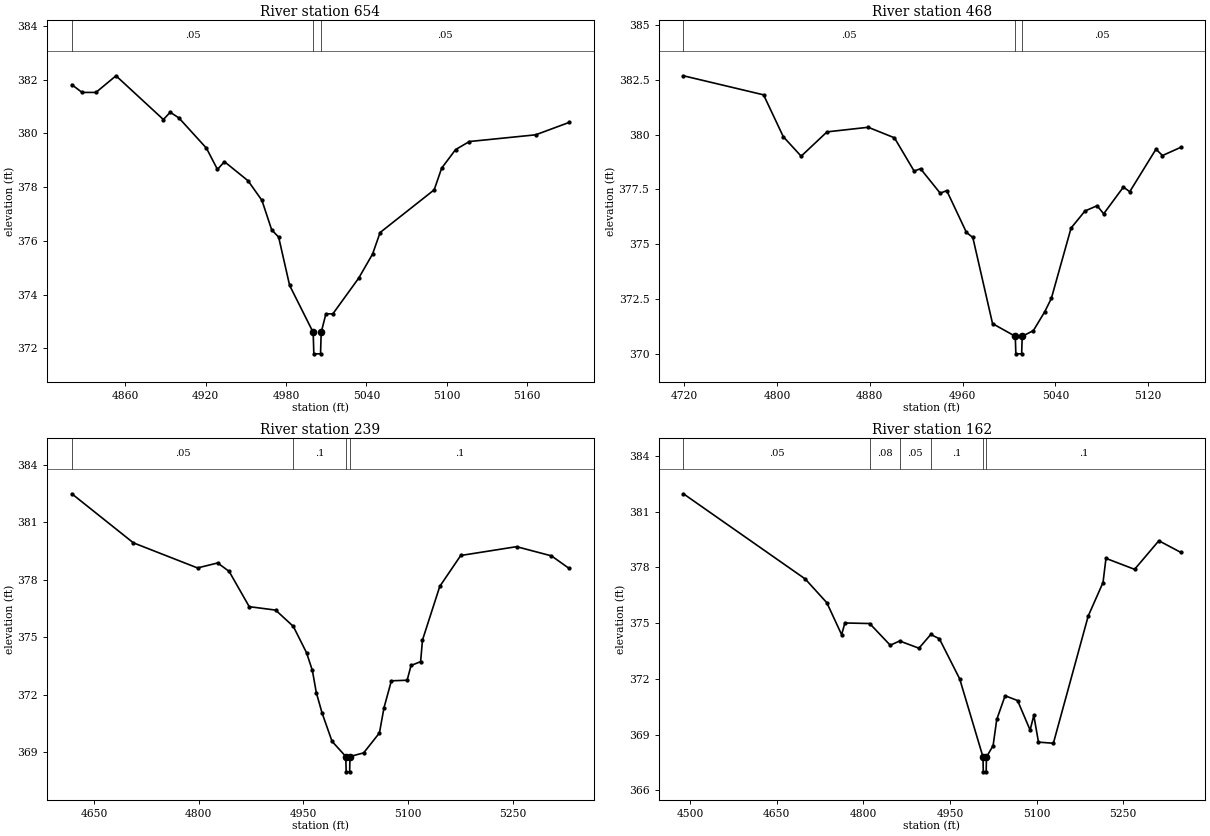
Type RM Length L Ch R = 1,654,186,186,186
BEGIN DESCRIPTION:
UNT 087 in RCW 3.0
END DESCRIPTION:
XS GIS Cut Line= 2
      2038482.38     13444071.76      2038123.01     13444165.51
#Sta/Elev= 30
  4820.0  381.82  4827.6  381.53  4838.0  381.53  4853.0  382.15  4888.4  380.52
  4893.5  380.79  4900.0  380.58  4920.6  379.45  4928.8  378.66  4934.0  378.95
  4951.6  378.24  4962.0  377.51  4969.3  376.41  4974.5  376.14  4982.7  374.34
  5000.3  372.59  5000.8  371.79  5005.8  371.79  5006.3  372.59  5009.8  373.28
  5015.0  373.28  5034.3  374.61  5044.7  375.51  5050.3  376.31  5090.7  377.90
  5096.3  378.71  5106.7  379.40  5117.0  379.70  5166.5  379.95  5191.4  380.41
#Mann=3,-1,0
  4820.0    0.05       0  5000.3    0.03       0  5006.3    0.05       0
Bank Sta=5000.3,5006.3
Exp/Cntr=0.3,0.1

Type RM Length L Ch R = 1,468,229,229,229
BEGIN DESCRIPTION:
UNT 087 in RCW 2.0
END DESCRIPTION:
XS GIS Cut Line= 2
      2038496.30     13443821.76      2038110.89     13444009.25
#Sta/Elev= 30
  4719.3  382.68  4788.4  381.81  4805.4  379.90  4820.8  379.01  4843.1  380.12
  4878.6  380.33  4901.2  379.85  4918.2  378.33  4923.7  378.44  4940.7  377.32
  4946.3  377.44  4963.3  375.53  4968.8  375.30  4985.8  371.37  5005.4  370.79
  5005.9  369.99  5010.9  369.99  5011.4  370.79  5021.0  371.05  5030.9  371.92
  5036.5  372.52  5053.5  375.73  5065.5  376.51  5076.0  376.75  5081.6  376.38
  5098.6  377.60  5104.1  377.39  5126.7  379.33  5132.3  379.04  5147.9  379.41
#Mann=3,-1,0
  4719.3    0.05       0  5005.4    0.03       0  5011.4    0.05       0
Bank Sta=5005.4,5011.4
Exp/Cntr=0.3,0.1

Type RM Length L Ch R = 1,239,77,77,77
BEGIN DESCRIPTION:
UNT 087 in RCW 1.0
END DESCRIPTION:
XS GIS Cut Line= 4
      2038520.63     13443752.34      2038367.82     13443641.20
      2038090.04     13443774.88      2038088.31     13443990.06
#Sta/Elev= 30
  4618.2  382.49  4706.4  379.93  4798.3  378.62  4827.2  378.88  4843.6  378.44
  4872.4  376.60  4910.2  376.42  4935.6  375.57  4954.6  374.19  4962.9  373.27
  4968.5  372.12  4976.7  371.06  4991.1  369.57  5010.8  368.78  5011.3  367.98
  5016.3  367.98  5016.8  368.78  5036.4  368.97  5059.0  370.01  5065.5  371.32
  5076.1  372.73  5098.7  372.76  5104.3  373.53  5118.0  373.73  5120.7  374.86
  5145.5  377.66  5175.5  379.27  5255.5  379.73  5305.5  379.25  5330.6  378.60
#Mann=4,-1,0
  4618.2    0.05       0  4935.6     0.1       0  5010.8    0.07       0
  5016.8     0.1       0
Bank Sta=5010.8,5016.8
Exp/Cntr=0.3,0.1

Type RM Length L Ch R = 1,162,0,0,0
BEGIN DESCRIPTION:
UNT 087 in RCW 9.0
END DESCRIPTION:
XS GIS Cut Line= 4
      2038572.66     13443655.08      2038333.10     13443517.94
      2038050.11     13443740.16      2038074.42     13443964.10
#Sta/Elev= 30
  4488.2  381.97  4699.2  377.38  4736.6  376.10  4762.2  374.38  4767.9  375.01
  4810.8  374.98  4846.5  373.81  4862.7  374.04  4896.2  373.65  4916.6  374.39
  4931.5  374.16  4966.7  372.00  5007.1  367.79  5007.6  366.99  5012.6  366.99
  5013.1  367.79  5024.6  368.40  5030.9  369.81  5045.4  371.09  5067.0  370.83
  5088.7  369.24  5095.1  370.03  5103.2  368.59  5129.0  368.53  5189.3  375.38
  5215.0  377.19  5220.1  378.49  5269.7  377.90  5311.7  379.44  5349.3  378.82
#Mann=6,-1,0
  4488.2    0.05       0  4810.8    0.08       0  4862.7    0.05       0
  4916.6     0.1       0  5007.1    0.07       0  5013.1     0.1       0
Bank Sta=5007.1,5013.1
Exp/Cntr=0.3,0.1

Chan Stop Cuts=-1