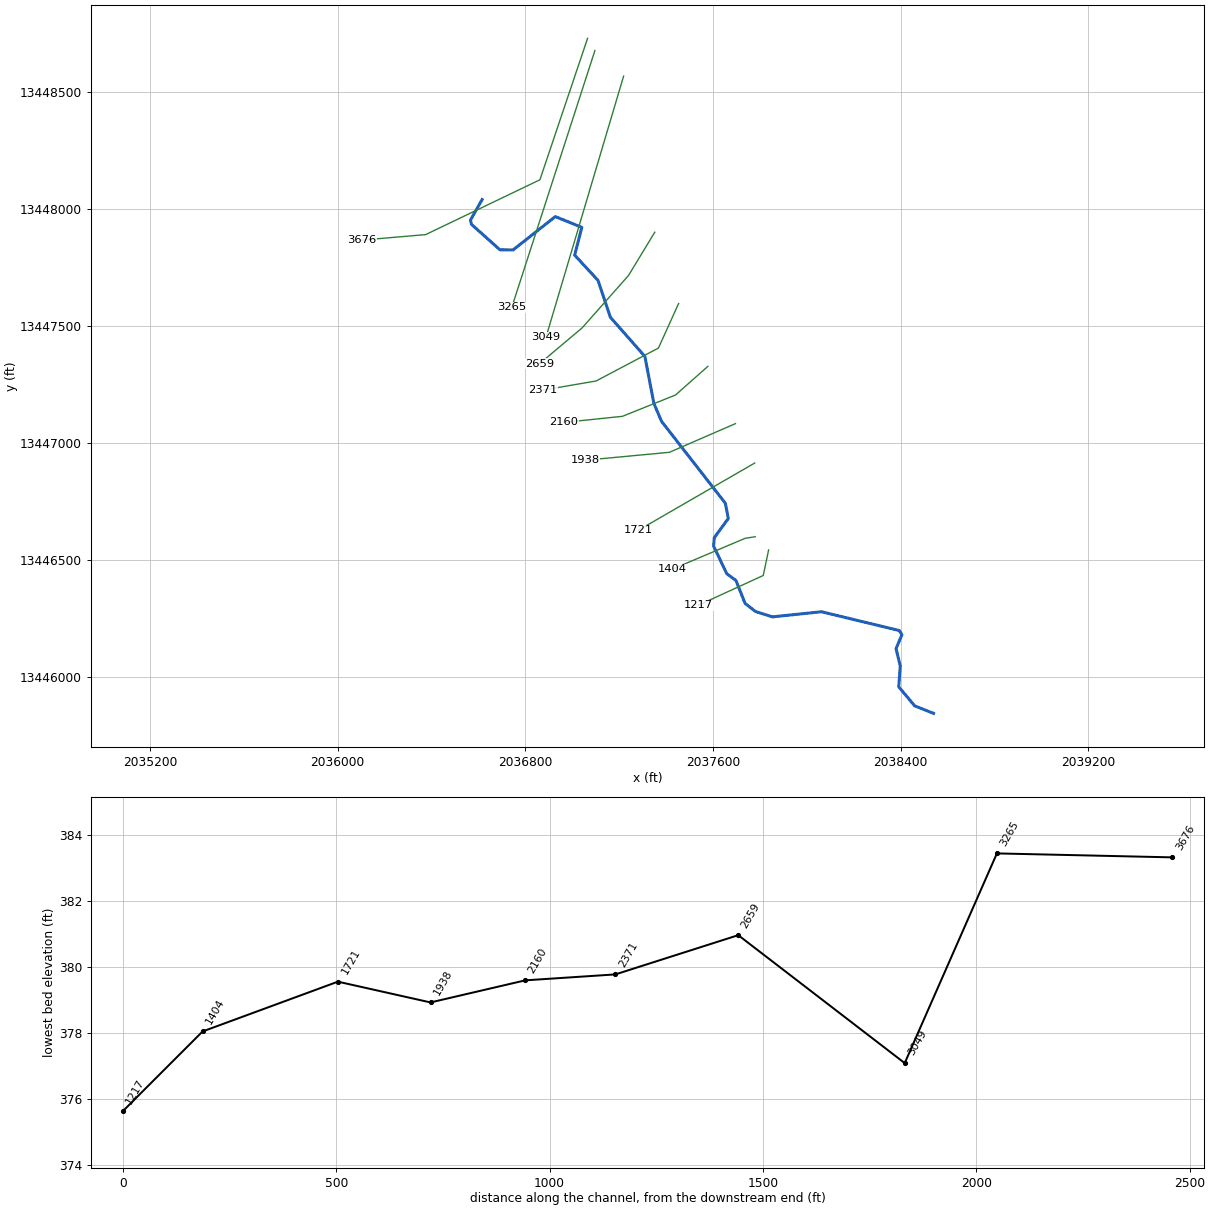
--- UNT 089 in RCW.prj (project) ---

Proj Title=UNT 089 in RCW Base Level Engineering
Current Plan=p01
Default Exp/Contr=0.3,0.1
English Units
Geom File=g01
Flow File=f01
Plan File=p01
BEGIN DESCRIPTION:
UNT 089 in RCW
END DESCRIPTION:

--- UNT 089 in RCW.p01 (plan) ---

Plan Title=Multiple Run
Short Identifier=Multiple
Geom File=g01
Flow File=f01
Subcritical Flow
K Sum by GR= 0
Std Step Tol= 0.01
Critical Tol= 0.01
Num of Std Step Trials= 20
Max Error Tol= 0.3
Flow Tol Ratio= 0.001
Split Flow NTrial= 30
Split Flow Tol= 0.02
Split Flow Ratio= 0.02
Log Output Level= 0
Friction Slope Method= 1
Unsteady Friction Slope Method= 2
Unsteady Bridges Friction Slope Method= 1
Parabolic Critical Depth
Global Vel Dist=  1 , 1 , 1
Global Log Level= 0
CheckData=True
Encroach Param= -1, 0, 0, 0
BEGIN DESCRIPTION:
Multiple Run
END DESCRIPTION:

--- UNT 089 in RCW.f01 (steady flow) ---

Flow Title=Multiple
Number of Profiles=7
Profile Names=10-year,25-year,50-year,1pct_min,100-year,1pct_plu,500-year
River Rch & RM= UNT 089 in RCW,Reach-1,3676
      58      73      85      50      99     198     135
Boundary for River Rch & Prof#=UNT 089 in RCW,Reach-1,1
Up Type=0
Dn Type=3
Dn Slope=0.005
Boundary for River Rch & Prof#=UNT 089 in RCW,Reach-1,2
Up Type=0
Dn Type=3
Dn Slope=0.005
Boundary for River Rch & Prof#=UNT 089 in RCW,Reach-1,3
Up Type=0
Dn Type=3
Dn Slope=0.005
Boundary for River Rch & Prof#=UNT 089 in RCW,Reach-1,4
Up Type=0
Dn Type=3
Dn Slope=0.005
Boundary for River Rch & Prof#=UNT 089 in RCW,Reach-1,5
Up Type=0
Dn Type=3
Dn Slope=0.005
Boundary for River Rch & Prof#=UNT 089 in RCW,Reach-1,6
Up Type=0
Dn Type=3
Dn Slope=0.005
Boundary for River Rch & Prof#=UNT 089 in RCW,Reach-1,7
Up Type=0
Dn Type=3
Dn Slope=0.005

--- UNT 089 in RCW.g01 (geometry) ---

Geom Title=Existing Conditions

River Reach=UNT 089 in RCW,Reach-1
Reach XY= 30
      2036615.74     13448039.12      2036565.70     13447950.94
      2036570.56     13447932.88      2036691.39     13447824.55
      2036747.64     13447823.85      2036927.50     13447966.21
      2037040.70     13447920.38      2037010.14     13447801.63
      2037109.45     13447693.99      2037162.23     13447536.35
      2037309.45     13447368.99      2037347.64     13447168.99
      2037380.28     13447091.91      2037652.50     13446741.91
      2037665.00     13446676.63      2037605.28     13446594.69
      2037602.50     13446558.57      2037658.75     13446440.52
      2037697.64     13446412.05      2037736.53     13446314.13
      2037780.97     13446279.41      2037853.20     13446256.49
      2038062.22     13446278.37      2038393.82     13446198.16
      2038405.28     13446180.45      2038380.28     13446120.73
      2038397.99     13446047.12      2038391.74     13445957.53
      2038459.79     13445876.28      2038540.07     13445844.28

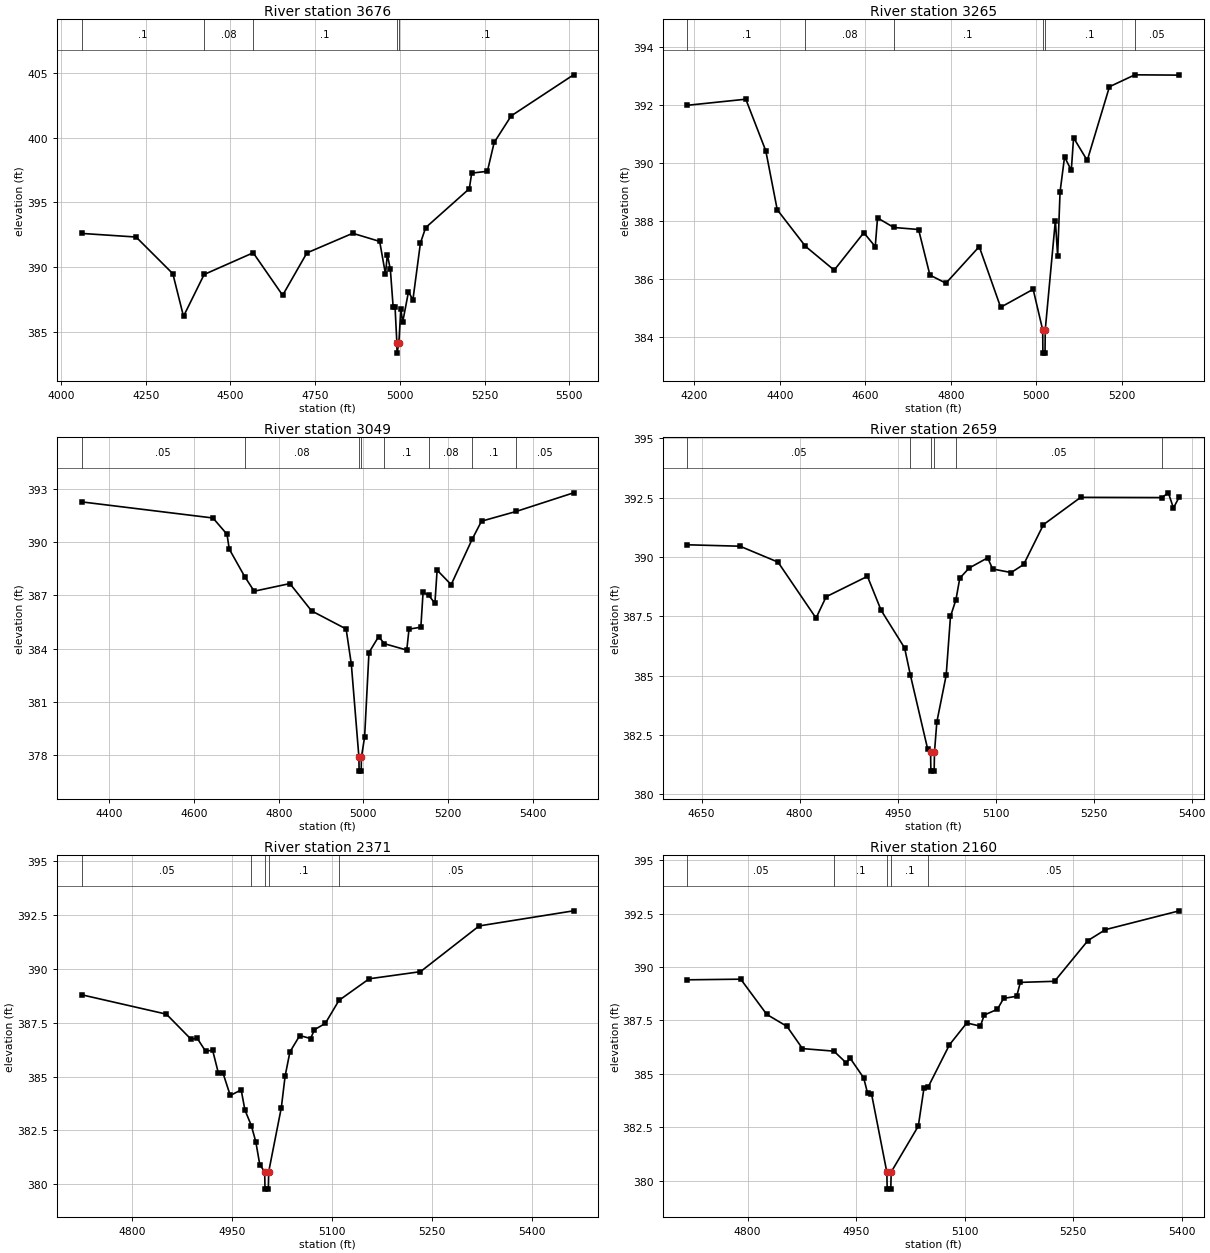
Type RM Length L Ch R = 1,3676,411,411,411
BEGIN DESCRIPTION:
UNT 089 in RCW 1.0
END DESCRIPTION:
XS GIS Cut Line= 4
      2037065.16     13448727.65      2036862.04     13448123.50
      2036374.96     13447889.32      2036101.61     13447865.69
#Sta/Elev= 30
  4060.6  392.60  4221.6  392.32  4330.1  389.48  4361.6  386.18  4422.5  389.42
  4567.3  391.10  4654.2  387.81  4725.8  391.09  4861.1  392.61  4940.6  391.98
  4957.7  389.45  4963.2  390.96  4972.1  389.82  4980.3  386.92  4985.9  386.93
  4991.3  384.13  4991.8  383.33  4997.3  384.13  5003.0  386.76  5008.5  385.73
  5025.6  388.08  5038.7  387.46  5060.9  391.86  5076.4  393.05  5205.1  396.06
  5212.2  397.27  5258.5  397.41  5278.5  399.64  5328.7  401.70  5512.8  404.88
#Mann=5,-1,0
  4060.6     0.1       0  4422.5    0.08       0  4567.3     0.1       0
  4991.3    0.07       0  4997.3     0.1       0
Bank Sta=4991.3,4997.3
Exp/Cntr=0.3,0.1

Type RM Length L Ch R = 1,3265,216,216,216
BEGIN DESCRIPTION:
Mapping XS b4d3095a
END DESCRIPTION:
XS GIS Cut Line= 2
      2037096.40     13448675.55      2036742.37     13447579.61
#Sta/Elev= 30
  4183.2  391.99  4320.4  392.20  4367.2  390.42  4394.0  388.39  4460.1  387.13
  4527.3  386.31  4596.6  387.60  4623.4  387.12  4628.7  388.11  4666.8  387.78
  4724.8  387.71  4751.3  386.14  4788.8  385.86  4866.8  387.12  4916.9  385.03
  4993.0  385.65  5015.3  384.25  5015.8  383.45  5020.8  383.45  5021.3  384.25
  5045.0  388.02  5050.3  386.80  5056.0  389.01  5066.5  390.21  5082.3  389.75
  5087.6  390.87  5119.6  390.09  5171.6  392.63  5231.0  393.04  5334.9  393.03
#Mann=6,-1,0
  4183.2     0.1       0  4460.1    0.08       0  4666.8     0.1       0
  5015.3    0.07       0  5021.3     0.1       0  5231.0    0.05       0
Bank Sta=5015.3,5021.3
Exp/Cntr=0.3,0.1

Type RM Length L Ch R = 1,3049,390,390,390
BEGIN DESCRIPTION:
Mapping XS 80173c1f
END DESCRIPTION:
XS GIS Cut Line= 2
      2037218.80     13448566.19      2036888.08     13447451.62
#Sta/Elev= 30
  4334.0  392.28  4644.6  391.37  4677.8  390.45  4683.0  389.62  4719.7  388.06
  4742.0  387.24  4826.3  387.67  4877.6  386.13  4959.2  385.11  4971.5  383.13
  4989.4  377.89  4989.9  377.09  4994.9  377.09  4995.4  377.89  5002.9  379.01
  5013.2  383.78  5036.1  384.68  5049.5  384.28  5102.5  383.92  5107.8  385.10
  5135.8  385.21  5141.0  387.17  5153.9  387.02  5169.0  386.56  5174.2  388.43
  5207.4  387.61  5257.2  390.18  5279.1  391.19  5361.1  391.74  5496.6  392.79
#Mann=8,-1,0
  4334.0    0.05       0  4719.7    0.08       0  4989.4    0.07       0
  4995.4    0.08       0  5049.5     0.1       0  5153.9    0.08       0
  5257.2     0.1       0  5361.1    0.05       0
Bank Sta=4989.4,4995.4
Exp/Cntr=0.3,0.1

Type RM Length L Ch R = 1,2659,288,288,288
BEGIN DESCRIPTION:
Mapping XS 57f10bab
END DESCRIPTION:
XS GIS Cut Line= 4
      2037351.63     13447899.55      2037239.64     13447714.65
      2037041.73     13447490.69      2036859.70     13447337.27
#Sta/Elev= 30
  4627.9  390.51  4708.7  390.45  4766.9  389.78  4825.1  387.42  4840.6  388.32
  4903.8  389.18  4924.7  387.75  4960.7  386.16  4969.5  385.02  4995.8  381.92
  5000.4  381.77  5000.9  380.97  5005.9  380.97  5006.4  381.77  5010.0  383.04
  5024.3  385.01  5030.9  387.49  5039.3  388.20  5045.1  389.10  5059.4  389.53
  5087.8  389.96  5095.4  389.49  5123.8  389.34  5142.9  389.68  5173.2  391.36
  5230.2  392.51  5354.6  392.50  5364.4  392.70  5372.1  392.06  5381.0  392.52
#Mann=6,-1,0
  4627.9    0.05       0  4969.5     0.1       0  5000.4    0.07       0
  5006.4     0.1       0  5039.3    0.05       0  5354.6    0.08       0
Bank Sta=5000.4,5006.4
Exp/Cntr=0.3,0.1

Type RM Length L Ch R = 1,2371,211,211,211
BEGIN DESCRIPTION:
Mapping XS 69293be5
END DESCRIPTION:
XS GIS Cut Line= 4
      2037453.17     13447594.81      2037367.25     13447404.75
      2037101.62     13447264.12      2036875.10     13447225.07
#Sta/Elev= 30
  4723.5  388.79  4851.0  387.89  4887.9  386.73  4897.3  386.77  4909.9  386.17
  4920.4  386.22  4929.2  385.14  4936.2  385.14  4946.9  384.12  4963.3  384.38
  4968.9  383.45  4978.6  382.72  4985.3  381.97  4991.2  380.92  4998.6  380.58
  4999.1  379.78  5004.1  379.78  5004.6  380.58  5023.6  383.56  5029.3  385.02
  5036.5  386.14  5051.3  386.90  5067.6  386.76  5073.3  387.17  5089.6  387.46
  5110.2  388.53  5155.6  389.53  5232.6  389.86  5320.7  391.98  5462.5  392.68
#Mann=5,-1,0
  4723.5    0.05       0  4978.6     0.1       0  4998.6    0.07       0
  5004.6     0.1       0  5110.2    0.05       0
Bank Sta=4998.6,5004.6
Exp/Cntr=0.3,0.1

Type RM Length L Ch R = 1,2160,222,222,222
BEGIN DESCRIPTION:
Mapping XS 6dd16e1c
END DESCRIPTION:
XS GIS Cut Line= 4
      2037578.16     13447326.61      2037440.16     13447204.23
      2037213.60     13447113.08      2036963.61     13447087.04
#Sta/Elev= 30
  4716.6  389.40  4790.6  389.43  4826.6  387.78  4854.5  387.22  4875.9  386.18
  4919.4  386.06  4936.4  385.51  4941.8  385.73  4960.5  384.81  4965.9  384.09
  4971.3  384.07  4992.5  380.40  4993.0  379.60  4998.0  379.60  4998.5  380.40
  5036.0  382.55  5043.8  384.32  5049.9  384.40  5079.1  386.36  5103.0  387.38
  5121.8  387.23  5127.1  387.75  5145.3  388.02  5153.9  388.53  5172.0  388.63
  5177.0  389.28  5224.3  389.33  5270.5  391.24  5294.7  391.75  5396.6  392.63
#Mann=5,-1,0
  4716.6    0.05       0  4919.4     0.1       0  4992.5    0.07       0
  4998.5     0.1       0  5049.9    0.05       0
Bank Sta=4992.5,4998.5
Exp/Cntr=0.3,0.1

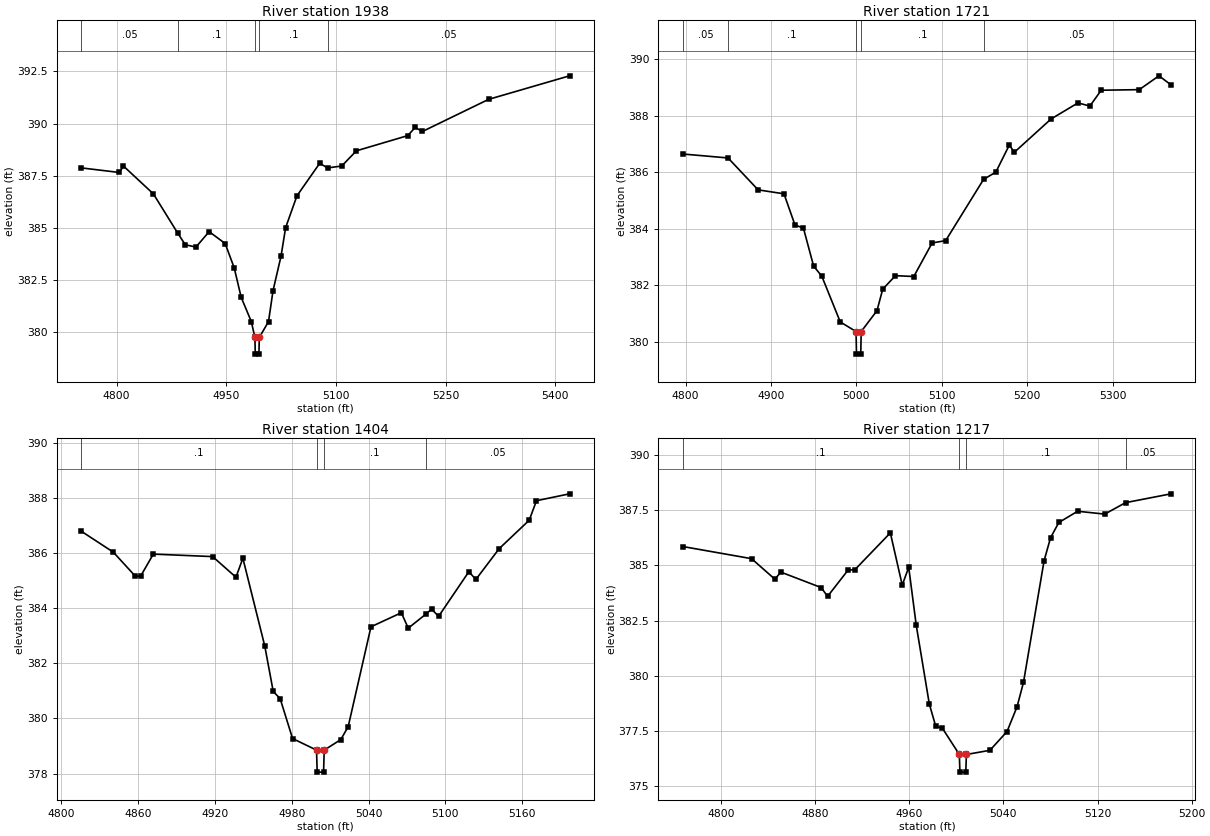
Type RM Length L Ch R = 1,1938,217,217,217
BEGIN DESCRIPTION:
Mapping XS c08502d7
END DESCRIPTION:
XS GIS Cut Line= 3
      2037695.40     13447081.84      2037414.12     13446959.44
      2037054.77     13446925.59
#Sta/Elev= 30
  4751.7  387.87  4803.8  387.65  4809.3  387.96  4850.3  386.62  4883.5  384.74
  4893.9  384.18  4908.5  384.07  4926.5  384.81  4948.4  384.24  4960.8  383.07
  4970.3  381.66  4984.2  380.49  4989.1  379.73  4989.6  378.93  4994.6  378.93
  4995.1  379.73  5007.7  380.49  5013.9  381.98  5024.8  383.63  5031.1  385.00
  5046.6  386.53  5077.7  388.09  5088.5  387.87  5107.8  387.96  5127.9  388.69
  5198.2  389.42  5208.2  389.81  5218.3  389.62  5308.7  391.16  5419.4  392.29
#Mann=5,-1,0
  4751.7    0.05       0  4883.5     0.1       0  4989.1    0.07       0
  4995.1     0.1       0  5088.5    0.05       0
Bank Sta=4989.1,4995.1
Exp/Cntr=0.3,0.1

Type RM Length L Ch R = 1,1721,317,317,317
BEGIN DESCRIPTION:
UNT 089 in RCW 2.0
END DESCRIPTION:
XS GIS Cut Line= 2
      2037777.56     13446913.53      2037282.80     13446627.08
#Sta/Elev= 30
  4796.7  386.65  4849.7  386.51  4884.9  385.38  4915.2  385.24  4928.0  384.14
  4938.0  384.02  4949.9  382.68  4959.5  382.32  4981.1  380.70  4999.6  380.36
  5000.1  379.56  5005.1  379.56  5005.6  380.36  5024.1  381.10  5030.8  381.86
  5045.7  382.34  5067.2  382.31  5088.7  383.50  5104.5  383.58  5148.9  385.75
  5163.3  386.01  5179.1  386.97  5184.9  386.71  5227.9  387.89  5259.4  388.46
  5273.4  388.35  5286.7  388.91  5331.2  388.93  5354.3  389.42  5368.4  389.10
#Mann=5,-1,0
  4796.7    0.05       0  4849.7     0.1       0  4999.6    0.07       0
  5005.6     0.1       0  5148.9    0.05       0
Bank Sta=4999.6,5005.6
Exp/Cntr=0.3,0.1

Type RM Length L Ch R = 1,1404,187,187,187
BEGIN DESCRIPTION:
UNT 089 in RCW 3.0
END DESCRIPTION:
XS GIS Cut Line= 3
      2037779.70     13446598.80      2037736.32     13446591.86
      2037426.01     13446459.98
#Sta/Elev= 30
  4815.8  386.80  4840.8  386.04  4857.9  385.17  4862.1  385.17  4872.0  385.97
  4918.3  385.88  4936.5  385.13  4941.9  385.82  4959.0  382.63  4965.6  380.98
  4971.0  380.72  4980.7  379.27  4999.4  378.85  4999.9  378.05  5004.9  378.05
  5005.4  378.85  5018.3  379.23  5024.1  379.70  5041.9  383.33  5065.6  383.84
  5071.0  383.28  5084.5  383.78  5089.2  383.97  5094.7  383.71  5118.3  385.33
  5123.8  385.05  5142.0  386.17  5165.4  387.20  5171.1  387.91  5196.9  388.16
#Mann=4,-1,0
  4815.8     0.1       0  4999.4    0.07       0  5005.4     0.1       0
  5084.5    0.05       0
Bank Sta=4999.4,5005.4
Exp/Cntr=0.3,0.1

Type RM Length L Ch R = 1,1217,0,0,0
BEGIN DESCRIPTION:
UNT 089 in RCW 4.0
END DESCRIPTION:
XS GIS Cut Line= 3
      2037836.90     13446542.20      2037814.15     13446433.30
      2037538.38     13446306.67
#Sta/Elev= 30
  4767.7  385.86  4826.1  385.31  4845.9  384.38  4851.0  384.70  4885.2  384.00
  4890.7  383.60  4908.2  384.80  4913.7  384.80  4944.0  386.48  4954.1  384.11
  4959.6  384.92  4966.0  382.29  4977.1  378.72  4982.6  377.70  4988.1  377.63
  5002.6  376.43  5003.1  375.63  5008.1  375.63  5008.6  376.43  5028.6  376.62
  5043.1  377.47  5051.6  378.59  5057.1  379.70  5074.6  385.22  5080.1  386.26
  5087.1  386.95  5103.1  387.46  5126.1  387.33  5143.8  387.85  5182.4  388.25
#Mann=4,-1,0
  4767.7     0.1       0  5002.6    0.07       0  5008.6     0.1       0
  5143.8    0.05       0
Bank Sta=5002.6,5008.6
Exp/Cntr=0.3,0.1

Chan Stop Cuts=-1