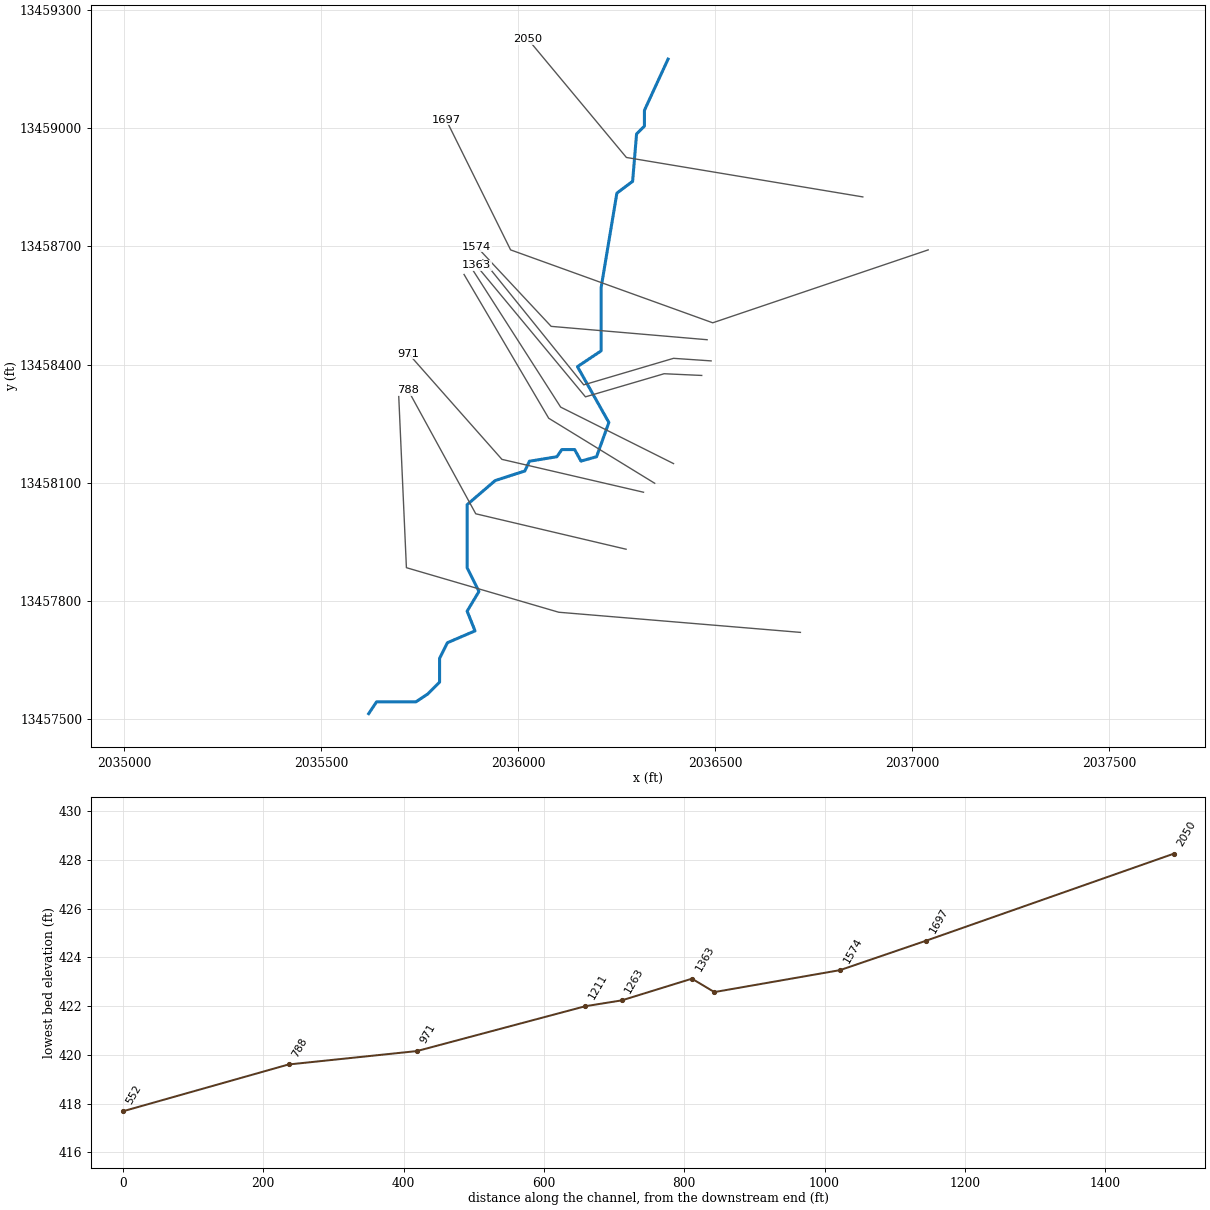
--- UNT 090 in RCW.prj (project) ---

Proj Title=UNT 090 in RCW Base Level Engineering
Current Plan=p01
Default Exp/Contr=0.3,0.1
English Units
Geom File=g01
Flow File=f01
Plan File=p01
BEGIN DESCRIPTION:
UNT 090 in RCW
END DESCRIPTION:

--- UNT 090 in RCW.p01 (plan) ---

Plan Title=Multiple Run
Short Identifier=Multiple
Geom File=g01
Flow File=f01
Subcritical Flow
K Sum by GR= 0
Std Step Tol= 0.01
Critical Tol= 0.01
Num of Std Step Trials= 20
Max Error Tol= 0.3
Flow Tol Ratio= 0.001
Split Flow NTrial= 30
Split Flow Tol= 0.02
Split Flow Ratio= 0.02
Log Output Level= 0
Friction Slope Method= 1
Unsteady Friction Slope Method= 2
Unsteady Bridges Friction Slope Method= 1
Parabolic Critical Depth
Global Vel Dist=  1 , 1 , 1
Global Log Level= 0
CheckData=True
Encroach Param= -1, 0, 0, 0
BEGIN DESCRIPTION:
Multiple Run
END DESCRIPTION:

--- UNT 090 in RCW.f01 (steady flow) ---

Flow Title=Multiple
Number of Profiles=7
Profile Names=10-year,25-year,50-year,1pct_min,100-year,1pct_plu,500-year
River Rch & RM= UNT 090 in RCW,Reach-1,2050
      95     125     149      89     177     353     253
Boundary for River Rch & Prof#=UNT 090 in RCW,Reach-1,1
Up Type=0
Dn Type=3
Dn Slope=0.005
Boundary for River Rch & Prof#=UNT 090 in RCW,Reach-1,2
Up Type=0
Dn Type=3
Dn Slope=0.005
Boundary for River Rch & Prof#=UNT 090 in RCW,Reach-1,3
Up Type=0
Dn Type=3
Dn Slope=0.005
Boundary for River Rch & Prof#=UNT 090 in RCW,Reach-1,4
Up Type=0
Dn Type=3
Dn Slope=0.005
Boundary for River Rch & Prof#=UNT 090 in RCW,Reach-1,5
Up Type=0
Dn Type=3
Dn Slope=0.005
Boundary for River Rch & Prof#=UNT 090 in RCW,Reach-1,6
Up Type=0
Dn Type=3
Dn Slope=0.005
Boundary for River Rch & Prof#=UNT 090 in RCW,Reach-1,7
Up Type=0
Dn Type=3
Dn Slope=0.005

--- UNT 090 in RCW.g01 (geometry) ---

Geom Title=Existing Conditions

River Reach=UNT 090 in RCW,Reach-1
Reach XY= 30
      2036380.80     13459174.54      2036320.80     13459044.54
      2036320.80     13459004.54      2036300.80     13458984.54
      2036290.80     13458864.54      2036250.80     13458834.54
      2036210.80     13458594.54      2036210.80     13458434.54
      2036150.80     13458394.54      2036230.51     13458252.96
      2036199.26     13458166.15      2036159.67     13458155.04
      2036143.70     13458184.21      2036111.06     13458184.21
      2036098.56     13458166.15      2036028.70     13458154.66
      2036017.31     13458130.04      2035941.93     13458105.67
      2035870.80     13458044.54      2035870.80     13457884.54
      2035900.80     13457824.54      2035870.80     13457774.54
      2035890.80     13457724.54      2035820.80     13457694.54
      2035800.80     13457654.54      2035800.80     13457594.54
      2035770.80     13457564.54      2035740.80     13457544.54
      2035640.80     13457544.54      2035620.80     13457514.54

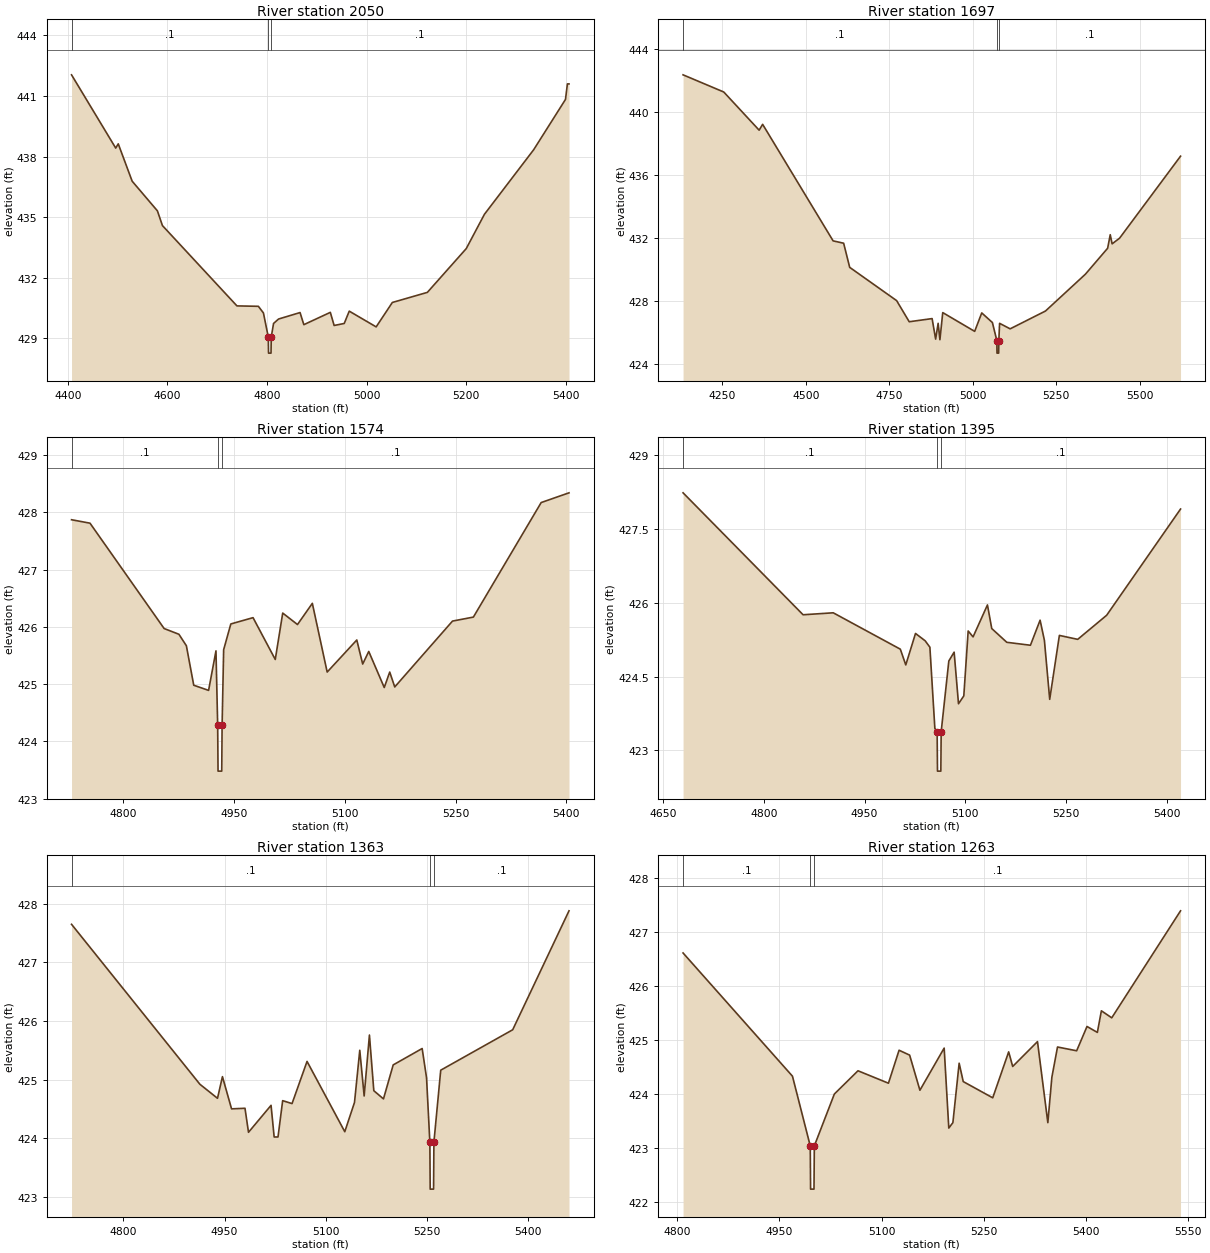
Type RM Length L Ch R = 1,2050,353,353,353
BEGIN DESCRIPTION:
UNT 090 in RCW 2.0
END DESCRIPTION:
XS GIS Cut Line= 3
      2036875.04     13458824.99      2036275.00     13458925.00
      2036025.02     13459224.98
#Sta/Elev= 30
  4407.7  442.05  4496.4  438.42  4501.5  438.63  4529.4  436.78  4580.1  435.31
  4590.2  434.58  4739.8  430.60  4782.8  430.58  4793.0  430.25  4802.7  429.06
  4803.2  428.26  4808.2  428.26  4808.7  429.06  4813.3  429.73  4823.4  429.95
  4866.5  430.27  4874.1  429.67  4927.3  430.28  4934.9  429.63  4955.2  429.73
  4965.3  430.34  5019.3  429.56  5051.8  430.77  5122.1  431.27  5200.2  433.44
  5236.7  435.14  5335.6  438.34  5399.4  440.83  5403.3  441.60  5406.5  441.60
#Mann=3,-1,0
  4407.7     0.1       0  4802.7    0.07       0  4808.7     0.1       0
Bank Sta=4802.7,4808.7
Exp/Cntr=0.3,0.1

Type RM Length L Ch R = 1,1697,123,123,123
BEGIN DESCRIPTION:
Mapping XS 34cce768
END DESCRIPTION:
XS GIS Cut Line= 4
      2037040.97     13458690.65      2036494.11     13458505.76
      2035981.09     13458690.66      2035817.38     13459020.70
#Sta/Elev= 30
  4132.0  442.34  4254.0  441.25  4360.0  438.83  4370.5  439.20  4581.7  431.81
  4613.3  431.66  4631.4  430.13  4772.1  428.02  4809.8  426.68  4878.4  426.88
  4889.0  425.58  4896.5  426.58  4901.8  425.54  4910.3  427.26  5006.0  426.07
  5027.2  427.24  5059.1  426.63  5072.4  425.49  5072.9  424.69  5077.9  424.69
  5078.4  425.49  5080.7  426.58  5112.3  426.23  5218.2  427.36  5337.6  429.69
  5404.5  431.34  5412.3  432.20  5417.9  431.62  5440.3  431.98  5623.0  437.18
#Mann=3,-1,0
  4132.0     0.1       0  5072.4    0.07       0  5078.4     0.1       0
Bank Sta=5072.4,5078.4
Exp/Cntr=0.3,0.1

Type RM Length L Ch R = 1,1574,179,179,179
BEGIN DESCRIPTION:
Mapping XS 0b7e4213
END DESCRIPTION:
XS GIS Cut Line= 3
      2036479.92     13458462.85      2036084.07     13458496.71
      2035895.24     13458698.56
#Sta/Elev= 30
  4729.9  427.87  4754.9  427.81  4855.3  425.97  4875.3  425.87  4885.4  425.67
  4895.4  424.98  4915.5  424.89  4925.5  425.58  4927.8  424.28  4928.3  423.48
  4933.3  423.48  4933.8  424.28  4935.9  425.60  4945.6  426.05  4975.7  426.16
  5005.8  425.43  5015.9  426.24  5035.9  426.04  5056.0  426.41  5076.1  425.21
  5116.2  425.77  5124.2  425.35  5132.4  425.57  5153.4  424.94  5160.8  425.21
  5167.6  424.95  5245.8  426.10  5274.1  426.17  5365.9  428.17  5403.6  428.34
#Mann=3,-1,0
  4729.9     0.1       0  4927.8    0.07       0  4933.8     0.1       0
Bank Sta=4927.8,4933.8
Exp/Cntr=0.3,0.1

Type RM Length L Ch R = 1,1395,32,32,32
BEGIN DESCRIPTION:
Mapping XS c70bb6dd
END DESCRIPTION:
XS GIS Cut Line= 4
      2036490.08     13458409.15      2036394.62     13458415.66
      2036166.75     13458348.39      2035910.65     13458665.26
#Sta/Elev= 30
  4679.8  428.24  4858.5  425.76  4903.4  425.80  5003.3  425.06  5011.4  424.74
  5025.9  425.38  5040.3  425.23  5047.3  425.10  5054.7  423.45  5058.1  423.38
  5058.6  422.58  5063.6  422.58  5064.1  423.38  5075.5  424.82  5083.4  425.00
  5089.9  423.95  5097.8  424.11  5104.3  425.43  5111.6  425.31  5133.0  425.96
  5139.4  425.48  5161.8  425.20  5197.0  425.14  5211.4  425.65  5217.8  425.24
  5225.7  424.04  5240.1  425.34  5267.4  425.26  5310.5  425.75  5420.5  427.91
#Mann=3,-1,0
  4679.8     0.1       0  5058.1    0.07       0  5064.1     0.1       0
Bank Sta=5058.1,5064.1
Exp/Cntr=0.3,0.1

Type RM Length L Ch R = 1,1363,100,100,100
BEGIN DESCRIPTION:
Mapping XS 499bc1b5
END DESCRIPTION:
XS GIS Cut Line= 4
      2036466.22     13458372.26      2036370.75     13458376.60
      2036171.09     13458318.00      2035894.22     13458651.11
#Sta/Elev= 30
  4723.4  427.65  4913.5  424.92  4939.6  424.68  4946.9  425.05  4960.4  424.50
  4980.3  424.51  4985.5  424.10  5018.9  424.56  5023.5  424.02  5029.2  424.02
  5036.1  424.64  5050.0  424.59  5072.2  425.31  5128.1  424.11  5142.5  424.61
  5150.3  425.50  5156.8  424.72  5164.6  425.76  5171.1  424.81  5185.4  424.67
  5199.8  425.25  5242.7  425.53  5249.2  425.03  5254.1  423.93  5254.6  423.13
  5259.6  423.13  5260.1  423.93  5270.2  425.16  5376.8  425.85  5460.2  427.88
#Mann=3,-1,0
  4723.4     0.1       0  5254.1    0.07       0  5260.1     0.1       0
Bank Sta=5254.1,5260.1
Exp/Cntr=0.3,0.1

Type RM Length L Ch R = 1,1263,52,52,52
BEGIN DESCRIPTION:
Mapping XS 9dc69b4c
END DESCRIPTION:
XS GIS Cut Line= 3
      2036394.65     13458148.72      2036108.16     13458291.96
      2035886.78     13458637.05
#Sta/Elev= 30
  4808.6  426.61  4969.2  424.33  4995.3  423.04  4995.8  422.24  5000.8  422.24
  5001.3  423.04  5030.7  424.00  5065.4  424.43  5110.1  424.20  5125.7  424.81
  5141.2  424.72  5156.3  424.07  5191.9  424.85  5198.7  423.37  5204.7  423.47
  5213.9  424.57  5219.9  424.23  5263.2  423.93  5286.6  424.78  5292.5  424.51
  5328.9  424.97  5344.1  423.47  5350.0  424.31  5358.3  424.87  5386.4  424.80
  5401.6  425.25  5416.8  425.14  5422.7  425.54  5437.9  425.41  5538.9  427.39
#Mann=3,-1,0
  4808.6     0.1       0  4995.3    0.07       0  5001.3     0.1       0
Bank Sta=4995.3,5001.3
Exp/Cntr=0.3,0.1

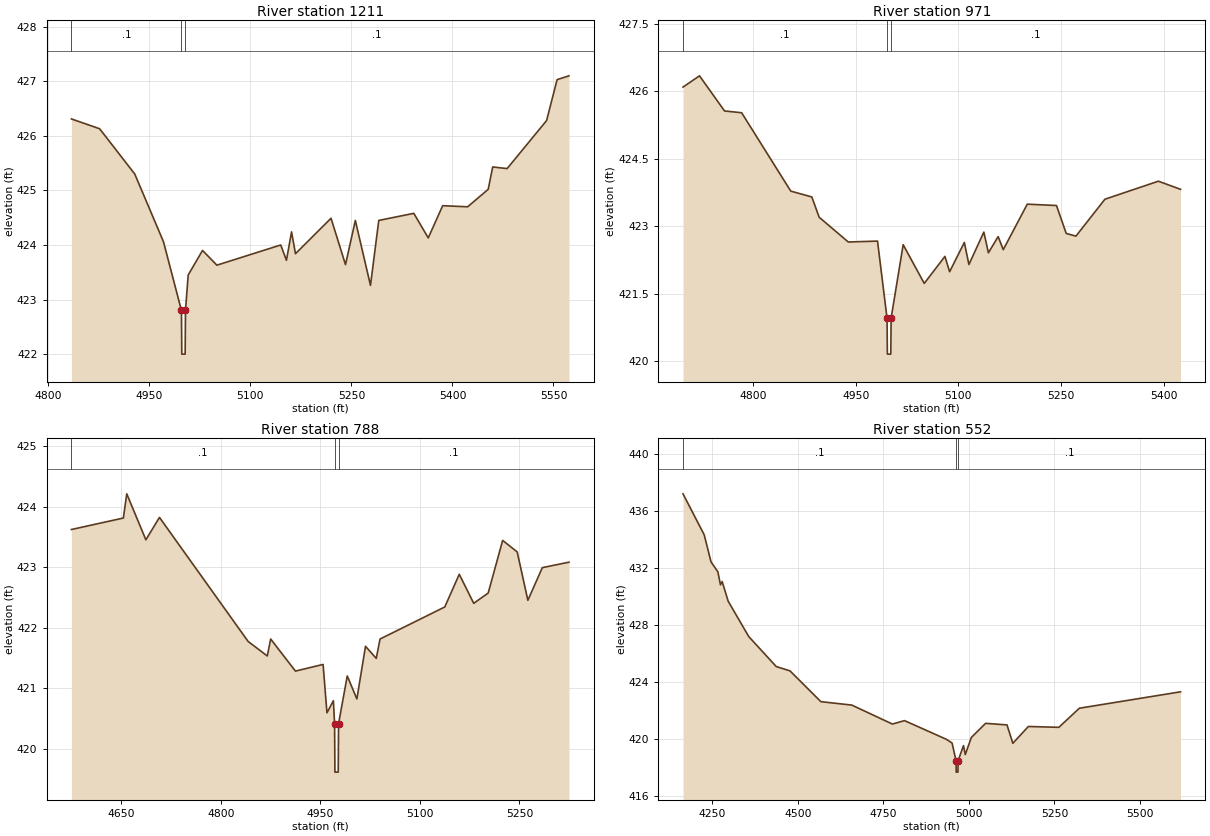
Type RM Length L Ch R = 1,1211,240,240,240
BEGIN DESCRIPTION:
Mapping XS dc0ca795
END DESCRIPTION:
XS GIS Cut Line= 3
      2036346.90     13458098.81      2036077.78     13458263.75
      2035862.95     13458628.31
#Sta/Elev= 30
  4834.2  426.31  4876.1  426.13  4928.3  425.30  4970.9  424.06  4997.6  422.80
  4998.1  422.00  5003.1  422.00  5003.6  422.80  5007.6  423.45  5028.9  423.90
  5050.2  423.63  5145.0  424.00  5153.5  423.72  5161.1  424.24  5166.9  423.84
  5219.7  424.49  5241.2  423.64  5255.8  424.45  5278.3  423.26  5290.6  424.45
  5342.6  424.58  5364.1  424.13  5385.5  424.72  5422.6  424.70  5453.1  425.02
  5459.8  425.43  5481.2  425.40  5539.8  426.28  5555.4  427.03  5573.0  427.10
#Mann=3,-1,0
  4834.2     0.1       0  4997.6    0.07       0  5003.6     0.1       0
Bank Sta=4997.6,5003.6
Exp/Cntr=0.3,0.1

Type RM Length L Ch R = 1,971,183,183,183
BEGIN DESCRIPTION:
Mapping XS e13ee263
END DESCRIPTION:
XS GIS Cut Line= 3
      2036318.45     13458076.13      2035959.07     13458159.47
      2035721.63     13458427.77
#Sta/Elev= 30
  4697.7  426.09  4721.8  426.34  4758.4  425.56  4783.4  425.52  4855.2  423.78
  4886.0  423.65  4896.7  423.20  4939.3  422.65  4982.0  422.67  4995.9  420.96
  4996.4  420.16  5001.4  420.16  5001.9  420.96  5019.5  422.59  5050.3  421.73
  5080.5  422.33  5087.4  421.99  5108.9  422.64  5115.6  422.15  5137.4  422.87
  5144.1  422.41  5158.3  422.77  5165.8  422.48  5200.9  423.49  5243.6  423.46
  5257.8  422.84  5272.0  422.78  5314.4  423.60  5392.5  424.00  5424.9  423.82
#Mann=3,-1,0
  4697.7     0.1       0  4995.9    0.07       0  5001.9     0.1       0
Bank Sta=4995.9,5001.9
Exp/Cntr=0.3,0.1

Type RM Length L Ch R = 1,788,236,236,236
BEGIN DESCRIPTION:
Mapping XS c5f62381
END DESCRIPTION:
XS GIS Cut Line= 3
      2036274.21     13457931.59      2035892.66     13458021.45
      2035720.77     13458335.27
#Sta/Elev= 30
  4574.9  423.62  4653.2  423.81  4658.3  424.21  4687.1  423.45  4707.6  423.82
  4841.2  421.77  4870.1  421.53  4875.2  421.81  4912.5  421.28  4954.2  421.39
  4960.0  420.59  4969.7  420.79  4971.5  420.41  4972.0  419.61  4977.0  419.61
  4977.5  420.41  4990.6  421.20  5005.1  420.82  5018.1  421.69  5034.3  421.49
  5040.0  421.81  5137.6  422.34  5159.4  422.88  5181.2  422.40  5203.0  422.57
  5224.8  423.44  5246.7  423.25  5262.8  422.45  5284.6  422.99  5324.7  423.08
#Mann=3,-1,0
  4574.9     0.1       0  4971.5    0.07       0  4977.5     0.1       0
Bank Sta=4971.5,4977.5
Exp/Cntr=0.3,0.1

Type RM Length L Ch R = 1,552,0,0,0
BEGIN DESCRIPTION:
UNT 090 in RCW 1.0
END DESCRIPTION:
XS GIS Cut Line= 4
      2036716.65     13457720.71      2036103.31     13457771.79
      2035716.66     13457884.77      2035697.15     13458320.45
#Sta/Elev= 30
  4164.1  437.20  4226.0  434.33  4246.0  432.43  4266.1  431.73  4273.6  430.82
  4278.6  431.05  4296.2  429.67  4356.4  427.19  4436.7  425.09  4476.8  424.79
  4567.1  422.63  4657.5  422.39  4776.2  421.06  4811.6  421.30  4934.1  419.99
  4950.6  419.73  4962.3  418.49  4962.8  417.69  4967.8  417.69  4968.3  418.49
  4984.0  419.55  4989.2  418.92  5007.0  420.12  5048.7  421.11  5111.2  421.00
  5128.3  419.71  5173.7  420.89  5262.7  420.83  5322.7  422.17  5618.5  423.32
#Mann=3,-1,0
  4164.1     0.1       0  4962.3    0.07       0  4968.3     0.1       0
Bank Sta=4962.3,4968.3
Exp/Cntr=0.3,0.1

Chan Stop Cuts=-1