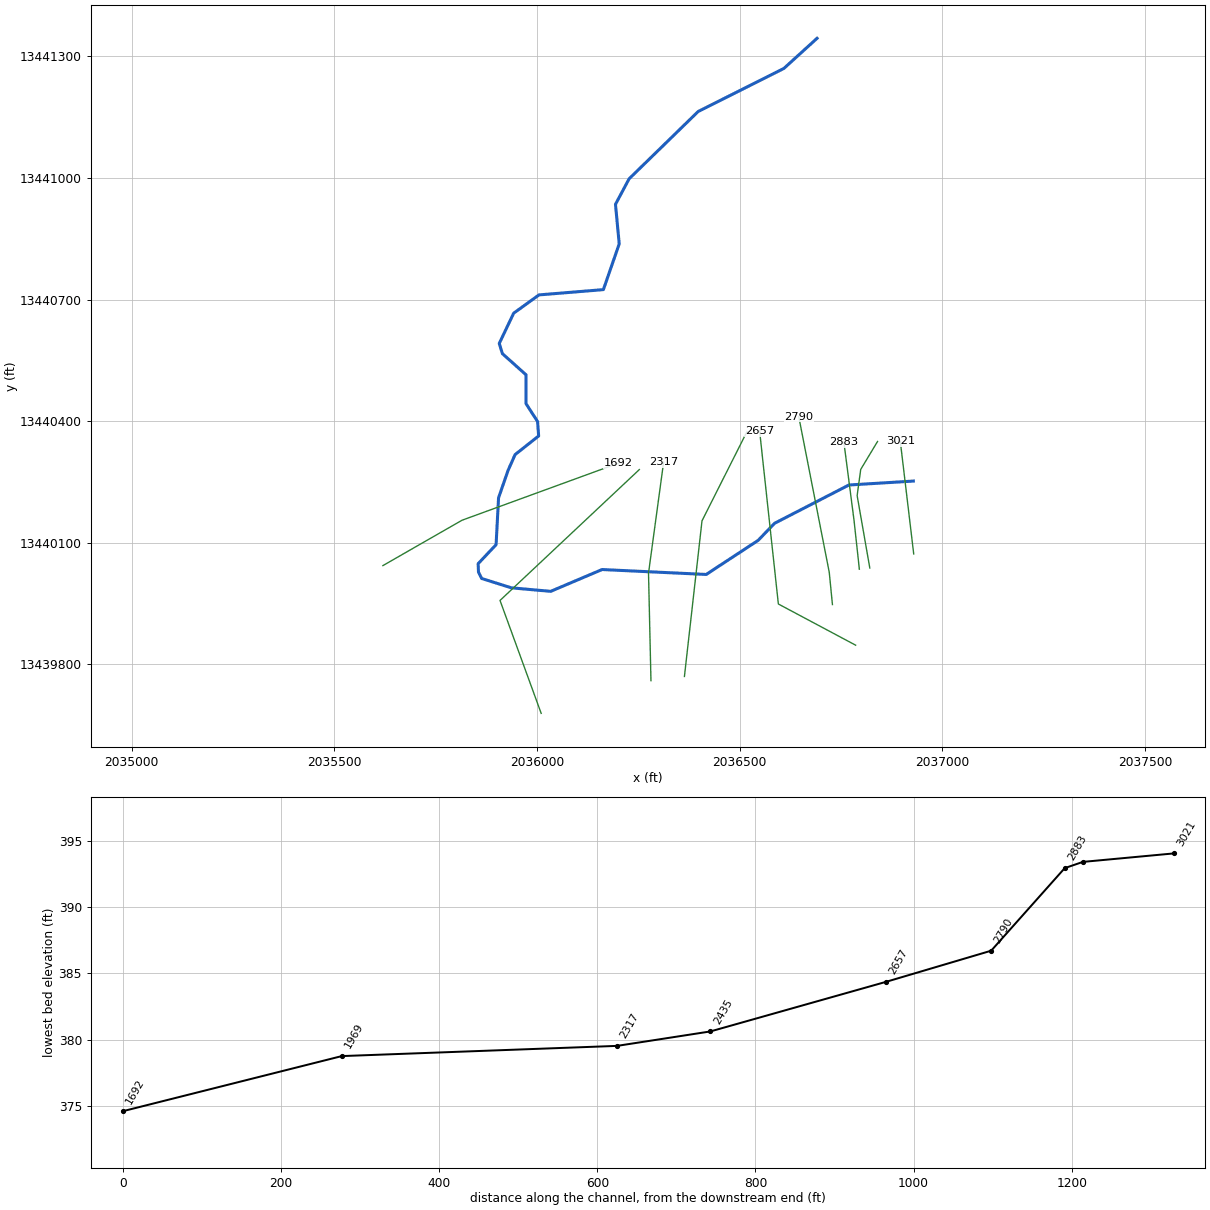
--- UNT 091 in RCW.prj (project) ---

Proj Title=UNT 091 in RCW Base Level Engineering
Current Plan=p01
Default Exp/Contr=0.3,0.1
English Units
Geom File=g01
Flow File=f01
Plan File=p01
BEGIN DESCRIPTION:
UNT 091 in RCW
END DESCRIPTION:

--- UNT 091 in RCW.p01 (plan) ---

Plan Title=Multiple Run
Short Identifier=Multiple
Geom File=g01
Flow File=f01
Subcritical Flow
K Sum by GR= 0
Std Step Tol= 0.01
Critical Tol= 0.01
Num of Std Step Trials= 20
Max Error Tol= 0.3
Flow Tol Ratio= 0.001
Split Flow NTrial= 30
Split Flow Tol= 0.02
Split Flow Ratio= 0.02
Log Output Level= 0
Friction Slope Method= 1
Unsteady Friction Slope Method= 2
Unsteady Bridges Friction Slope Method= 1
Parabolic Critical Depth
Global Vel Dist=  1 , 1 , 1
Global Log Level= 0
CheckData=True
Encroach Param= -1, 0, 0, 0
BEGIN DESCRIPTION:
Multiple Run
END DESCRIPTION:

--- UNT 091 in RCW.f01 (steady flow) ---

Flow Title=Multiple
Number of Profiles=7
Profile Names=10-year,25-year,50-year,1pct_min,100-year,1pct_plu,500-year
River Rch & RM= UNT 091 in RCW,Reach-1,3021
      56      71      83      48      96     192     132
Boundary for River Rch & Prof#=UNT 091 in RCW,Reach-1,1
Up Type=0
Dn Type=3
Dn Slope=0.005
Boundary for River Rch & Prof#=UNT 091 in RCW,Reach-1,2
Up Type=0
Dn Type=3
Dn Slope=0.005
Boundary for River Rch & Prof#=UNT 091 in RCW,Reach-1,3
Up Type=0
Dn Type=3
Dn Slope=0.005
Boundary for River Rch & Prof#=UNT 091 in RCW,Reach-1,4
Up Type=0
Dn Type=3
Dn Slope=0.005
Boundary for River Rch & Prof#=UNT 091 in RCW,Reach-1,5
Up Type=0
Dn Type=3
Dn Slope=0.005
Boundary for River Rch & Prof#=UNT 091 in RCW,Reach-1,6
Up Type=0
Dn Type=3
Dn Slope=0.005
Boundary for River Rch & Prof#=UNT 091 in RCW,Reach-1,7
Up Type=0
Dn Type=3
Dn Slope=0.005

--- UNT 091 in RCW.g01 (geometry) ---

Geom Title=Existing Conditions

River Reach=UNT 091 in RCW,Reach-1
Reach XY= 30
      2036928.44     13440252.17      2036769.41     13440242.45
      2036586.08     13440148.00      2036545.45     13440105.81
      2036417.35     13440021.75      2036160.40     13440033.90
      2036033.67     13439980.08      2035936.44     13439988.76
      2035863.30     13440011.85      2035855.48     13440027.48
      2035854.62     13440048.31      2035898.89     13440095.18
      2035904.96     13440210.64      2035928.40     13440278.34
      2035945.76     13440317.41      2036003.92     13440363.41
      2036001.32     13440399.00      2035972.67     13440443.27
      2035972.67     13440514.46      2035914.51     13440566.54
      2035906.70     13440591.71      2035942.29     13440666.36
      2036004.79     13440711.50      2036163.64     13440724.52
      2036202.71     13440837.37      2036193.48     13440935.01
      2036227.11     13440997.94      2036397.47     13441163.96
      2036609.06     13441270.29      2036690.80     13441344.54

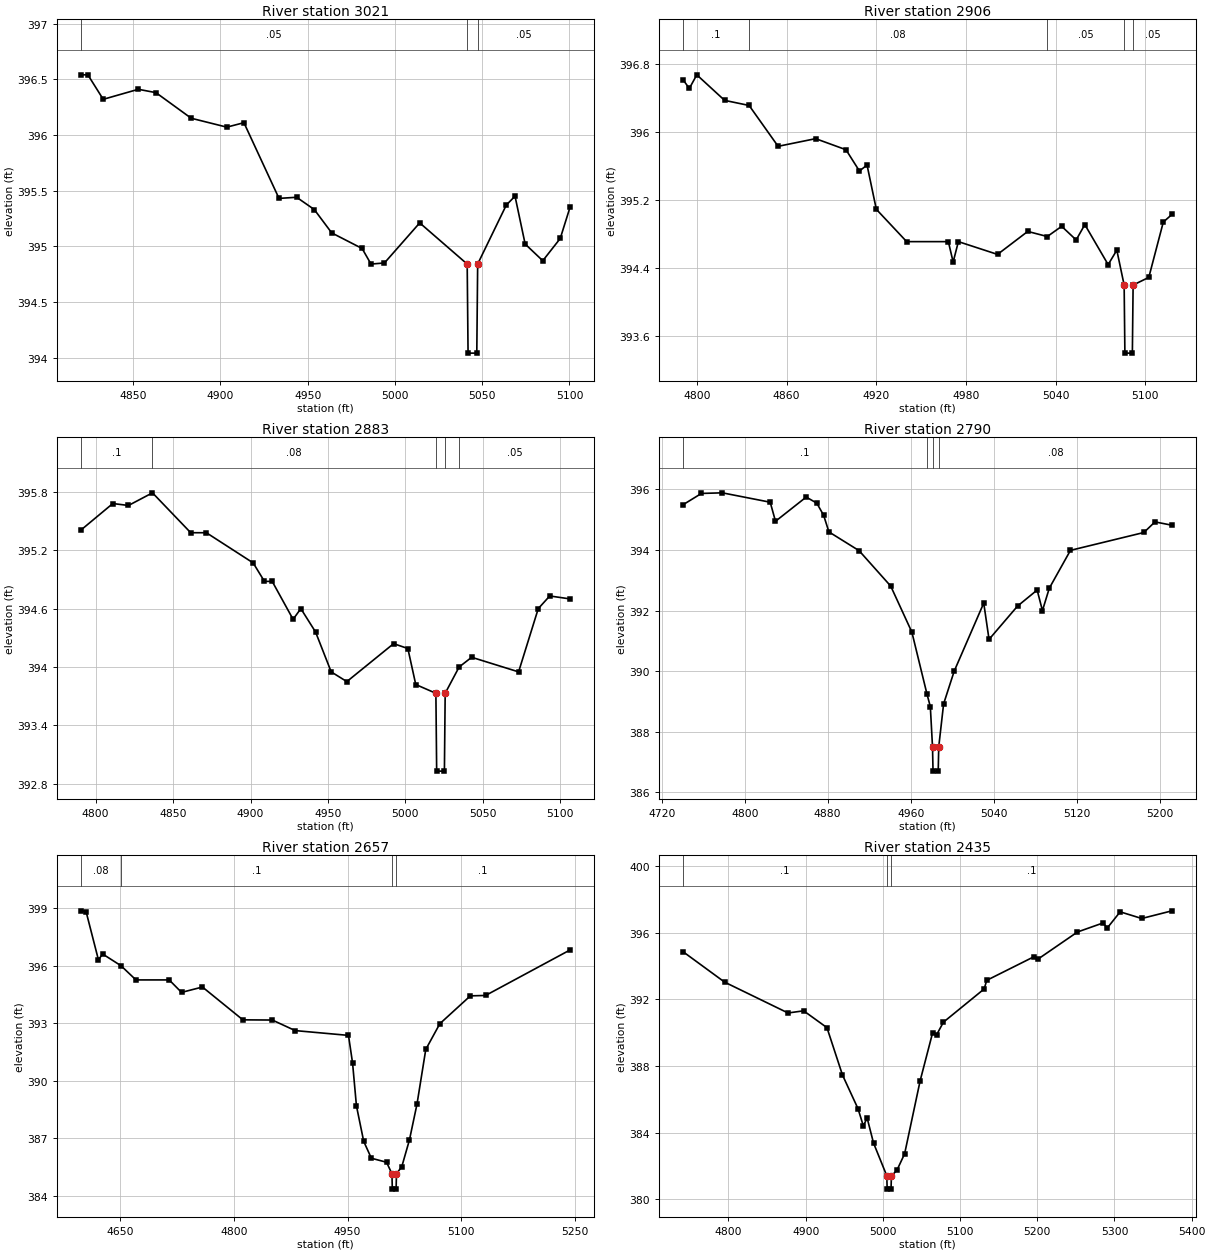
Type RM Length L Ch R = 1,3021,115,115,115
BEGIN DESCRIPTION:
UNT 091 in RCW 6.0
END DESCRIPTION:
XS GIS Cut Line= 2
      2036929.31     13440072.48      2036896.19     13440350.52
#Sta/Elev= 26
  4820.3  396.54  4824.1  396.54  4832.9  396.32  4853.0  396.41  4863.1  396.38
  4883.3  396.15  4903.7  396.07  4913.5  396.11  4933.6  395.43  4943.7  395.44
  4953.8  395.33  4963.8  395.12  4981.2  394.98  4986.3  394.84  4994.0  394.85
  5014.2  395.21  5041.4  394.84  5041.9  394.04  5046.9  394.04  5047.4  394.84
  5063.8  395.37  5068.8  395.45  5074.6  395.02  5084.7  394.87  5094.7  395.07
  5100.3  395.35
#Mann=3,-1,0
  4820.3    0.05       0  5041.4    0.03       0  5047.4    0.05       0
Bank Sta=5041.4,5047.4
Exp/Cntr=0.3,0.1

Type RM Length L Ch R = 1,2906,23,23,23
BEGIN DESCRIPTION:
Mapping XS 738eb749
END DESCRIPTION:
XS GIS Cut Line= 4
      2036820.99     13440037.69      2036789.74     13440216.33
      2036798.60     13440280.91      2036840.07     13440349.86
#Sta/Elev= 30
  4790.8  396.61  4794.9  396.51  4799.9  396.67  4818.5  396.37  4834.9  396.31
  4854.3  395.83  4879.4  395.92  4899.7  395.79  4908.7  395.54  4913.8  395.61
  4920.0  395.09  4940.3  394.71  4968.2  394.71  4971.4  394.47  4974.9  394.71
  5001.1  394.56  5021.3  394.83  5034.4  394.77  5044.0  394.89  5053.7  394.73
  5059.5  394.91  5075.1  394.44  5080.9  394.61  5085.8  394.20  5086.3  393.40
  5091.3  393.40  5091.8  394.20  5102.3  394.29  5112.0  394.94  5117.8  395.03
#Mann=5,-1,0
  4790.8     0.1       0  4834.9    0.08       0  5034.4    0.05       0
  5085.8    0.07       0  5091.8    0.05       0
Bank Sta=5085.8,5091.8
Exp/Cntr=0.3,0.1

Type RM Length L Ch R = 1,2883,93,93,93
BEGIN DESCRIPTION:
Mapping XS 274ba37f
END DESCRIPTION:
XS GIS Cut Line= 3
      2036795.20     13440034.67      2036782.17     13440154.51
      2036757.06     13440347.94
#Sta/Elev= 27
  4790.7  395.41  4811.1  395.68  4821.2  395.66  4836.7  395.79  4861.4  395.38
  4871.5  395.38  4901.7  395.07  4909.0  394.88  4914.0  394.88  4927.5  394.49
  4932.5  394.60  4942.0  394.36  4952.1  393.95  4962.2  393.85  4992.4  394.24
  5001.6  394.19  5006.7  393.82  5019.7  393.73  5020.2  392.93  5025.2  392.93
  5025.7  393.73  5034.7  394.00  5042.8  394.10  5073.1  393.95  5085.8  394.60
  5093.2  394.73  5106.3  394.70
#Mann=5,-1,0
  4790.7     0.1       0  4836.7    0.08       0  5019.7    0.07       0
  5025.7    0.08       0  5034.7    0.05       0
Bank Sta=5019.7,5025.7
Exp/Cntr=0.3,0.1

Type RM Length L Ch R = 1,2790,133,133,133
BEGIN DESCRIPTION:
Mapping XS 15d66850
END DESCRIPTION:
XS GIS Cut Line= 3
      2036728.78     13439947.50      2036720.97     13440026.91
      2036645.69     13440411.11
#Sta/Elev= 30
  4740.7  395.50  4758.3  395.87  4778.4  395.89  4824.6  395.58  4829.7  394.95
  4859.3  395.75  4869.5  395.55  4876.1  395.15  4881.2  394.60  4910.3  393.98
  4940.8  392.81  4961.2  391.29  4975.8  389.24  4979.0  388.83  4981.1  387.50
  4981.6  386.70  4986.6  386.70  4987.1  387.50  4991.8  388.92  5002.0  390.00
  5030.5  392.25  5035.6  391.05  5063.1  392.15  5082.0  392.68  5087.1  392.00
  5093.7  392.74  5114.1  393.99  5184.9  394.58  5195.6  394.93  5212.0  394.82
#Mann=4,-1,0
  4740.7     0.1       0  4975.8    0.08       0  4981.1    0.07       0
  4987.1    0.08       0
Bank Sta=4981.1,4987.1
Exp/Cntr=0.3,0.1

Type RM Length L Ch R = 1,2657,222,222,222
BEGIN DESCRIPTION:
Mapping XS 9777cfc7
END DESCRIPTION:
XS GIS Cut Line= 3
      2036786.07     13439847.23      2036595.38     13439948.86
      2036549.10     13440375.88
#Sta/Elev= 30
  4598.2  398.85  4604.6  398.81  4620.9  396.30  4626.5  396.60  4650.7  395.99
  4670.5  395.25  4714.4  395.25  4730.7  394.60  4758.3  394.88  4811.7  393.17
  4850.6  393.16  4880.8  392.61  4951.2  392.36  4956.6  390.92  4961.7  388.69
  4971.3  386.84  4981.4  385.96  5001.5  385.75  5008.6  385.15  5009.1  384.35
  5014.1  384.35  5014.6  385.15  5021.6  385.52  5031.7  386.91  5041.7  388.78
  5053.3  391.63  5071.9  392.97  5112.2  394.42  5132.3  394.44  5243.8  396.81
#Mann=4,-1,0
  4598.2    0.08       0  4650.7     0.1       0  5008.6    0.07       0
  5014.6     0.1       0
Bank Sta=5008.6,5014.6
Exp/Cntr=0.3,0.1

Type RM Length L Ch R = 1,2435,118,118,118
BEGIN DESCRIPTION:
Mapping XS 6161802c
END DESCRIPTION:
XS GIS Cut Line= 3
      2036363.59     13439770.02      2036407.00     13440154.13
      2036517.99     13440374.27
#Sta/Elev= 30
  4741.4  394.85  4795.1  393.03  4877.2  391.18  4897.4  391.31  4927.6  390.30
  4947.7  387.46  4967.8  385.44  4974.7  384.41  4979.7  384.87  4987.9  383.38
  5005.1  381.41  5005.6  380.61  5010.6  380.61  5011.1  381.41  5018.1  381.73
  5028.2  382.73  5048.3  387.11  5064.5  390.00  5069.6  389.87  5078.5  390.63
  5131.2  392.62  5134.6  393.14  5195.9  394.56  5201.5  394.43  5252.1  396.04
  5285.1  396.58  5290.7  396.28  5307.4  397.25  5335.3  396.85  5374.5  397.31
#Mann=3,-1,0
  4741.4     0.1       0  5005.1    0.07       0  5011.1     0.1       0
Bank Sta=5005.1,5011.1
Exp/Cntr=0.3,0.1

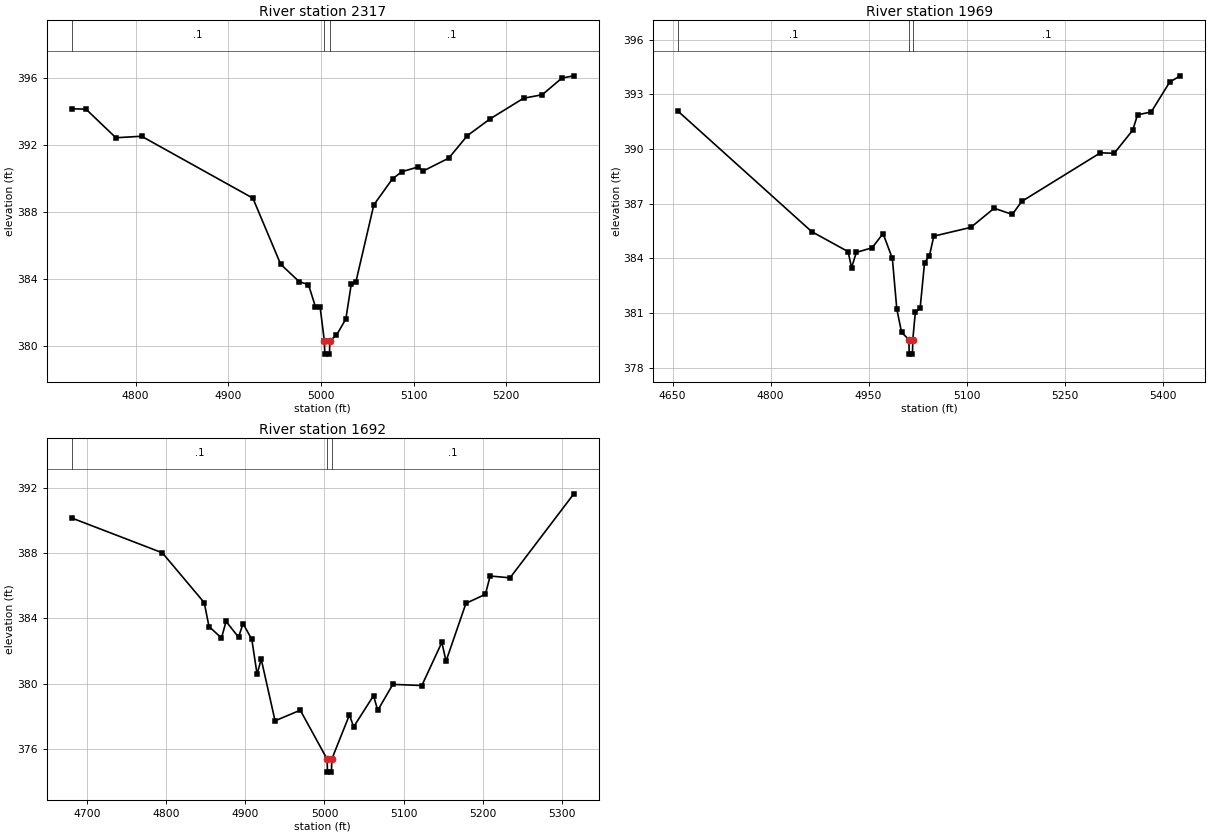
Type RM Length L Ch R = 1,2317,348,348,348
BEGIN DESCRIPTION:
UNT 091 in RCW 5.0
END DESCRIPTION:
XS GIS Cut Line= 3
      2036281.02     13439759.68      2036275.00     13440025.00
      2036312.27     13440298.78
#Sta/Elev= 30
  4731.2  394.18  4746.5  394.16  4778.8  392.45  4806.5  392.54  4926.6  388.84
  4956.6  384.89  4976.6  383.85  4986.6  383.67  4994.1  382.35  4999.1  382.35
  5003.7  380.32  5004.2  379.52  5009.2  379.52  5009.7  380.32  5016.8  380.65
  5026.9  381.62  5032.8  383.72  5037.8  383.85  5057.1  388.44  5077.3  390.00
  5087.4  390.42  5105.2  390.71  5110.2  390.46  5137.9  391.23  5158.1  392.58
  5182.6  393.58  5218.6  394.81  5238.8  395.02  5260.1  396.02  5272.9  396.15
#Mann=3,-1,0
  4731.2     0.1       0  5003.7    0.07       0  5009.7     0.1       0
Bank Sta=5003.7,5009.7
Exp/Cntr=0.3,0.1

Type RM Length L Ch R = 1,1969,277,277,277
BEGIN DESCRIPTION:
Mapping XS c1fceb4c
END DESCRIPTION:
XS GIS Cut Line= 3
      2036010.17     13439678.99      2035908.62     13439957.61
      2036252.38     13440280.54
#Sta/Elev= 30
  4658.7  392.06  4862.8  385.47  4918.6  384.37  4923.9  383.49  4931.2  384.33
  4955.3  384.58  4972.1  385.36  4986.3  384.00  4993.1  381.23  5000.4  379.94
  5011.6  379.55  5012.1  378.75  5017.1  378.75  5017.6  379.55  5021.5  381.06
  5028.8  381.26  5035.6  383.77  5042.9  384.13  5049.8  385.22  5106.4  385.70
  5142.1  386.75  5169.9  386.41  5184.1  387.12  5304.7  389.79  5325.7  389.76
  5354.1  391.03  5361.4  391.87  5382.4  392.03  5410.7  393.67  5426.9  394.01
#Mann=3,-1,0
  4658.7     0.1       0  5011.6    0.07       0  5017.6     0.1       0
Bank Sta=5011.6,5017.6
Exp/Cntr=0.3,0.1

Type RM Length L Ch R = 1,1692,0,0,0
BEGIN DESCRIPTION:
UNT 091 in RCW 4.0
END DESCRIPTION:
XS GIS Cut Line= 3
      2035619.58     13440043.56      2035814.87     13440155.53
      2036200.12     13440296.09
#Sta/Elev= 30
  4680.3  390.14  4794.9  388.01  4847.9  384.96  4853.9  383.50  4869.7  382.80
  4875.5  383.81  4891.3  382.85  4897.0  383.68  4908.1  382.71  4914.7  380.59
  4920.0  381.50  4937.5  377.73  4969.4  378.38  5003.3  375.39  5003.8  374.59
  5008.8  374.59  5009.3  375.39  5031.6  378.09  5036.9  377.36  5062.1  379.27
  5067.4  378.37  5086.5  379.96  5123.2  379.89  5148.5  382.53  5153.8  381.38
  5179.0  384.92  5203.6  385.47  5209.6  386.59  5234.8  386.48  5315.5  391.62
#Mann=3,-1,0
  4680.3     0.1       0  5003.3    0.07       0  5009.3     0.1       0
Bank Sta=5003.3,5009.3
Exp/Cntr=0.3,0.1

Chan Stop Cuts=-1