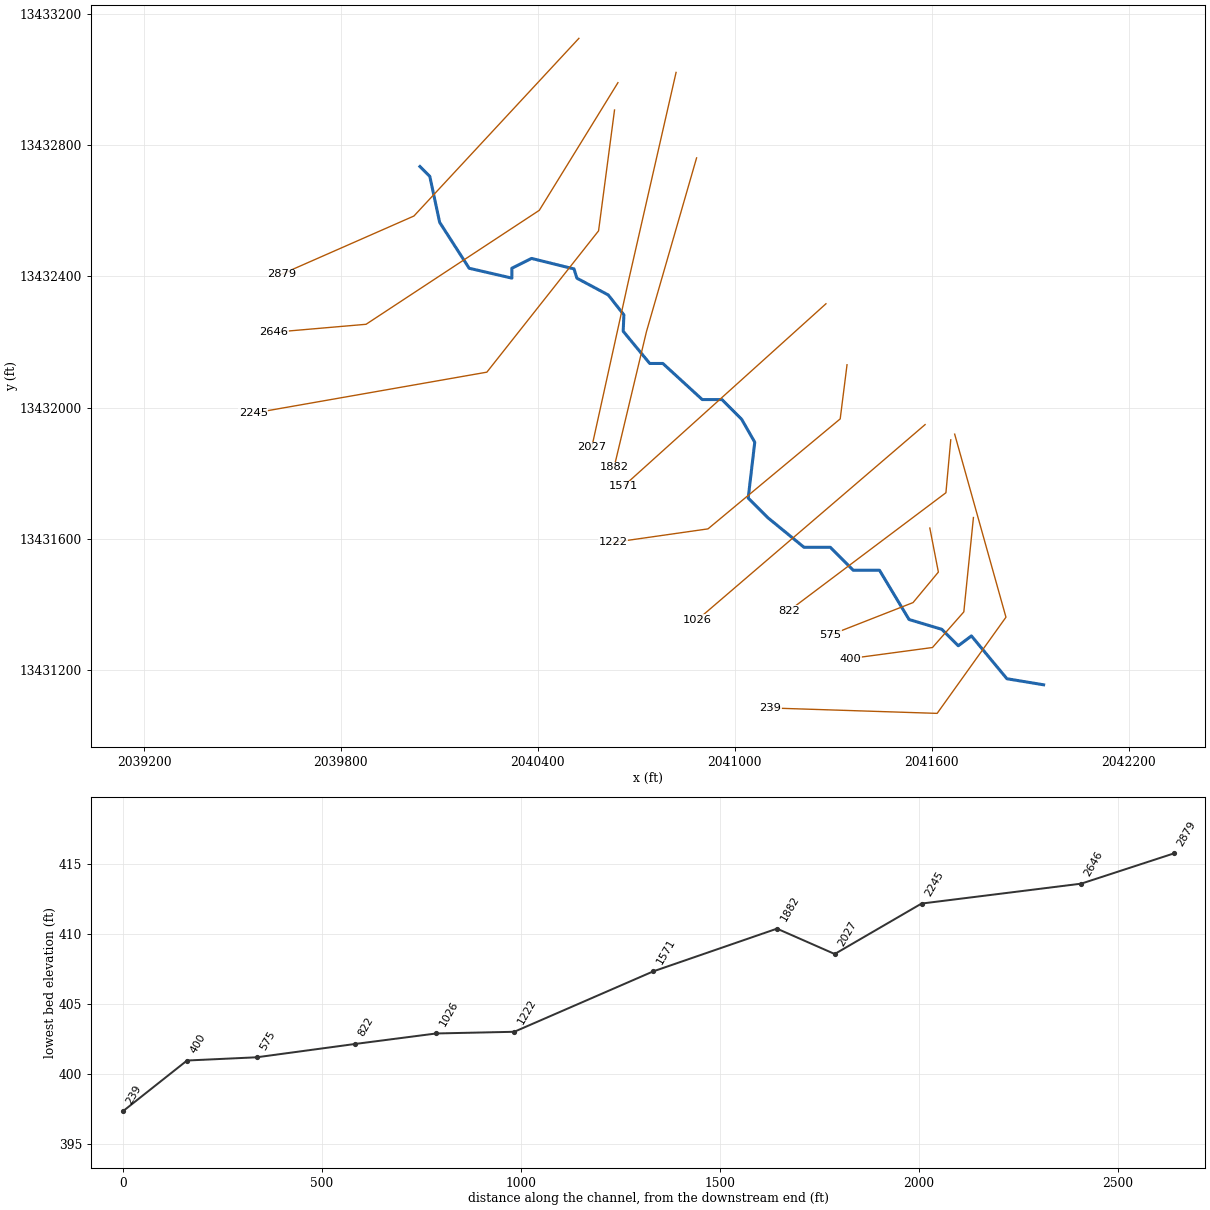
--- UNT 092 in RCW.prj (project) ---

Proj Title=UNT 092 in RCW Base Level Engineering
Current Plan=p01
Default Exp/Contr=0.3,0.1
English Units
Geom File=g01
Flow File=f01
Plan File=p01
BEGIN DESCRIPTION:
UNT 092 in RCW
END DESCRIPTION:

--- UNT 092 in RCW.p01 (plan) ---

Plan Title=Multiple Run
Short Identifier=Multiple
Geom File=g01
Flow File=f01
Subcritical Flow
K Sum by GR= 0
Std Step Tol= 0.01
Critical Tol= 0.01
Num of Std Step Trials= 20
Max Error Tol= 0.3
Flow Tol Ratio= 0.001
Split Flow NTrial= 30
Split Flow Tol= 0.02
Split Flow Ratio= 0.02
Log Output Level= 0
Friction Slope Method= 1
Unsteady Friction Slope Method= 2
Unsteady Bridges Friction Slope Method= 1
Parabolic Critical Depth
Global Vel Dist=  1 , 1 , 1
Global Log Level= 0
CheckData=True
Encroach Param= -1, 0, 0, 0
BEGIN DESCRIPTION:
Multiple Run
END DESCRIPTION:

--- UNT 092 in RCW.f01 (steady flow) ---

Flow Title=Multiple
Number of Profiles=7
Profile Names=10-year,25-year,50-year,1pct_min,100-year,1pct_plu,500-year
River Rch & RM= UNT 092 in RCW,Reach-1,2879
     104     138     165      98     196     391     282
Boundary for River Rch & Prof#=UNT 092 in RCW,Reach-1,1
Up Type=0
Dn Type=3
Dn Slope=0.005
Boundary for River Rch & Prof#=UNT 092 in RCW,Reach-1,2
Up Type=0
Dn Type=3
Dn Slope=0.005
Boundary for River Rch & Prof#=UNT 092 in RCW,Reach-1,3
Up Type=0
Dn Type=3
Dn Slope=0.005
Boundary for River Rch & Prof#=UNT 092 in RCW,Reach-1,4
Up Type=0
Dn Type=3
Dn Slope=0.005
Boundary for River Rch & Prof#=UNT 092 in RCW,Reach-1,5
Up Type=0
Dn Type=3
Dn Slope=0.005
Boundary for River Rch & Prof#=UNT 092 in RCW,Reach-1,6
Up Type=0
Dn Type=3
Dn Slope=0.005
Boundary for River Rch & Prof#=UNT 092 in RCW,Reach-1,7
Up Type=0
Dn Type=3
Dn Slope=0.005

--- UNT 092 in RCW.g01 (geometry) ---

Geom Title=Existing Conditions

River Reach=UNT 092 in RCW,Reach-1
Reach XY= 30
      2040040.80     13432734.54      2040070.80     13432704.54
      2040100.80     13432564.54      2040190.80     13432424.54
      2040320.80     13432394.54      2040320.80     13432424.54
      2040380.80     13432454.54      2040510.21     13432422.53
      2040518.90     13432394.32      2040614.38     13432343.32
      2040662.12     13432282.56      2040659.95     13432232.65
      2040740.80     13432134.54      2040780.80     13432134.54
      2040900.80     13432024.54      2040960.80     13432024.54
      2041020.80     13431964.54      2041060.80     13431894.54
      2041040.80     13431724.54      2041100.80     13431664.54
      2041210.80     13431574.54      2041290.80     13431574.54
      2041360.80     13431504.54      2041440.80     13431504.54
      2041530.80     13431354.54      2041630.80     13431324.54
      2041680.80     13431274.54      2041720.80     13431304.54
      2041828.97     13431174.04      2041940.80     13431155.60

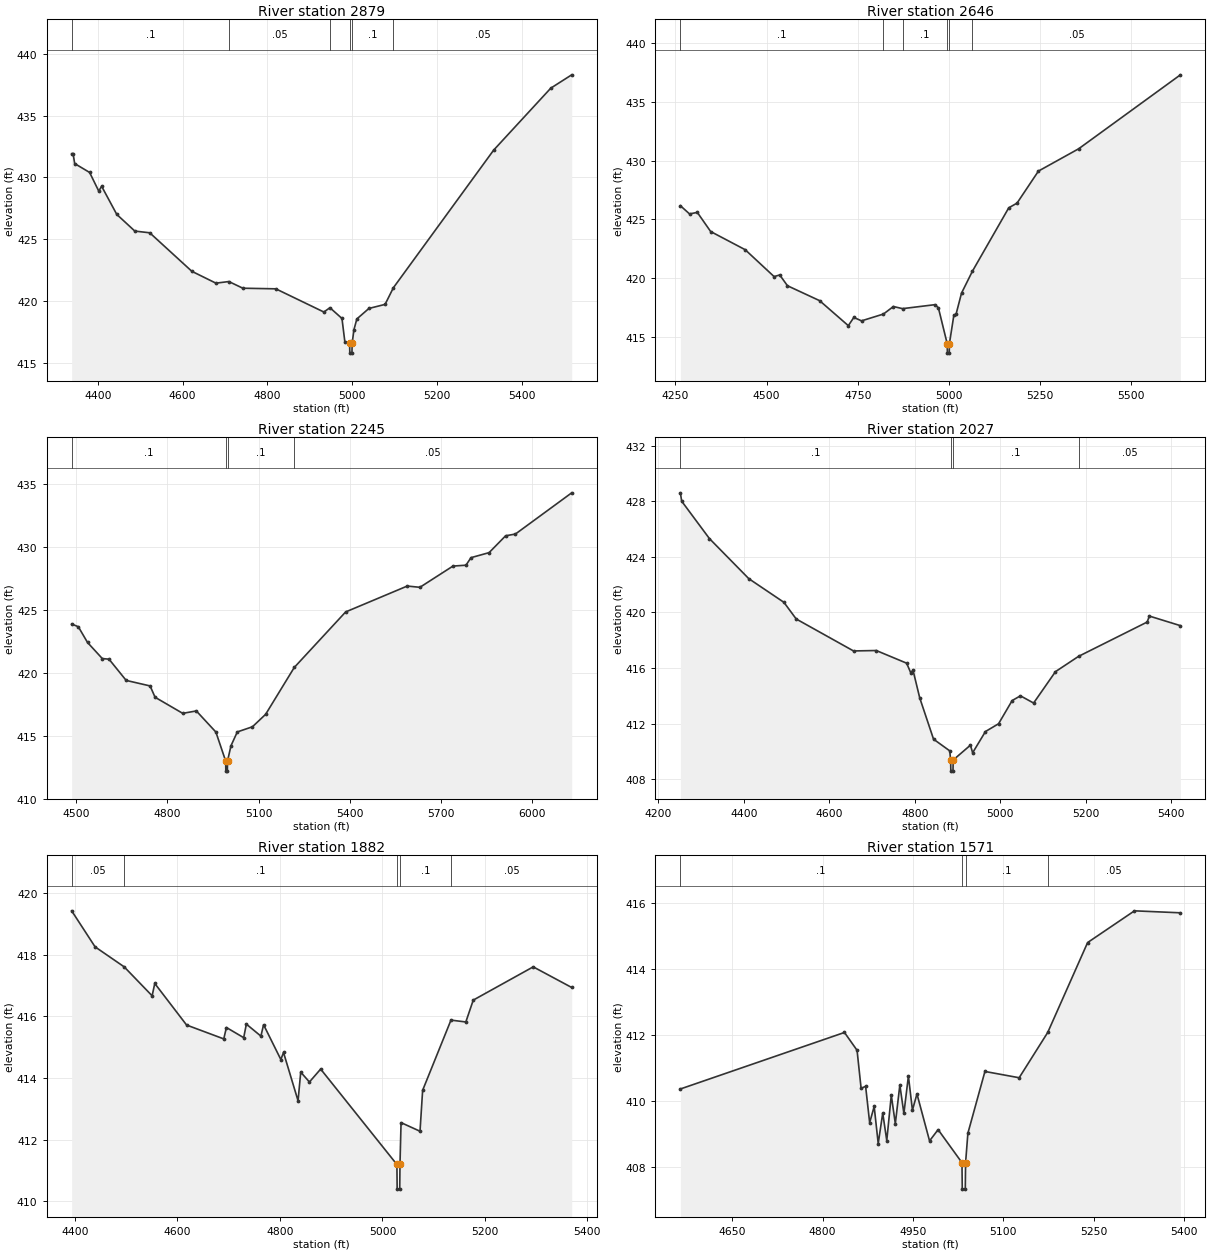
Type RM Length L Ch R = 1,2879,233,233,233
BEGIN DESCRIPTION:
UNT 092 in RCW 4.0
END DESCRIPTION:
XS GIS Cut Line= 3
      2040525.03     13433125.03      2040022.46     13432583.73
      2039619.88     13432406.74
#Sta/Elev= 30
  4338.6  431.92  4342.0  431.92  4345.7  431.12  4380.9  430.40  4402.4  428.89
  4409.2  429.28  4444.9  427.00  4487.4  425.65  4522.6  425.51  4621.8  422.39
  4678.5  421.43  4709.0  421.56  4742.0  421.02  4819.7  420.97  4933.0  419.09
  4947.2  419.44  4975.6  418.57  4982.4  416.68  4993.6  416.56  4994.1  415.76
  4999.1  415.76  4999.6  416.56  5003.9  417.67  5010.7  418.53  5039.1  419.38
  5077.2  419.71  5096.8  421.06  5333.1  432.21  5467.7  437.23  5517.0  438.31
#Mann=6,-1,0
  4338.6     0.1       0  4709.0    0.05       0  4947.2     0.1       0
  4993.6    0.07       0  4999.6     0.1       0  5096.8    0.05       0
Bank Sta=4993.6,4999.6
Exp/Cntr=0.3,0.1

Type RM Length L Ch R = 1,2646,401,401,401
BEGIN DESCRIPTION:
Mapping XS c552d307
END DESCRIPTION:
XS GIS Cut Line= 4
      2040643.99     13432989.99      2040404.40     13432601.10
      2039876.62     13432253.87      2039595.40     13432229.57
#Sta/Elev= 30
  4263.6  426.16  4288.7  425.46  4310.0  425.59  4346.6  423.96  4441.3  422.41
  4520.5  420.12  4535.9  420.26  4557.2  419.34  4645.3  418.07  4724.0  415.94
  4739.1  416.64  4760.2  416.35  4820.3  416.93  4847.5  417.57  4872.7  417.39
  4962.0  417.73  4971.0  417.45  4995.1  414.40  4995.6  413.60  5000.6  413.60
  5001.1  414.40  5013.2  416.81  5019.2  416.90  5034.3  418.71  5064.2  420.58
  5163.8  425.98  5186.5  426.38  5245.2  429.11  5355.5  431.01  5634.4  437.31
#Mann=6,-1,0
  4263.6     0.1       0  4820.3    0.05       0  4872.7     0.1       0
  4995.1    0.07       0  5001.1     0.1       0  5064.2    0.05       0
Bank Sta=4995.1,5001.1
Exp/Cntr=0.3,0.1

Type RM Length L Ch R = 1,2245,218,218,218
BEGIN DESCRIPTION:
Mapping XS b732893d
END DESCRIPTION:
XS GIS Cut Line= 4
      2040633.57     13432906.68      2040584.96     13432538.60
      2040244.68     13432108.04      2039532.84     13431983.03
#Sta/Elev= 30
  4486.1  423.89  4508.0  423.67  4538.2  422.42  4586.7  421.14  4608.8  421.09
  4665.2  419.40  4743.8  418.96  4760.1  418.06  4850.9  416.78  4895.7  416.97
  4959.9  415.29  4992.1  412.98  4992.6  412.18  4997.6  412.18  4998.1  412.98
  5009.5  414.20  5030.3  415.30  5080.0  415.71  5123.3  416.70  5217.4  420.43
  5386.2  424.85  5588.6  426.91  5630.2  426.81  5738.8  428.50  5781.5  428.57
  5798.1  429.17  5857.5  429.57  5911.8  430.91  5944.0  431.05  6128.9  434.33
#Mann=4,-1,0
  4486.1     0.1       0  4992.1    0.07       0  4998.1     0.1       0
  5217.4    0.05       0
Bank Sta=4992.1,4998.1
Exp/Cntr=0.3,0.1

Type RM Length L Ch R = 1,2027,145,145,145
BEGIN DESCRIPTION:
UNT 092 in RCW 3.0
END DESCRIPTION:
XS GIS Cut Line= 3
      2040821.06     13433021.19      2040675.23     13432382.35
      2040564.25     13431879.43
#Sta/Elev= 30
  4251.6  428.61  4254.6  428.01  4319.5  425.32  4411.8  422.43  4493.9  420.73
  4522.7  419.53  4656.8  417.23  4710.1  417.26  4781.1  416.35  4790.9  415.65
  4796.0  415.85  4811.8  413.85  4844.1  410.88  4882.0  410.04  4884.1  409.38
  4884.6  408.58  4889.6  408.58  4890.1  409.38  4930.5  410.45  4935.6  409.90
  4965.6  411.43  4996.3  411.99  5028.1  413.66  5047.5  414.00  5078.3  413.48
  5129.5  415.74  5183.5  416.84  5344.1  419.31  5349.2  419.74  5421.9  419.05
#Mann=4,-1,0
  4251.6     0.1       0  4884.1    0.07       0  4890.1     0.1       0
  5183.5    0.05       0
Bank Sta=4884.1,4890.1
Exp/Cntr=0.3,0.1

Type RM Length L Ch R = 1,1882,311,311,311
BEGIN DESCRIPTION:
UNT 092 in RCW 2.0
END DESCRIPTION:
XS GIS Cut Line= 3
      2040883.56     13432760.79      2040730.79     13432231.30
      2040632.26     13431818.18
#Sta/Elev= 30
  4393.5  419.43  4439.2  418.26  4496.0  417.61  4550.5  416.67  4555.7  417.07
  4617.8  415.72  4690.3  415.27  4695.5  415.64  4729.2  415.31  4734.4  415.75
  4762.8  415.36  4768.0  415.73  4801.7  414.60  4806.9  414.83  4835.3  413.26
  4840.5  414.19  4857.5  413.87  4879.4  414.29  5028.2  411.19  5028.7  410.39
  5033.7  410.39  5034.2  411.19  5036.3  412.55  5073.3  412.27  5078.4  413.60
  5133.7  415.88  5162.7  415.82  5177.2  416.53  5294.2  417.61  5369.3  416.94
#Mann=5,-1,0
  4393.5    0.05       0  4496.0     0.1       0  5028.2    0.07       0
  5034.2     0.1       0  5133.7    0.05       0
Bank Sta=5028.2,5034.2
Exp/Cntr=0.3,0.1

Type RM Length L Ch R = 1,1571,349,349,349
BEGIN DESCRIPTION:
Mapping XS 7b1b899a
END DESCRIPTION:
XS GIS Cut Line= 2
      2041277.69     13432316.39      2040661.33     13431760.80
#Sta/Elev= 30
  4564.1  410.37  4836.4  412.08  4857.3  411.54  4864.0  410.39  4871.5  410.45
  4878.2  409.35  4885.7  409.84  4892.4  408.72  4899.9  409.64  4906.6  408.81
  4914.1  410.18  4920.8  409.32  4928.3  410.49  4935.0  409.63  4942.5  410.76
  4949.2  409.73  4956.7  410.22  4977.6  408.80  4991.8  409.14  5031.4  408.14
  5031.9  407.34  5036.9  407.34  5037.4  408.14  5041.2  409.03  5069.5  410.90
  5126.3  410.71  5173.7  412.08  5239.9  414.80  5317.7  415.76  5393.9  415.70
#Mann=4,-1,0
  4564.1     0.1       0  5031.4    0.07       0  5037.4     0.1       0
  5173.7    0.05       0
Bank Sta=5031.4,5037.4
Exp/Cntr=0.3,0.1

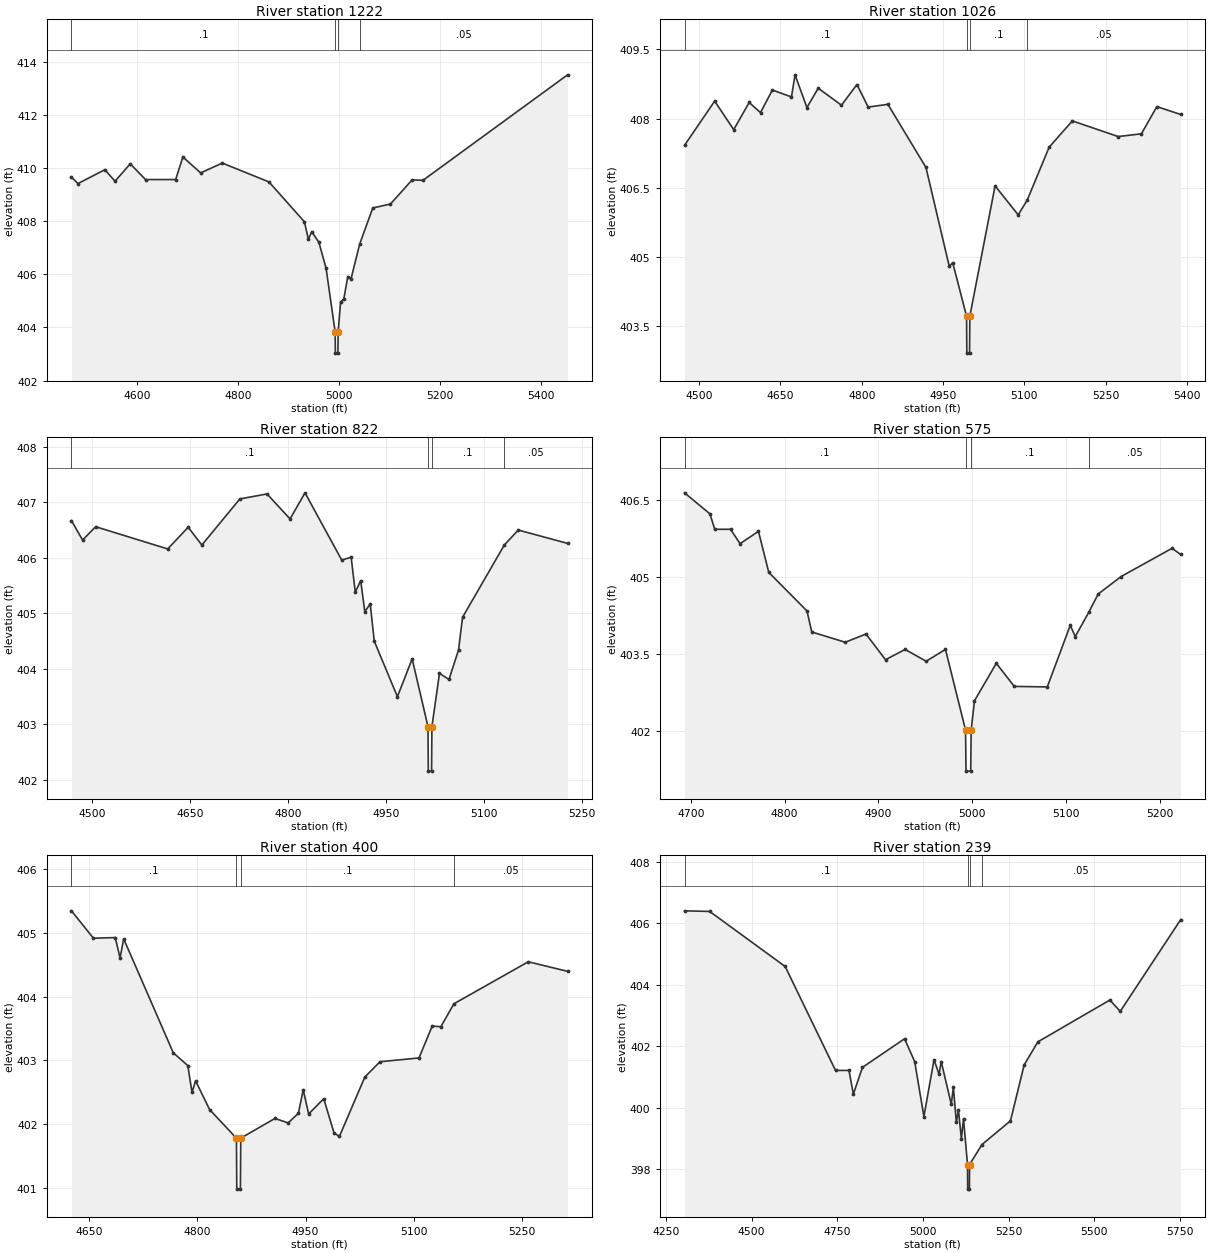
Type RM Length L Ch R = 1,1222,196,196,196
BEGIN DESCRIPTION:
Mapping XS beac3fc8
END DESCRIPTION:
XS GIS Cut Line= 4
      2041341.90     13432130.60      2041321.07     13431965.68
      2040918.29     13431630.61      2040628.29     13431589.18
#Sta/Elev= 30
  4469.2  409.65  4482.1  409.41  4535.3  409.93  4555.5  409.50  4585.7  410.15
  4616.0  409.56  4675.7  409.56  4690.0  410.41  4725.2  409.81  4768.1  410.18
  4860.6  409.47  4930.9  407.97  4938.7  407.31  4945.2  407.60  4959.5  407.20
  4973.8  406.22  4991.7  403.83  4992.2  403.03  4997.2  403.03  4997.7  403.83
  5002.5  404.95  5009.0  405.08  5016.8  405.91  5023.3  405.83  5040.3  407.13
  5066.3  408.49  5101.4  408.64  5144.4  409.55  5165.7  409.53  5452.3  413.50
#Mann=4,-1,0
  4469.2     0.1       0  4991.7    0.07       0  4997.7     0.1       0
  5040.3    0.05       0
Bank Sta=4991.7,4997.7
Exp/Cntr=0.3,0.1

Type RM Length L Ch R = 1,1026,204,204,204
BEGIN DESCRIPTION:
Mapping XS de1a3bb3
END DESCRIPTION:
XS GIS Cut Line= 2
      2041579.72     13431948.30      2040885.28     13431352.81
#Sta/Elev= 30
  4473.3  407.42  4528.9  408.38  4564.0  407.76  4592.5  408.35  4613.4  408.13
  4635.3  408.62  4670.5  408.47  4677.1  408.95  4699.0  408.24  4719.9  408.66
  4762.7  408.29  4791.2  408.74  4812.0  408.25  4848.3  408.31  4918.5  406.94
  4961.3  404.80  4967.9  404.87  4993.4  403.71  4993.9  402.91  4998.9  402.91
  4999.4  403.71  5046.0  406.54  5088.6  405.91  5105.2  406.23  5145.7  407.38
  5188.5  407.95  5273.0  407.61  5315.8  407.67  5344.3  408.26  5388.1  408.09
#Mann=4,-1,0
  4473.3     0.1       0  4993.4    0.07       0  4999.4     0.1       0
  5105.2    0.05       0
Bank Sta=4993.4,4999.4
Exp/Cntr=0.3,0.1

Type RM Length L Ch R = 1,822,247,247,247
BEGIN DESCRIPTION:
Mapping XS 70a97d2d
END DESCRIPTION:
XS GIS Cut Line= 3
      2041657.88     13431901.93      2041643.16     13431740.72
      2041164.51     13431380.87
#Sta/Elev= 30
  4467.8  406.67  4484.8  406.32  4504.9  406.56  4615.3  406.16  4646.8  406.55
  4667.7  406.23  4726.0  407.06  4767.6  407.15  4803.0  406.70  4825.9  407.17
  4882.2  405.96  4896.7  406.01  4903.0  405.38  4911.3  405.59  4917.6  405.03
  4925.9  405.17  4932.1  404.50  4967.6  403.50  4990.2  404.18  5014.5  402.96
  5015.0  402.16  5020.0  402.16  5020.5  402.96  5032.1  403.92  5046.7  403.81
  5061.3  404.34  5067.5  404.93  5131.5  406.23  5152.9  406.50  5228.5  406.26
#Mann=4,-1,0
  4467.8     0.1       0  5014.5    0.07       0  5020.5     0.1       0
  5131.5    0.05       0
Bank Sta=5014.5,5020.5
Exp/Cntr=0.3,0.1

Type RM Length L Ch R = 1,575,175,175,175
BEGIN DESCRIPTION:
Mapping XS a2ad0d61
END DESCRIPTION:
XS GIS Cut Line= 4
      2041594.15     13431633.11      2041620.19     13431499.00
      2041542.98     13431406.04      2041290.43     13431307.10
#Sta/Elev= 30
  4693.4  406.63  4720.5  406.22  4725.6  405.92  4742.4  405.92  4752.6  405.64
  4772.2  405.88  4783.2  405.08  4823.9  404.33  4829.0  403.92  4864.7  403.72
  4886.8  403.88  4907.6  403.38  4928.5  403.58  4950.9  403.35  4971.5  403.58
  4992.9  402.01  4993.4  401.21  4998.4  401.21  4998.9  402.01  5002.4  402.58
  5025.7  403.31  5044.8  402.86  5080.0  402.85  5104.5  404.05  5109.8  403.83
  5124.1  404.30  5134.3  404.66  5158.7  405.00  5213.0  405.55  5222.1  405.43
#Mann=4,-1,0
  4693.4     0.1       0  4992.9    0.07       0  4998.9     0.1       0
  5124.1    0.05       0
Bank Sta=4992.9,4998.9
Exp/Cntr=0.3,0.1

Type RM Length L Ch R = 1,400,161,161,161
BEGIN DESCRIPTION:
Mapping XS ec484362
END DESCRIPTION:
XS GIS Cut Line= 4
      2041726.99     13431665.25      2041697.69     13431377.71
      2041602.21     13431269.20      2041351.13     13431235.47
#Sta/Elev= 30
  4625.9  405.35  4656.3  404.92  4686.5  404.93  4693.2  404.61  4698.2  404.91
  4766.9  403.12  4787.0  402.92  4792.8  402.50  4797.8  402.68  4817.1  402.23
  4854.3  401.78  4854.8  400.98  4859.8  400.98  4860.3  401.78  4907.6  402.09
  4925.9  402.02  4940.1  402.17  4946.8  402.54  4954.3  402.16  4975.2  402.40
  4989.5  401.86  4997.0  401.81  5032.1  402.74  5053.0  402.98  5107.1  403.04
  5125.4  403.54  5137.4  403.53  5155.4  403.89  5258.4  404.55  5312.8  404.40
#Mann=4,-1,0
  4625.9     0.1       0  4854.3    0.07       0  4860.3     0.1       0
  5155.4    0.05       0
Bank Sta=4854.3,4860.3
Exp/Cntr=0.3,0.1

Type RM Length L Ch R = 1,239,0,0,0
BEGIN DESCRIPTION:
UNT 092 in RCW 1.0
END DESCRIPTION:
XS GIS Cut Line= 4
      2041669.80     13431919.25      2041826.06     13431361.51
      2041616.42     13431068.54      2041108.85     13431085.00
#Sta/Elev= 30
  4304.5  406.41  4377.9  406.39  4598.1  404.60  4745.0  401.22  4784.3  401.22
  4797.0  400.45  4823.6  401.32  4946.4  402.25  4975.9  401.51  5002.9  399.72
  5032.4  401.57  5047.1  401.09  5053.3  401.51  5082.7  400.12  5088.9  400.67
  5097.5  399.53  5103.6  399.94  5112.2  399.00  5118.4  399.65  5130.1  398.16
  5130.6  397.36  5135.6  397.36  5136.1  398.16  5172.3  398.81  5255.4  399.58
  5295.4  401.40  5335.4  402.15  5545.5  403.51  5575.6  403.14  5751.8  406.12
#Mann=4,-1,0
  4304.5     0.1       0  5130.1    0.07       0  5136.1     0.1       0
  5172.3    0.05       0
Bank Sta=5130.1,5136.1
Exp/Cntr=0.3,0.1

Chan Stop Cuts=-1