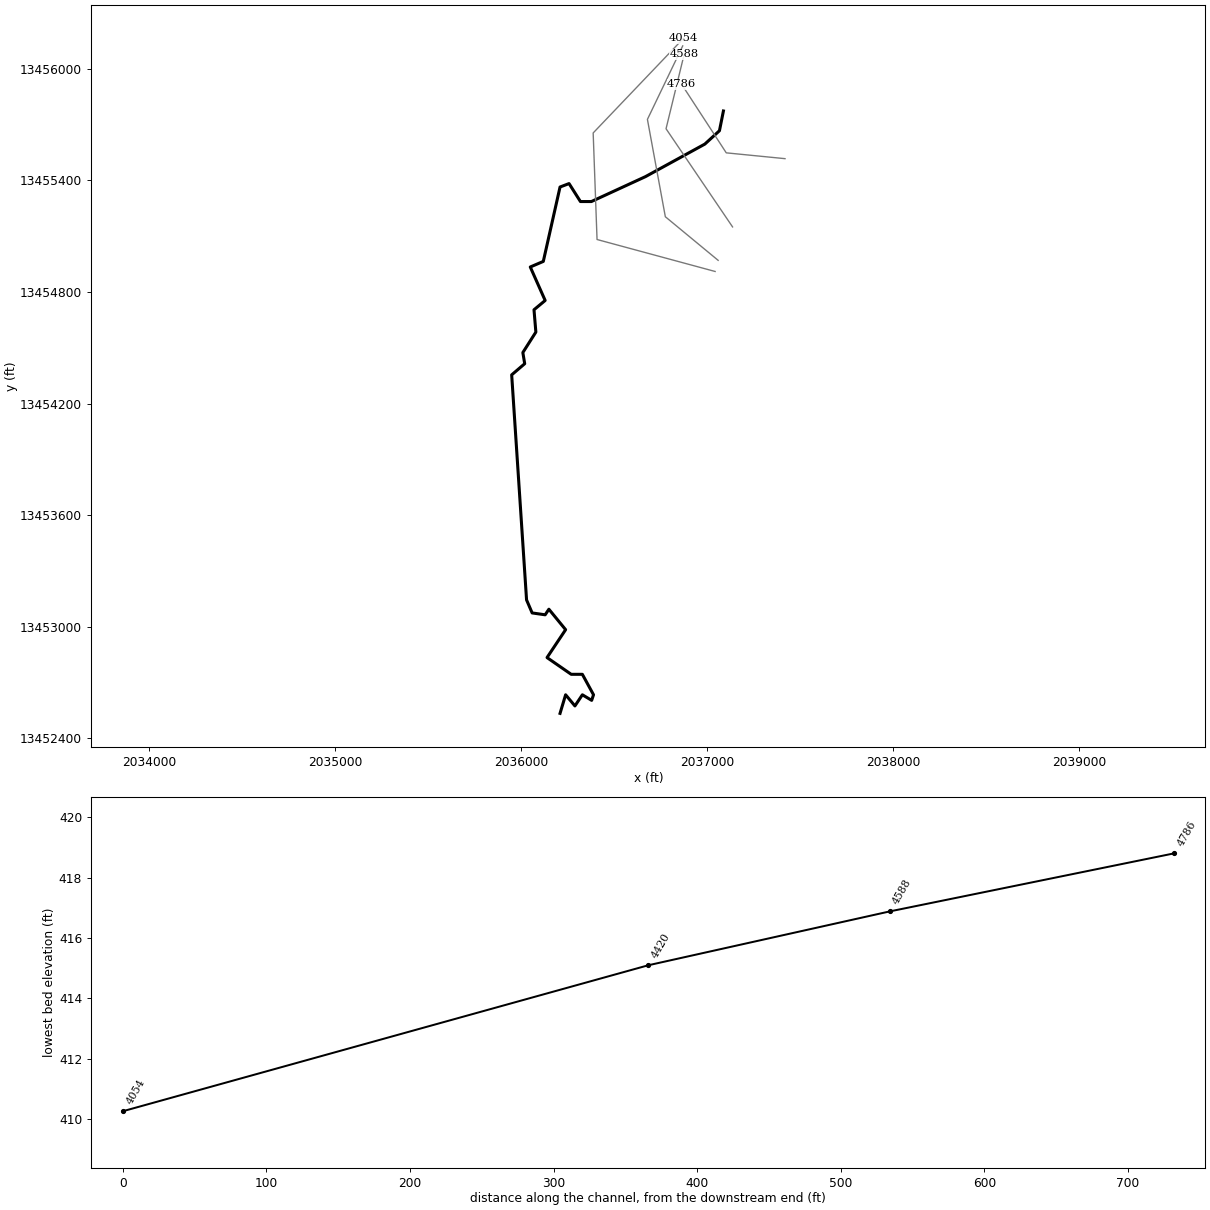
--- UNT 094 in RCW.prj (project) ---

Proj Title=UNT 094 in RCW Base Level Engineering
Current Plan=p01
Default Exp/Contr=0.3,0.1
English Units
Geom File=g01
Flow File=f01
Plan File=p01
BEGIN DESCRIPTION:
UNT 094 in RCW
END DESCRIPTION:

--- UNT 094 in RCW.p01 (plan) ---

Plan Title=Multiple Run
Short Identifier=Multiple
Geom File=g01
Flow File=f01
Subcritical Flow
K Sum by GR= 0
Std Step Tol= 0.01
Critical Tol= 0.01
Num of Std Step Trials= 20
Max Error Tol= 0.3
Flow Tol Ratio= 0.001
Split Flow NTrial= 30
Split Flow Tol= 0.02
Split Flow Ratio= 0.02
Log Output Level= 0
Friction Slope Method= 1
Unsteady Friction Slope Method= 2
Unsteady Bridges Friction Slope Method= 1
Parabolic Critical Depth
Global Vel Dist=  1 , 1 , 1
Global Log Level= 0
CheckData=True
Encroach Param= -1, 0, 0, 0
BEGIN DESCRIPTION:
Multiple Run
END DESCRIPTION:

--- UNT 094 in RCW.f01 (steady flow) ---

Flow Title=Multiple
Number of Profiles=7
Profile Names=10-year,25-year,50-year,1pct_min,100-year,1pct_plu,500-year
River Rch & RM= UNT 094 in RCW,Reach-1,4786
      66      84      98      58     115     230     159
River Rch & RM= UNT 094 in RCW,Reach-1,4054
     126     168     202     121     242     483     352
Boundary for River Rch & Prof#=UNT 094 in RCW,Reach-1,1
Up Type=0
Dn Type=3
Dn Slope=0.005
Boundary for River Rch & Prof#=UNT 094 in RCW,Reach-1,2
Up Type=0
Dn Type=3
Dn Slope=0.005
Boundary for River Rch & Prof#=UNT 094 in RCW,Reach-1,3
Up Type=0
Dn Type=3
Dn Slope=0.005
Boundary for River Rch & Prof#=UNT 094 in RCW,Reach-1,4
Up Type=0
Dn Type=3
Dn Slope=0.005
Boundary for River Rch & Prof#=UNT 094 in RCW,Reach-1,5
Up Type=0
Dn Type=3
Dn Slope=0.005
Boundary for River Rch & Prof#=UNT 094 in RCW,Reach-1,6
Up Type=0
Dn Type=3
Dn Slope=0.005
Boundary for River Rch & Prof#=UNT 094 in RCW,Reach-1,7
Up Type=0
Dn Type=3
Dn Slope=0.005

--- UNT 094 in RCW.g01 (geometry) ---

Geom Title=Existing Conditions

River Reach=UNT 094 in RCW,Reach-1
Reach XY= 30
      2037089.22     13455773.38      2037067.86     13455667.13
      2036989.22     13455595.25      2036669.95     13455420.25
      2036379.32     13455286.40      2036320.47     13455286.40
      2036259.27     13455383.01      2036210.80     13455364.54
      2036120.80     13454964.54      2036050.80     13454934.54
      2036130.80     13454754.54      2036070.80     13454704.54
      2036080.80     13454584.54      2036010.80     13454474.54
      2036020.80     13454414.54      2035950.80     13454354.54
      2036030.80     13453144.54      2036060.80     13453074.54
      2036130.80     13453064.54      2036150.80     13453094.54
      2036240.80     13452984.54      2036140.80     13452834.54
      2036270.80     13452744.54      2036330.80     13452744.54
      2036390.80     13452634.54      2036380.80     13452604.54
      2036330.80     13452634.54      2036290.80     13452574.54
      2036240.80     13452634.54      2036210.80     13452534.54

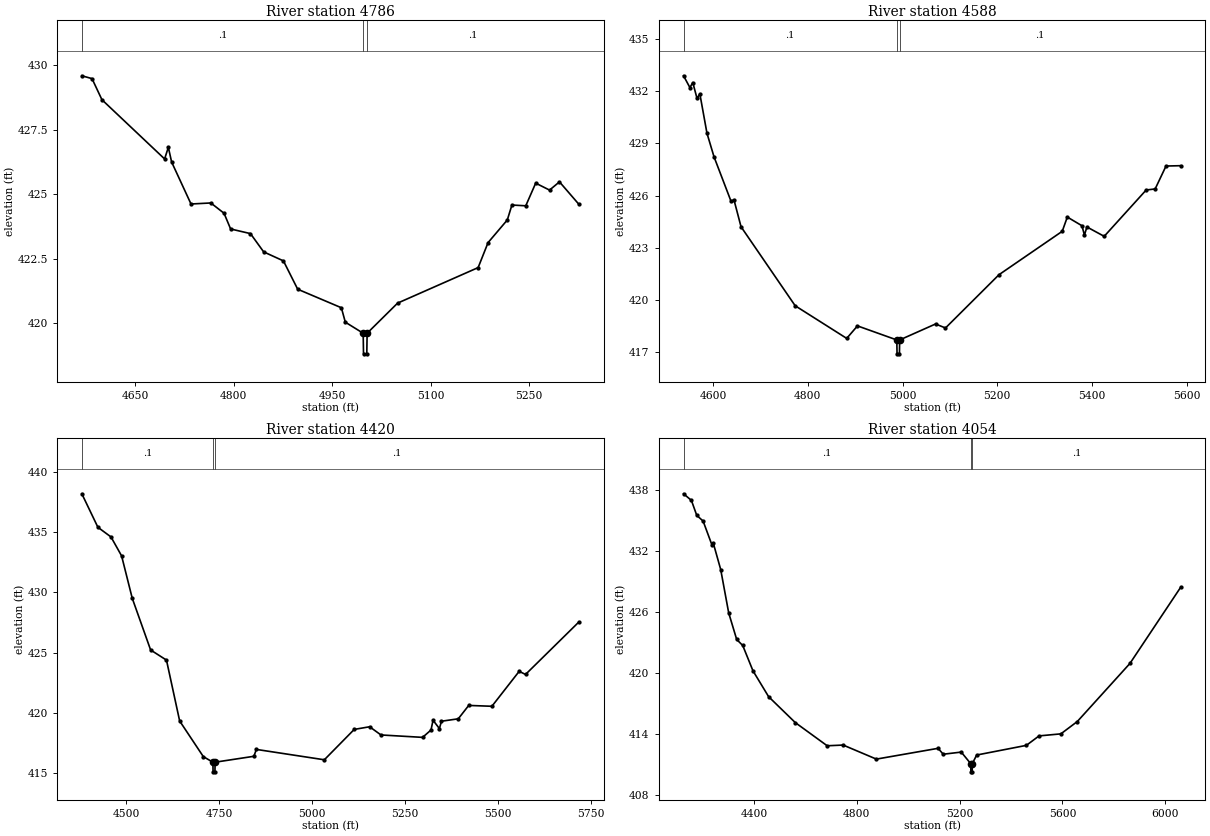
Type RM Length L Ch R = 1,4786,198,198,198
BEGIN DESCRIPTION:
UNT 094 in RCW 2.0
END DESCRIPTION:
XS GIS Cut Line= 3
      2037420.43     13455516.98      2037104.50     13455548.23
      2036864.94     13455916.25
#Sta/Elev= 30
  4569.1  429.60  4584.6  429.49  4599.7  428.67  4695.1  426.37  4700.8  426.82
  4705.8  426.25  4735.3  424.62  4765.5  424.66  4785.6  424.26  4795.6  423.65
  4825.8  423.47  4845.9  422.76  4876.0  422.41  4897.7  421.31  4964.2  420.59
  4970.2  420.03  4997.4  419.60  4997.9  418.80  5002.9  418.80  5003.4  419.60
  5049.8  420.77  5172.4  422.15  5187.5  423.12  5216.8  424.00  5223.8  424.58
  5244.9  424.55  5260.0  425.43  5281.1  425.16  5296.2  425.48  5325.7  424.61
#Mann=3,-1,0
  4569.1     0.1       0  4997.4    0.07       0  5003.4     0.1       0
Bank Sta=4997.4,5003.4
Exp/Cntr=0.3,0.1

Type RM Length L Ch R = 1,4588,168,168,168
BEGIN DESCRIPTION:
Mapping XS 788b4603
END DESCRIPTION:
XS GIS Cut Line= 3
      2037138.34     13455150.04      2036780.72     13455677.78
      2036877.95     13456077.11
#Sta/Elev= 30
  4538.1  432.90  4551.5  432.22  4557.6  432.51  4566.5  431.60  4572.5  431.86
  4587.5  429.59  4602.4  428.23  4638.4  425.66  4644.4  425.76  4659.4  424.20
  4773.6  419.65  4882.3  417.77  4905.0  418.49  4988.0  417.68  4988.5  416.88
  4993.5  416.88  4994.0  417.68  5069.7  418.60  5090.7  418.37  5203.6  421.44
  5337.0  423.94  5347.7  424.76  5378.6  424.26  5383.8  423.72  5389.0  424.19
  5425.5  423.65  5514.1  426.32  5533.0  426.38  5555.9  427.70  5586.6  427.72
#Mann=3,-1,0
  4538.1     0.1       0  4988.0    0.07       0  4994.0     0.1       0
Bank Sta=4988,4994
Exp/Cntr=0.3,0.1

Type RM Length L Ch R = 1,4420,366,366,366
BEGIN DESCRIPTION:
Mapping XS 66587b01
END DESCRIPTION:
XS GIS Cut Line= 4
      2037060.82     13454970.30      2036776.94     13455204.69
      2036680.59     13455728.13      2036870.35     13456123.26
#Sta/Elev= 30
  4379.8  438.17  4423.1  435.39  4458.3  434.59  4486.9  433.02  4515.6  429.50
  4565.1  425.21  4607.8  424.37  4643.3  419.32  4707.1  416.36  4732.8  415.90
  4733.3  415.10  4738.3  415.10  4738.8  415.90  4843.2  416.39  4849.9  416.96
  5033.0  416.10  5113.5  418.62  5155.0  418.84  5185.5  418.16  5297.6  417.96
  5320.3  418.57  5325.8  419.38  5342.9  418.69  5348.5  419.30  5393.7  419.50
  5421.9  420.61  5484.3  420.54  5557.8  423.44  5574.9  423.18  5718.5  427.53
#Mann=3,-1,0
  4379.8     0.1       0  4732.8    0.07       0  4738.8     0.1       0
Bank Sta=4732.8,4738.8
Exp/Cntr=0.3,0.1

Type RM Length L Ch R = 1,4054,0,0,0
BEGIN DESCRIPTION:
Mapping XS d9b030c0
END DESCRIPTION:
XS GIS Cut Line= 4
      2037044.58     13454910.43      2036409.76     13455082.30
      2036388.92     13455655.21      2036874.48     13456163.91
#Sta/Elev= 30
  4125.6  437.58  4156.2  436.93  4177.0  435.46  4201.7  434.90  4236.3  432.54
  4241.5  432.72  4270.2  430.14  4301.3  425.88  4332.4  423.27  4355.9  422.68
  4395.8  420.19  4456.7  417.65  4560.3  415.11  4684.6  412.83  4746.8  412.90
  4876.0  411.52  5116.2  412.58  5136.2  412.00  5206.3  412.21  5243.3  411.07
  5243.8  410.27  5248.8  410.27  5249.3  411.07  5266.3  411.92  5459.7  412.87
  5509.1  413.80  5594.0  414.00  5657.9  415.21  5862.9  420.92  6059.8  428.38
#Mann=3,-1,0
  4125.6     0.1       0  5243.3    0.07       0  5249.3     0.1       0
Bank Sta=5243.3,5249.3
Exp/Cntr=0.3,0.1

Chan Stop Cuts=-1