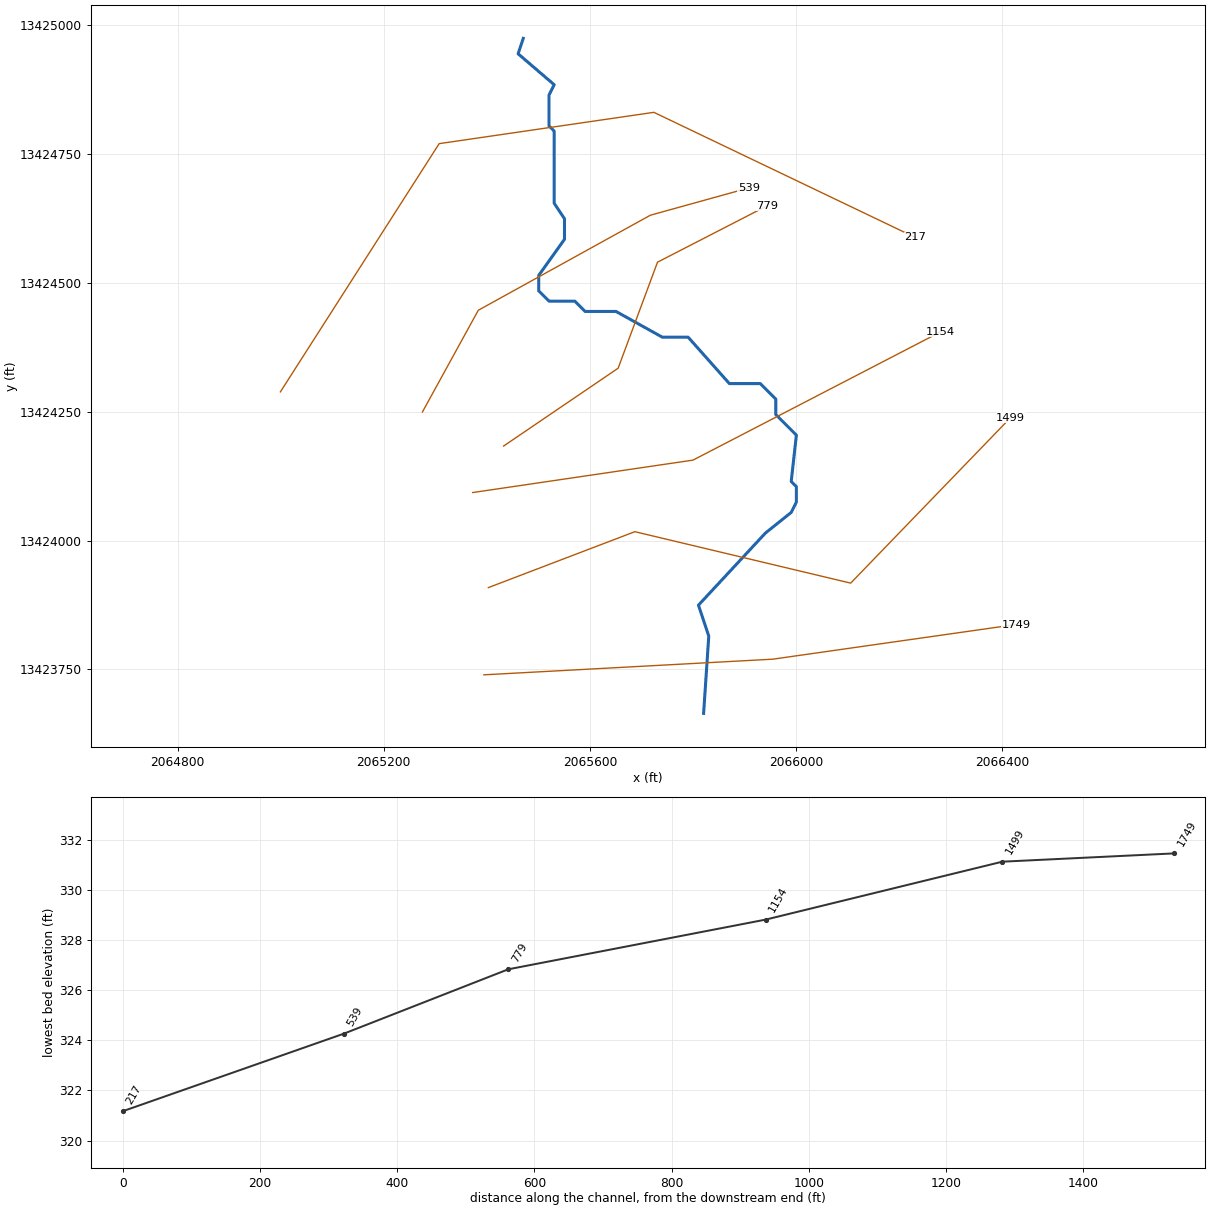
--- UNT 100 in RCW.prj (project) ---

Proj Title=UNT 100 in RCW Base Level Engineering
Current Plan=p01
Default Exp/Contr=0.3,0.1
English Units
Geom File=g01
Flow File=f01
Plan File=p01
BEGIN DESCRIPTION:
UNT 100 in RCW
END DESCRIPTION:

--- UNT 100 in RCW.p01 (plan) ---

Plan Title=Multiple Run
Short Identifier=Multiple
Geom File=g01
Flow File=f01
Subcritical Flow
K Sum by GR= 0
Std Step Tol= 0.01
Critical Tol= 0.01
Num of Std Step Trials= 20
Max Error Tol= 0.3
Flow Tol Ratio= 0.001
Split Flow NTrial= 30
Split Flow Tol= 0.02
Split Flow Ratio= 0.02
Log Output Level= 0
Friction Slope Method= 1
Unsteady Friction Slope Method= 2
Unsteady Bridges Friction Slope Method= 1
Parabolic Critical Depth
Global Vel Dist=  1 , 1 , 1
Global Log Level= 0
CheckData=True
Encroach Param= -1, 0, 0, 0
BEGIN DESCRIPTION:
Multiple Run
END DESCRIPTION:

--- UNT 100 in RCW.f01 (steady flow) ---

Flow Title=Multiple
Number of Profiles=7
Profile Names=10-year,25-year,50-year,1pct_min,100-year,1pct_plu,500-year
River Rch & RM= UNT 100 in RCW,Reach-1,1749
      67      85     100      58     116     232     160
Boundary for River Rch & Prof#=UNT 100 in RCW,Reach-1,1
Up Type=0
Dn Type=3
Dn Slope=0.005
Boundary for River Rch & Prof#=UNT 100 in RCW,Reach-1,2
Up Type=0
Dn Type=3
Dn Slope=0.005
Boundary for River Rch & Prof#=UNT 100 in RCW,Reach-1,3
Up Type=0
Dn Type=3
Dn Slope=0.005
Boundary for River Rch & Prof#=UNT 100 in RCW,Reach-1,4
Up Type=0
Dn Type=3
Dn Slope=0.005
Boundary for River Rch & Prof#=UNT 100 in RCW,Reach-1,5
Up Type=0
Dn Type=3
Dn Slope=0.005
Boundary for River Rch & Prof#=UNT 100 in RCW,Reach-1,6
Up Type=0
Dn Type=3
Dn Slope=0.005
Boundary for River Rch & Prof#=UNT 100 in RCW,Reach-1,7
Up Type=0
Dn Type=3
Dn Slope=0.005

--- UNT 100 in RCW.g01 (geometry) ---

Geom Title=Existing Conditions

River Reach=UNT 100 in RCW,Reach-1
Reach XY= 30
      2065820.80     13423664.54      2065830.80     13423814.54
      2065810.80     13423874.54      2065940.80     13424014.54
      2065990.80     13424054.54      2066000.80     13424074.54
      2066000.80     13424104.54      2065990.80     13424114.54
      2066000.80     13424204.54      2065960.80     13424244.54
      2065960.80     13424274.54      2065930.80     13424304.54
      2065870.80     13424304.54      2065790.80     13424394.54
      2065740.80     13424394.54      2065650.80     13424444.54
      2065590.80     13424444.54      2065570.80     13424464.54
      2065520.80     13424464.54      2065500.80     13424484.54
      2065500.80     13424514.54      2065550.80     13424584.54
      2065550.80     13424624.54      2065530.80     13424654.54
      2065530.80     13424794.54      2065520.80     13424804.54
      2065520.80     13424864.54      2065530.80     13424884.54
      2065460.80     13424944.54      2065470.80     13424974.54

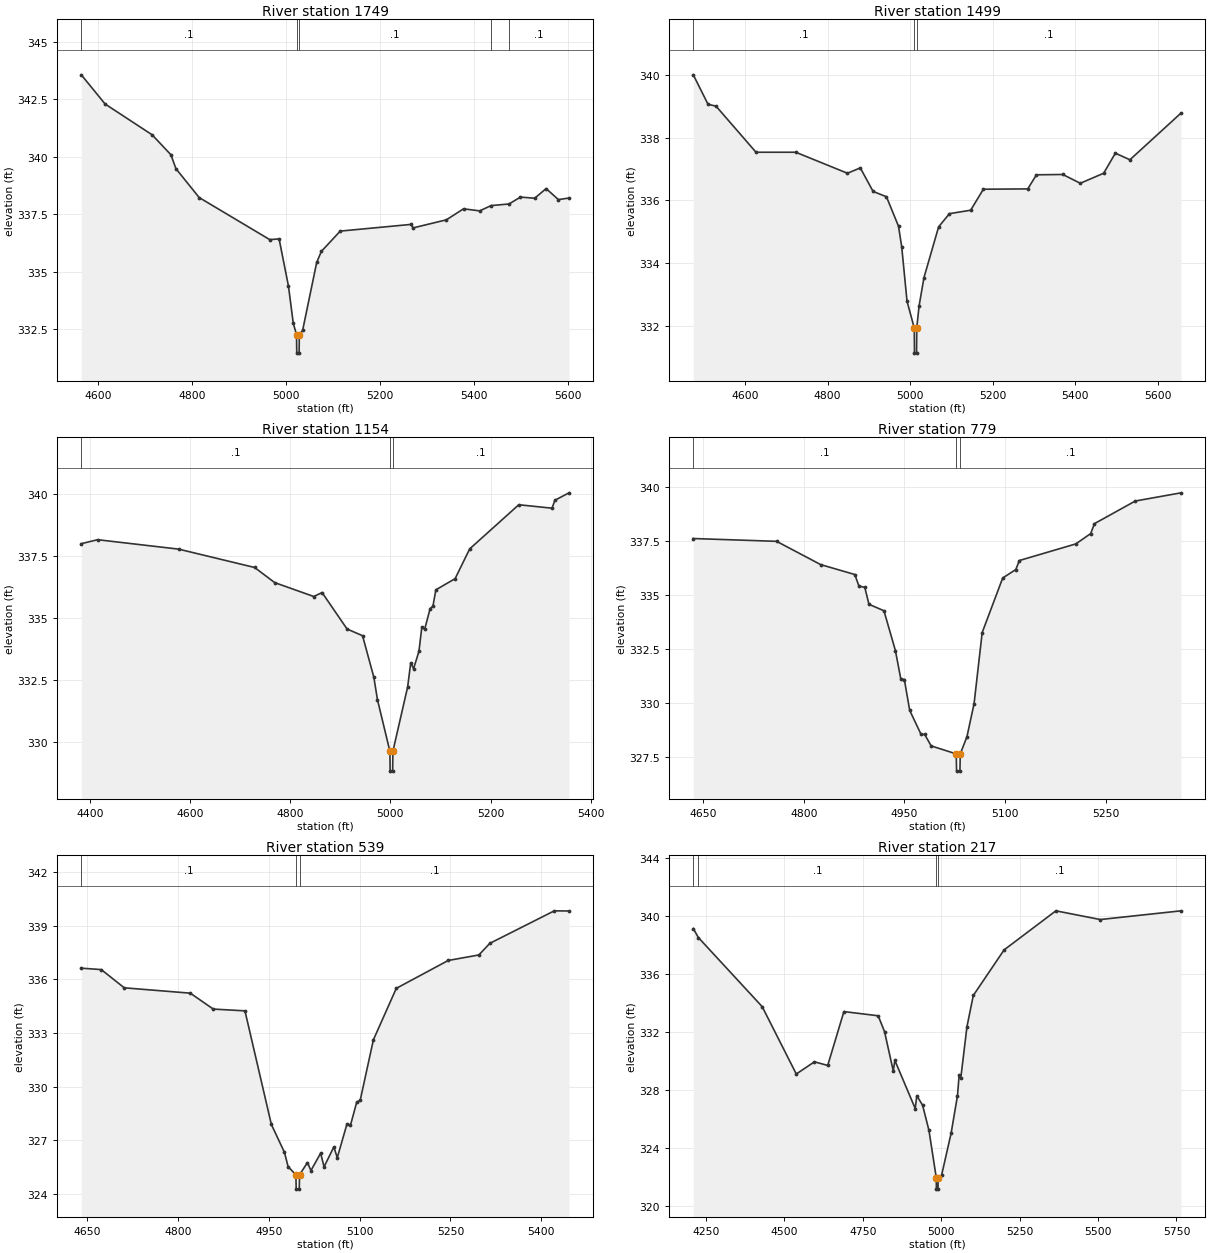
Type RM Length L Ch R = 1,1749,250,250,250
BEGIN DESCRIPTION:
UNT 100 in RCW 2.0
END DESCRIPTION:
XS GIS Cut Line= 3
      2065394.40     13423739.35      2065955.18     13423769.73
      2066427.41     13423837.01
#Sta/Elev= 30
  4564.6  343.56  4615.3  342.29  4715.4  340.95  4755.5  340.08  4766.0  339.48
  4815.6  338.22  4965.8  336.39  4985.8  336.42  5005.8  334.36  5015.9  332.76
  5022.9  332.25  5023.4  331.45  5028.4  331.45  5028.9  332.25  5035.9  332.44
  5065.9  335.40  5075.9  335.88  5116.0  336.76  5266.1  337.05  5271.2  336.90
  5342.0  337.25  5378.5  337.73  5412.8  337.64  5437.2  337.87  5475.3  337.94
  5499.8  338.24  5530.1  338.19  5554.4  338.61  5580.6  338.13  5603.2  338.20
#Mann=5,-1,0
  4564.6     0.1       0  5022.9    0.07       0  5028.9     0.1       0
  5437.2    0.05       0  5475.3     0.1       0
Bank Sta=5022.9,5028.9
Exp/Cntr=0.3,0.1

Type RM Length L Ch R = 1,1499,345,345,345
BEGIN DESCRIPTION:
Mapping XS 5d52c6ba
END DESCRIPTION:
XS GIS Cut Line= 4
      2065403.11     13423908.63      2065687.38     13424017.13
      2066106.22     13423917.30      2066416.58     13424238.52
#Sta/Elev= 30
  4474.9  340.00  4510.6  339.06  4530.0  339.00  4626.8  337.53  4723.1  337.53
  4848.3  336.86  4879.5  337.03  4910.4  336.28  4942.8  336.11  4972.0  335.17
  4979.8  334.51  4992.6  332.78  5010.2  331.92  5010.7  331.12  5015.7  331.12
  5016.2  331.92  5021.9  332.63  5033.7  333.53  5069.2  335.15  5095.4  335.57
  5146.8  335.68  5177.6  336.35  5285.1  336.36  5306.2  336.81  5370.0  336.82
  5412.4  336.54  5469.0  336.86  5497.3  337.50  5532.6  337.29  5656.4  338.78
#Mann=3,-1,0
  4474.9     0.1       0  5010.2    0.07       0  5016.2     0.1       0
Bank Sta=5010.2,5016.2
Exp/Cntr=0.3,0.1

Type RM Length L Ch R = 1,1154,375,375,375
BEGIN DESCRIPTION:
Mapping XS 90d2a3d3
END DESCRIPTION:
XS GIS Cut Line= 3
      2065372.73     13424093.09      2065800.23     13424156.02
      2066281.04     13424405.09
#Sta/Elev= 30
  4383.1  337.98  4415.7  338.14  4577.4  337.76  4729.1  337.02  4769.2  336.41
  4847.2  335.85  4863.7  336.01  4913.6  334.54  4944.5  334.27  4967.0  332.60
  4974.3  331.69  4999.1  329.61  4999.6  328.81  5004.6  328.81  5005.1  329.61
  5034.6  332.21  5040.7  333.18  5046.4  332.94  5057.1  333.64  5062.9  334.62
  5068.5  334.53  5079.4  335.36  5085.0  335.46  5090.9  336.12  5129.3  336.57
  5158.4  337.77  5256.4  339.55  5322.8  339.41  5328.4  339.73  5356.7  340.03
#Mann=3,-1,0
  4383.1     0.1       0  4999.1    0.07       0  5005.1     0.1       0
Bank Sta=4999.1,5005.1
Exp/Cntr=0.3,0.1

Type RM Length L Ch R = 1,779,240,240,240
BEGIN DESCRIPTION:
Mapping XS 8e3cccfd
END DESCRIPTION:
XS GIS Cut Line= 4
      2065432.67     13424183.32      2065654.93     13424334.39
      2065731.32     13424540.12      2065943.96     13424649.47
#Sta/Elev= 30
  4635.1  337.62  4759.3  337.49  4825.1  336.41  4876.0  335.95  4882.0  335.42
  4890.9  335.35  4897.0  334.57  4919.4  334.27  4936.5  332.42  4944.5  331.11
  4949.8  331.08  4957.8  329.65  4974.8  328.53  4980.2  328.53  4989.8  328.00
  5027.2  327.63  5027.7  326.83  5032.7  326.83  5033.2  327.63  5043.2  328.43
  5053.8  329.96  5065.9  333.26  5096.5  335.79  5116.0  336.18  5121.3  336.60
  5205.5  337.37  5227.7  337.85  5233.3  338.31  5294.2  339.36  5362.4  339.74
#Mann=3,-1,0
  4635.1     0.1       0  5027.2    0.07       0  5033.2     0.1       0
Bank Sta=5027.2,5033.2
Exp/Cntr=0.3,0.1

Type RM Length L Ch R = 1,539,322,322,322
BEGIN DESCRIPTION:
Mapping XS d3e9e0c1
END DESCRIPTION:
XS GIS Cut Line= 4
      2065275.04     13424249.31      2065383.56     13424446.82
      2065717.43     13424631.26      2065908.43     13424684.22
#Sta/Elev= 30
  4640.7  336.63  4673.7  336.55  4711.6  335.53  4820.6  335.23  4858.5  334.34
  4910.8  334.24  4954.4  327.88  4976.0  326.32  4982.0  325.52  4994.9  325.06
  4995.4  324.26  5000.4  324.26  5000.9  325.06  5014.0  325.75  5019.7  325.30
  5035.7  326.27  5041.4  325.51  5057.5  326.62  5063.2  326.02  5079.3  327.92
  5085.0  327.84  5095.3  329.13  5101.0  329.23  5122.8  332.62  5160.6  335.50
  5246.2  337.06  5296.9  337.37  5315.0  338.02  5421.4  339.84  5445.7  339.83
#Mann=3,-1,0
  4640.7     0.1       0  4994.9    0.07       0  5000.9     0.1       0
Bank Sta=4994.9,5000.9
Exp/Cntr=0.3,0.1

Type RM Length L Ch R = 1,217,0,0,0
BEGIN DESCRIPTION:
UNT 100 in RCW 1.0
END DESCRIPTION:
XS GIS Cut Line= 4
      2064999.47     13424288.43      2065307.61     13424770.17
      2065724.27     13424830.93      2066231.08     13424588.36
#Sta/Elev= 30
  4209.8  339.12  4226.0  338.50  4429.4  333.74  4538.1  329.10  4596.0  329.94
  4638.3  329.69  4689.9  333.40  4799.2  333.11  4819.4  332.02  4847.3  329.31
  4852.3  330.04  4917.3  326.72  4922.3  327.61  4940.7  326.95  4960.9  325.23
  4984.3  321.97  4984.8  321.17  4989.8  321.17  4990.3  321.97  5001.4  322.14
  5031.7  325.02  5051.9  327.60  5057.3  329.02  5062.4  328.80  5082.2  332.36
  5102.4  334.51  5200.6  337.65  5365.7  340.34  5507.2  339.74  5764.6  340.34
#Mann=4,-1,0
  4209.8    0.05       0  4226.0     0.1       0  4984.3    0.07       0
  4990.3     0.1       0
Bank Sta=4984.3,4990.3
Exp/Cntr=0.3,0.1

Chan Stop Cuts=-1