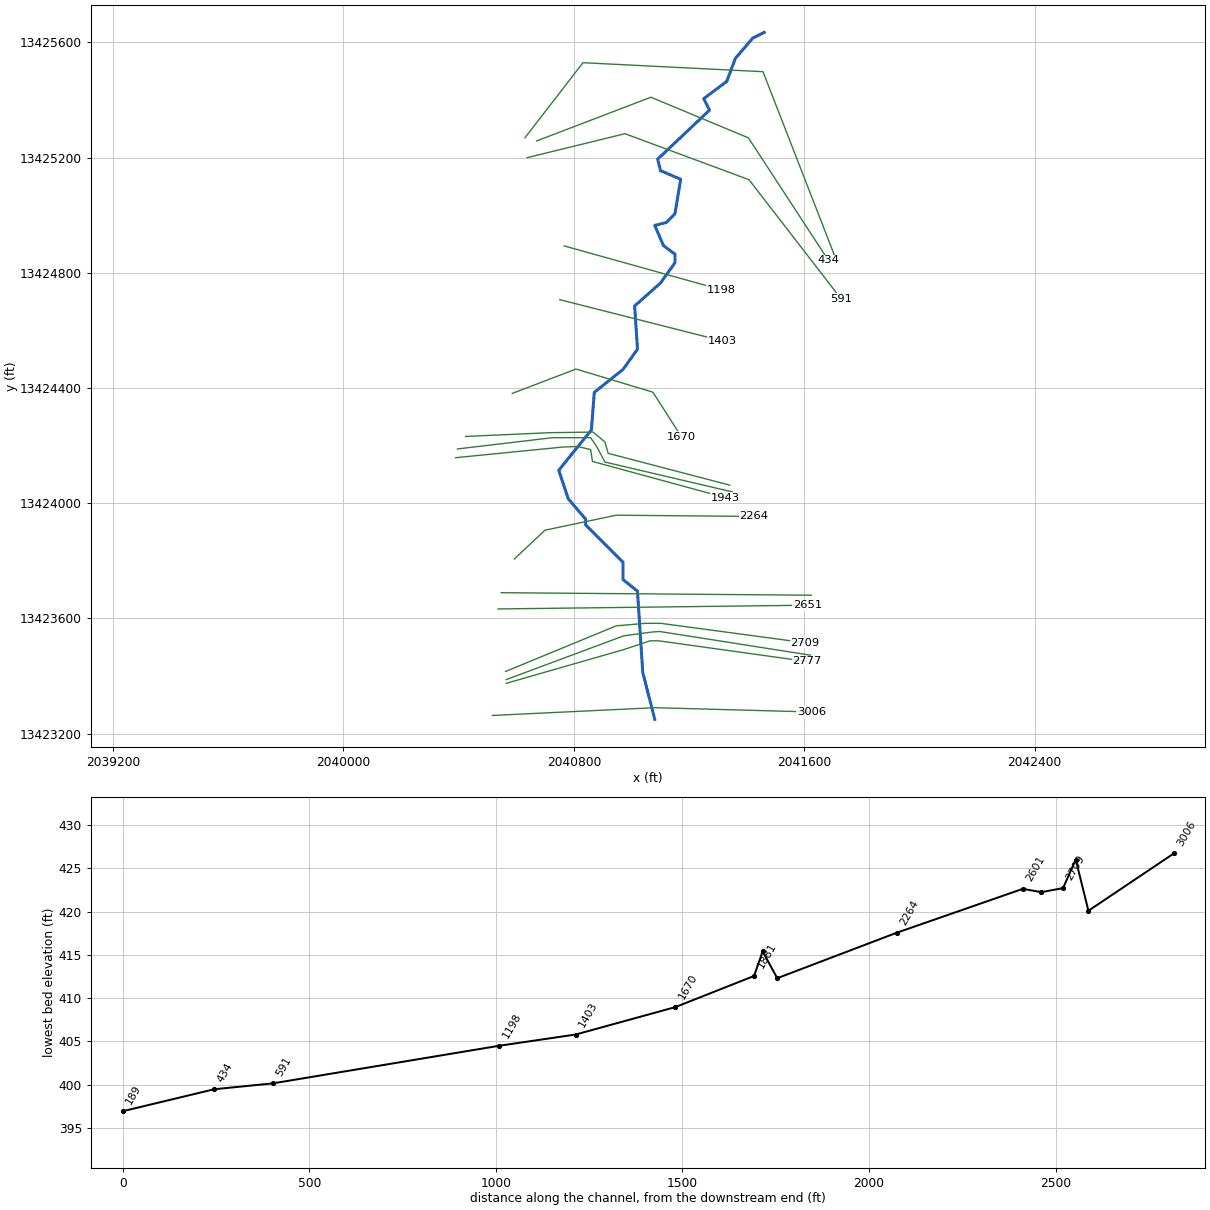
--- UNT 102 in RCW.prj (project) ---

Proj Title=UNT 102 in RCW Base Level Engineering
Current Plan=p01
Default Exp/Contr=0.3,0.1
English Units
Geom File=g01
Flow File=f01
Plan File=p01
BEGIN DESCRIPTION:
UNT 102 in RCW
END DESCRIPTION:

--- UNT 102 in RCW.p01 (plan) ---

Plan Title=Multiple Run
Short Identifier=Multiple
Geom File=g01
Flow File=f01
Subcritical Flow
K Sum by GR= 0
Std Step Tol= 0.01
Critical Tol= 0.01
Num of Std Step Trials= 20
Max Error Tol= 0.3
Flow Tol Ratio= 0.001
Split Flow NTrial= 30
Split Flow Tol= 0.02
Split Flow Ratio= 0.02
Log Output Level= 0
Friction Slope Method= 1
Unsteady Friction Slope Method= 2
Unsteady Bridges Friction Slope Method= 1
Parabolic Critical Depth
Global Vel Dist=  1 , 1 , 1
Global Log Level= 0
CheckData=True
Encroach Param= -1, 0, 0, 0
BEGIN DESCRIPTION:
Multiple Run
END DESCRIPTION:

--- UNT 102 in RCW.f01 (steady flow) ---

Flow Title=Multiple
Program Version=5.05
Number of Profiles= 7
Profile Names=10-year,25-year,50-year,1pct_min,100-year,1pct_plu,500-year
River Rch & RM=UNT 102 in RCW,Reach-1         ,3006
      51      65      75      44      87     174     119
Boundary for River Rch & Prof#=UNT 102 in RCW,Reach-1         , 1
Up Type= 0
Dn Type= 3
Dn Slope=0.005
Boundary for River Rch & Prof#=UNT 102 in RCW,Reach-1         , 2
Up Type= 0
Dn Type= 3
Dn Slope=0.005
Boundary for River Rch & Prof#=UNT 102 in RCW,Reach-1         , 3
Up Type= 0
Dn Type= 3
Dn Slope=0.005
Boundary for River Rch & Prof#=UNT 102 in RCW,Reach-1         , 4
Up Type= 0
Dn Type= 3
Dn Slope=0.005
Boundary for River Rch & Prof#=UNT 102 in RCW,Reach-1         , 5
Up Type= 0
Dn Type= 3
Dn Slope=0.005
Boundary for River Rch & Prof#=UNT 102 in RCW,Reach-1         , 6
Up Type= 0
Dn Type= 3
Dn Slope=0.005
Boundary for River Rch & Prof#=UNT 102 in RCW,Reach-1         , 7
Up Type= 0
Dn Type= 3
Dn Slope=0.005
DSS Import GetInterval= 0
DSS Import GetPeak= 0
DSS Import FillOption= 0

--- UNT 102 in RCW.g01 (geometry) ---

Geom Title=Existing Conditions

River Reach=UNT 102 in RCW,Reach-1
Reach XY= 30
      2041080.80     13423249.54      2041039.11     13423412.31
      2041020.80     13423694.54      2040970.80     13423734.54
      2040970.80     13423794.54      2040840.80     13423924.54
      2040840.80     13423944.54      2040780.80     13424014.54
      2040747.45     13424114.13      2040860.80     13424254.54
      2040870.80     13424384.54      2040970.80     13424464.54
      2041020.80     13424534.54      2041010.80     13424684.54
      2041100.80     13424764.54      2041150.80     13424834.54
      2041150.80     13424864.54      2041110.80     13424894.54
      2041080.80     13424964.54      2041120.80     13424974.54
      2041150.80     13425004.54      2041170.80     13425124.54
      2041100.80     13425154.54      2041090.80     13425194.54
      2041270.80     13425364.54      2041250.80     13425404.54
      2041330.80     13425464.54      2041360.80     13425544.54
      2041420.80     13425614.54      2041460.80     13425634.54

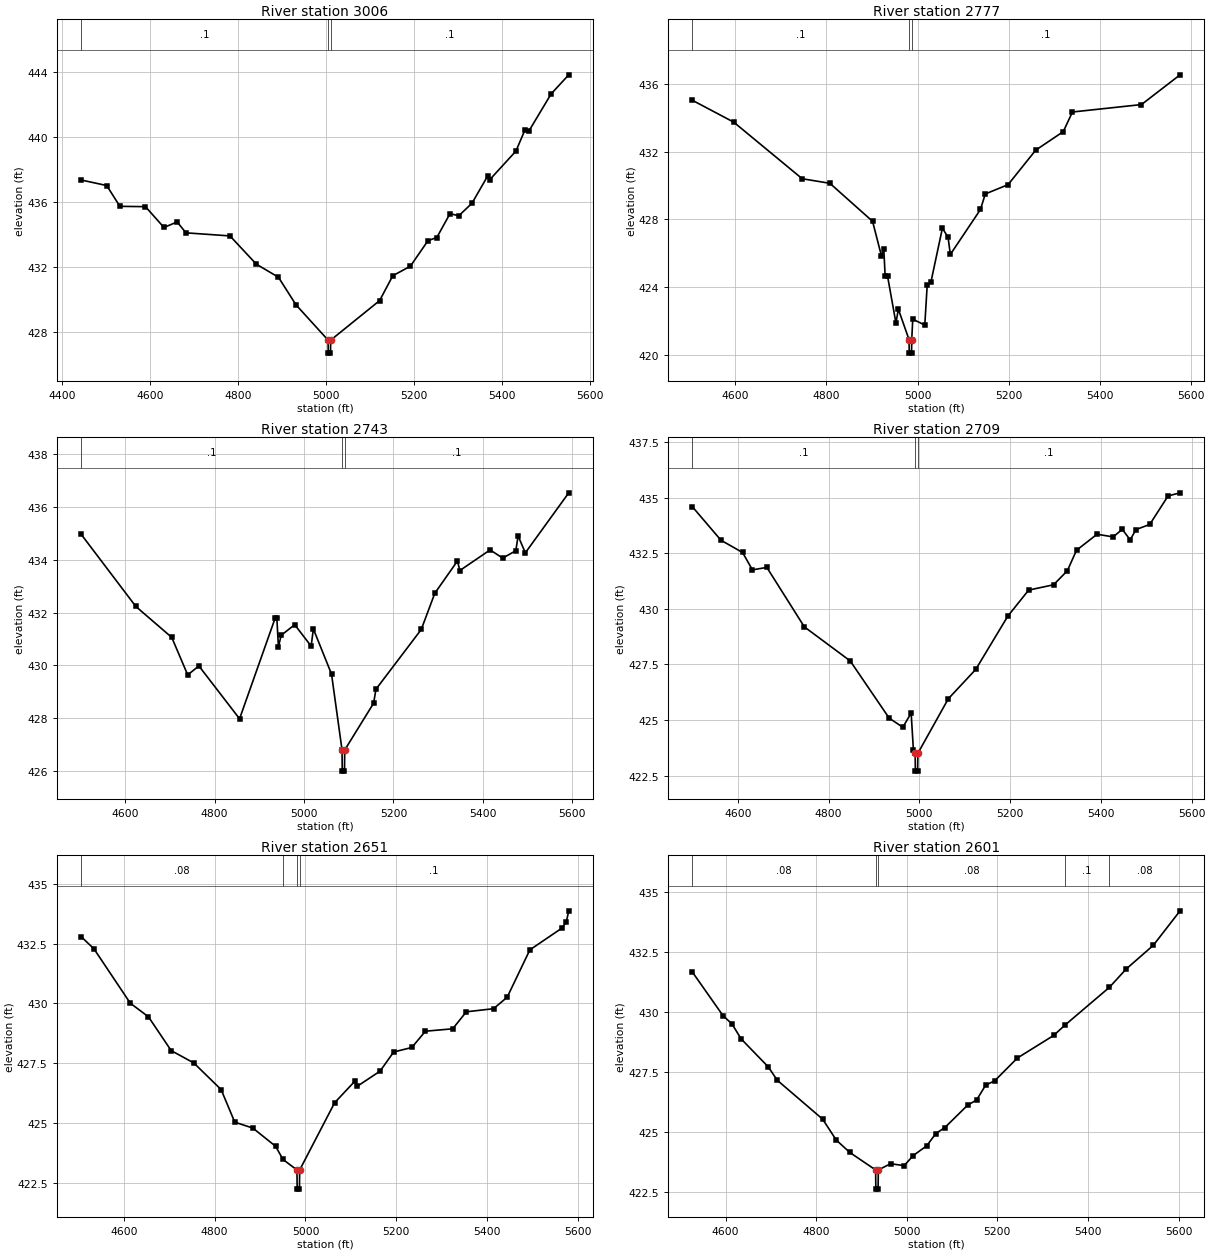
Type RM Length L Ch R = 1,3006,229,229,229
BEGIN DESCRIPTION:
UNT 102 in RCW 3.0
END DESCRIPTION:
XS GIS Cut Line= 3
      2040516.96     13423262.90      2041081.59     13423289.81
      2041625.01     13423275.00
#Sta/Elev= 30
  4443.0  437.37  4501.1  437.03  4531.1  435.75  4589.2  435.73  4631.3  434.45
  4661.3  434.79  4681.3  434.12  4781.4  433.93  4841.5  432.19  4891.6  431.39
  4931.6  429.69  5004.5  427.52  5005.0  426.72  5010.0  426.72  5010.5  427.52
  5121.7  429.95  5151.7  431.48  5191.8  432.07  5231.8  433.64  5251.8  433.83
  5281.8  435.30  5301.8  435.17  5331.8  435.94  5367.6  437.62  5372.6  437.40
  5431.8  439.15  5451.8  440.42  5461.9  440.41  5511.9  442.67  5551.9  443.84
#Mann=3,-1,0
  4443.0     0.1       0  5004.5    0.07       0  5010.5     0.1       0
Bank Sta=5004.5,5010.5
Exp/Cntr=0.3,0.1

Type RM Length L Ch R = 1,2777,34,34,34
BEGIN DESCRIPTION:
Mapping XS 1a0ac065
END DESCRIPTION:
XS GIS Cut Line= 5
      2040565.08     13423374.44      2040973.08     13423491.63
      2041064.22     13423522.01      2041094.61     13423522.01
      2041608.89     13423450.40
#Sta/Elev= 30
  4505.9  435.05  4596.4  433.76  4746.8  430.41  4807.5  430.14  4901.2  427.89
  4920.6  425.85  4925.8  426.25  4928.8  424.66  4934.0  424.66  4952.5  421.87
  4957.8  422.69  4981.2  420.89  4981.7  420.09  4986.7  420.09  4987.2  420.89
  4989.4  422.10  5015.8  421.75  5021.1  424.12  5029.4  424.31  5054.5  427.49
  5066.9  426.94  5071.9  425.93  5138.0  428.59  5148.6  429.51  5198.6  430.06
  5259.2  432.10  5319.8  433.20  5339.9  434.36  5491.4  434.80  5576.1  436.56
#Mann=3,-1,0
  4505.9     0.1       0  4981.2    0.07       0  4987.2     0.1       0
Bank Sta=4981.2,4987.2
Exp/Cntr=0.3,0.1

Type RM Length L Ch R = 1,2743,34,34,34
BEGIN DESCRIPTION:
Mapping XS bd4301df
END DESCRIPTION:
XS GIS Cut Line= 5
      2040565.09     13423387.46      2040973.08     13423539.37
      2041070.74     13423552.39      2041096.78     13423554.56
      2041620.95     13423472.26
#Sta/Elev= 30
  4501.5  434.96  4623.8  432.23  4704.1  431.06  4739.8  429.64  4764.8  429.98
  4855.8  427.98  4935.2  431.78  4939.2  431.78  4942.7  430.71  4948.9  431.14
  4979.1  431.54  5015.9  430.73  5020.9  431.38  5061.5  429.67  5085.0  426.80
  5085.5  426.00  5090.5  426.00  5091.0  426.80  5155.6  428.57  5160.9  429.10
  5262.2  431.36  5292.5  432.73  5343.1  433.95  5348.5  433.59  5416.2  434.37
  5444.4  434.06  5473.7  434.34  5478.8  434.90  5495.0  434.26  5592.1  436.53
#Mann=3,-1,0
  4501.5     0.1       0  5085.0    0.07       0  5091.0     0.1       0
Bank Sta=5085,5091
Exp/Cntr=0.3,0.1

Type RM Length L Ch R = 1,2709,58,58,58
BEGIN DESCRIPTION:
Mapping XS 4a6c264d
END DESCRIPTION:
XS GIS Cut Line= 5
      2040562.92     13423415.68      2040947.04     13423574.10
      2041049.03     13423582.78      2041101.12     13423582.78
      2041601.18     13423515.67
#Sta/Elev= 30
  4500.0  434.58  4562.8  433.08  4610.4  432.53  4632.1  431.75  4663.9  431.86
  4746.5  429.19  4847.6  427.66  4933.5  425.09  4963.6  424.68  4981.9  425.32
  4986.9  423.65  4990.7  423.51  4991.2  422.71  4996.2  422.71  4996.7  423.51
  5063.8  425.96  5124.3  427.28  5194.9  429.67  5240.8  430.84  5295.8  431.08
  5326.1  431.71  5346.3  432.63  5391.6  433.35  5427.0  433.23  5447.2  433.57
  5464.5  433.10  5477.5  433.56  5507.7  433.79  5548.1  435.07  5574.5  435.21
#Mann=3,-1,0
  4500.0     0.1       0  4990.7    0.07       0  4996.7     0.1       0
Bank Sta=4990.7,4996.7
Exp/Cntr=0.3,0.1

Type RM Length L Ch R = 1,2651,50,50,50
BEGIN DESCRIPTION:
Mapping XS 14ff2939
END DESCRIPTION:
XS GIS Cut Line= 2
      2040536.83     13423632.69      2041610.56     13423645.70
#Sta/Elev= 30
  4506.0  432.79  4534.2  432.28  4614.2  430.01  4654.2  429.44  4704.2  428.03
  4754.2  427.51  4814.2  426.40  4844.2  425.04  4884.2  424.79  4934.2  424.03
  4950.5  423.48  4981.2  423.04  4981.7  422.24  4986.7  422.24  4987.2  423.04
  5064.2  425.85  5109.2  426.76  5114.2  426.54  5164.2  427.17  5194.2  427.97
  5234.2  428.16  5264.2  428.84  5324.2  428.94  5354.2  429.65  5414.2  429.78
  5444.2  430.26  5494.2  432.24  5564.2  433.14  5574.2  433.39  5579.8  433.87
#Mann=4,-1,0
  4506.0    0.08       0  4950.5     0.1       0  4981.2    0.07       0
  4987.2     0.1       0
Bank Sta=4981.2,4987.2
Exp/Cntr=0.3,0.1

Type RM Length L Ch R = 1,2601,337,337,337
BEGIN DESCRIPTION:
Mapping XS deb5a704
END DESCRIPTION:
XS GIS Cut Line= 2
      2040547.71     13423689.11      2041624.08     13423680.43
#Sta/Elev= 30
  4526.9  431.67  4594.2  429.86  4614.2  429.51  4634.2  428.89  4694.2  427.72
  4714.2  427.16  4814.2  425.54  4844.2  424.67  4874.2  424.15  4931.2  423.42
  4931.7  422.62  4936.7  422.62  4937.2  423.42  4964.2  423.68  4994.2  423.60
  5014.2  424.02  5044.2  424.43  5064.2  424.94  5084.2  425.19  5134.2  426.12
  5154.2  426.34  5174.2  426.96  5194.2  427.14  5244.2  428.09  5324.2  429.03
  5349.1  429.46  5447.4  431.04  5484.2  431.80  5544.2  432.79  5603.3  434.23
#Mann=5,-1,0
  4526.9    0.08       0  4931.2    0.07       0  4937.2    0.08       0
  5349.1     0.1       0  5447.4    0.08       0
Bank Sta=4931.2,4937.2
Exp/Cntr=0.3,0.1

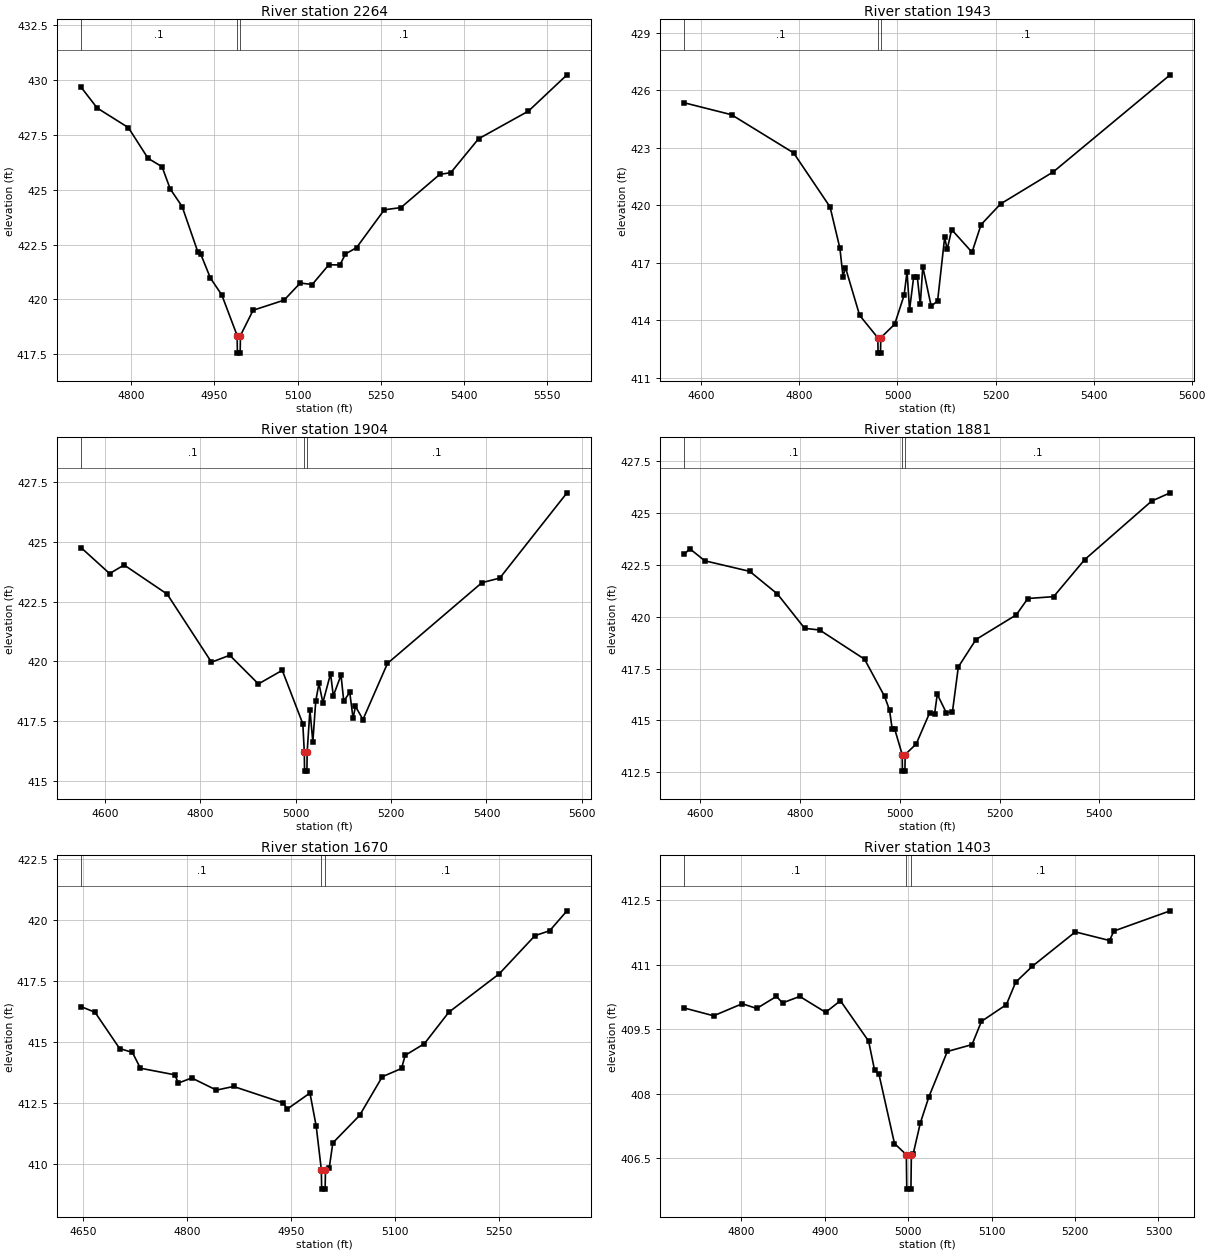
Type RM Length L Ch R = 1,2264,321,321,321
BEGIN DESCRIPTION:
Mapping XS 687f6c5d
END DESCRIPTION:
XS GIS Cut Line= 4
      2040593.31     13423806.30      2040699.64     13423906.13
      2040947.04     13423958.21      2041424.45     13423953.87
#Sta/Elev= 30
  4709.9  429.65  4738.7  428.71  4794.9  427.82  4830.5  426.42  4855.7  426.04
  4870.4  425.03  4891.9  424.23  4920.3  422.16  4925.4  422.07  4943.0  420.97
  4963.4  420.21  4991.1  418.36  4991.6  417.56  4996.6  417.56  4997.1  418.36
  5019.9  419.51  5075.8  419.97  5105.0  420.75  5126.5  420.68  5156.5  421.58
  5176.5  421.57  5186.5  422.07  5206.5  422.36  5256.5  424.08  5286.5  424.18
  5356.5  425.69  5376.5  425.77  5426.5  427.31  5516.5  428.57  5586.0  430.22
#Mann=3,-1,0
  4709.9     0.1       0  4991.1    0.07       0  4997.1     0.1       0
Bank Sta=4991.1,4997.1
Exp/Cntr=0.3,0.1

Type RM Length L Ch R = 1,1943,39,39,39
BEGIN DESCRIPTION:
Mapping XS ad6f2fdb
END DESCRIPTION:
XS GIS Cut Line= 6
      2040389.27     13424157.86      2040760.41     13424194.76
      2040812.49     13424196.93      2040858.06     13424186.07
      2040864.57     13424144.84      2041324.93     13424019.49
#Sta/Elev= 30
  4565.3  425.34  4661.5  424.72  4788.1  422.73  4862.5  419.91  4882.6  417.75
  4888.9  416.28  4893.9  416.75  4922.8  414.26  4959.9  413.09  4960.4  412.29
  4965.4  412.29  4965.9  413.09  4994.3  413.80  5013.5  415.31  5019.5  416.54
  5024.6  414.54  5033.1  416.28  5040.3  416.28  5046.5  414.83  5051.6  416.79
  5068.7  414.74  5081.8  415.01  5096.2  418.32  5101.4  417.70  5110.5  418.73
  5152.0  417.55  5170.5  418.99  5210.3  420.07  5317.8  421.74  5556.1  426.80
#Mann=3,-1,0
  4565.3     0.1       0  4959.9    0.07       0  4965.9     0.1       0
Bank Sta=4959.9,4965.9
Exp/Cntr=0.3,0.1

Type RM Length L Ch R = 1,1904,23,23,23
BEGIN DESCRIPTION:
Mapping XS dc2839fc
END DESCRIPTION:
XS GIS Cut Line= 6
      2040395.77     13424188.24      2040725.68     13424227.31
      2040858.06     13424227.31      2040877.59     13424199.10
      2040907.97     13424142.67      2041351.39     13424038.85
#Sta/Elev= 30
  4550.4  424.75  4610.0  423.67  4640.3  424.03  4730.6  422.81  4823.5  419.96
  4861.8  420.25  4921.9  419.05  4971.9  419.62  5015.0  417.38  5018.1  416.20
  5018.6  415.40  5023.6  415.40  5024.1  416.20  5029.9  417.96  5036.0  416.62
  5042.1  418.33  5048.8  419.07  5057.0  418.27  5073.2  419.48  5078.9  418.55
  5095.1  419.42  5100.8  418.33  5113.4  418.70  5120.3  417.61  5125.4  418.11
  5141.1  417.56  5192.5  419.91  5390.5  423.29  5427.9  423.48  5568.8  427.05
#Mann=3,-1,0
  4550.4     0.1       0  5018.1    0.07       0  5024.1     0.1       0
Bank Sta=5018.1,5024.1
Exp/Cntr=0.3,0.1

Type RM Length L Ch R = 1,1881,211,211,211
BEGIN DESCRIPTION:
Mapping XS af54a7bb
END DESCRIPTION:
XS GIS Cut Line= 6
      2040424.00     13424231.65      2040714.83     13424244.67
      2040866.74     13424246.84      2040907.97     13424212.12
      2040918.83     13424173.05      2041341.02     13424062.63
#Sta/Elev= 30
  4567.9  423.02  4578.9  423.28  4608.9  422.70  4699.0  422.19  4754.4  421.10
  4809.1  419.44  4839.2  419.36  4929.2  417.95  4969.2  416.16  4979.2  415.50
  4984.6  414.58  4989.6  414.58  5004.6  413.35  5005.1  412.55  5010.1  412.55
  5010.6  413.35  5032.7  413.86  5059.6  415.36  5069.7  415.33  5074.9  416.26
  5093.0  415.37  5105.4  415.42  5117.2  417.58  5152.5  418.90  5233.3  420.09
  5256.5  420.88  5308.2  420.97  5370.2  422.75  5504.6  425.58  5541.8  425.98
#Mann=3,-1,0
  4567.9     0.1       0  5004.6    0.07       0  5010.6     0.1       0
Bank Sta=5004.6,5010.6
Exp/Cntr=0.3,0.1

Type RM Length L Ch R = 1,1670,267,267,267
BEGIN DESCRIPTION:
Mapping XS 0ebe719d
END DESCRIPTION:
XS GIS Cut Line= 4
      2040586.07     13424381.08      2040807.38     13424465.70
      2041074.31     13424385.40      2041173.87     13424229.57
#Sta/Elev= 30
  4647.0  416.45  4666.9  416.22  4702.4  414.73  4720.8  414.57  4732.4  413.92
  4781.8  413.65  4787.2  413.31  4806.4  413.52  4842.0  413.02  4866.7  413.17
  4938.7  412.49  4944.1  412.24  4976.9  412.90  4985.9  411.54  4993.3  409.75
  4993.8  408.95  4998.8  408.95  4999.3  409.75  5004.7  409.82  5009.9  410.85
  5048.5  411.98  5081.2  413.57  5109.0  413.91  5114.2  414.45  5142.0  414.93
  5177.1  416.22  5249.9  417.80  5301.4  419.37  5322.6  419.57  5347.6  420.39
#Mann=3,-1,0
  4647.0     0.1       0  4993.3    0.07       0  4999.3     0.1       0
Bank Sta=4993.3,4999.3
Exp/Cntr=0.3,0.1

Type RM Length L Ch R = 1,1403,205,205,205
BEGIN DESCRIPTION:
Mapping XS 0f02c2d8
END DESCRIPTION:
XS GIS Cut Line= 2
      2040750.94     13424706.59      2041315.15     13424563.36
#Sta/Elev= 30
  4731.9  409.99  4767.0  409.81  4801.2  410.09  4818.6  409.98  4842.2  410.26
  4849.6  410.11  4870.2  410.26  4901.2  409.89  4918.9  410.16  4952.7  409.22
  4959.9  408.54  4965.1  408.45  4983.7  406.84  4997.9  406.58  4998.4  405.78
  5003.4  405.78  5003.9  406.58  5006.0  406.59  5014.7  407.32  5025.0  407.93
  5047.0  408.98  5076.6  409.14  5087.9  409.68  5117.8  410.07  5128.9  410.59
  5148.8  410.96  5200.4  411.76  5241.4  411.56  5246.6  411.78  5314.0  412.25
#Mann=3,-1,0
  4731.9     0.1       0  4997.9    0.07       0  5003.9     0.1       0
Bank Sta=4997.9,5003.9
Exp/Cntr=0.3,0.1

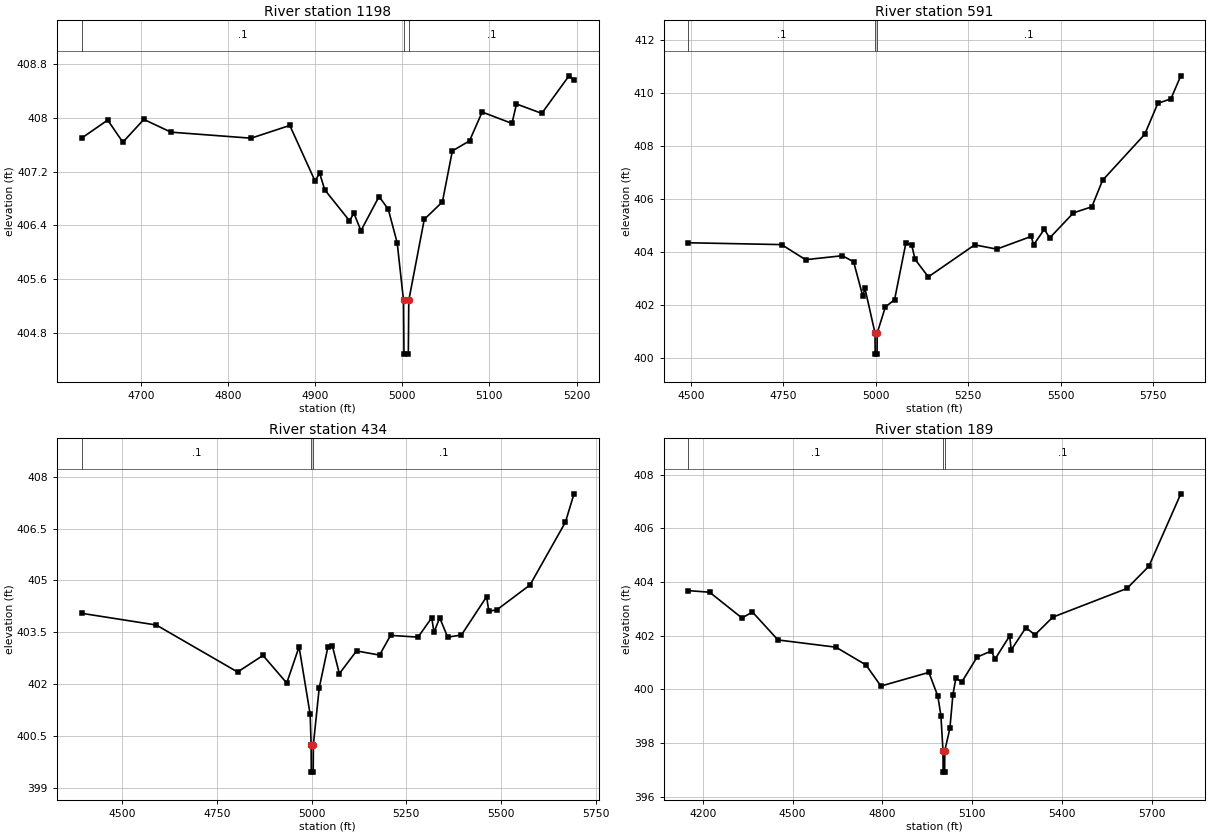
Type RM Length L Ch R = 1,1198,607,607,607
BEGIN DESCRIPTION:
Mapping XS 4ab54940
END DESCRIPTION:
XS GIS Cut Line= 2
      2040766.15     13424893.21      2041310.47     13424741.41
#Sta/Elev= 30
  4632.0  407.70  4662.0  407.97  4679.4  407.64  4703.5  407.98  4734.6  407.79
  4826.5  407.70  4871.0  407.89  4900.0  407.06  4905.2  407.18  4911.1  406.93
  4939.4  406.47  4944.6  406.58  4952.6  406.32  4973.4  406.83  4984.0  406.64
  4994.2  406.14  5001.5  405.28  5002.0  404.48  5007.0  404.48  5007.5  405.28
  5025.3  406.49  5046.1  406.75  5057.5  407.51  5077.2  407.66  5091.7  408.09
  5125.9  407.92  5131.1  408.21  5160.1  408.07  5191.4  408.63  5197.1  408.57
#Mann=3,-1,0
  4632.0     0.1       0  5001.5    0.07       0  5007.5     0.1       0
Bank Sta=5001.5,5007.5
Exp/Cntr=0.3,0.1

Type RM Length L Ch R = 1,591,157,157,157
BEGIN DESCRIPTION:
Mapping XS 29ad6869
END DESCRIPTION:
XS GIS Cut Line= 4
      2040637.10     13425199.52      2040977.42     13425282.86
      2041407.97     13425123.14      2041727.37     13424710.01
#Sta/Elev= 30
  4492.7  404.34  4744.9  404.27  4809.7  403.70  4909.3  403.85  4939.7  403.62
  4964.7  402.31  4970.1  402.63  4997.5  400.93  4998.0  400.13  5003.0  400.13
  5003.5  400.93  5025.5  401.91  5050.5  402.19  5080.9  404.32  5096.5  404.27
  5105.9  403.71  5141.7  403.05  5267.1  404.26  5326.8  404.10  5420.0  404.58
  5426.4  404.26  5455.4  404.85  5469.9  404.52  5534.2  405.47  5584.0  405.70
  5612.9  406.70  5727.0  408.44  5762.4  409.61  5797.7  409.78  5824.5  410.65
#Mann=3,-1,0
  4492.7     0.1       0  4997.5    0.07       0  5003.5     0.1       0
Bank Sta=4997.5,5003.5
Exp/Cntr=0.3,0.1

Type RM Length L Ch R = 1,434,245,245,245
BEGIN DESCRIPTION:
Mapping XS f55abcc9
END DESCRIPTION:
XS GIS Cut Line= 4
      2040670.33     13425257.59      2041067.43     13425409.48
      2041405.97     13425268.42      2041683.73     13424843.10
#Sta/Elev= 30
  4392.6  404.05  4590.1  403.71  4804.5  402.35  4871.6  402.83  4934.3  402.03
  4966.8  403.08  4996.1  401.12  4998.6  400.25  4999.1  399.45  5004.1  399.45
  5004.6  400.25  5020.0  401.89  5042.6  403.06  5054.6  403.11  5073.1  402.30
  5118.5  402.96  5179.2  402.84  5208.3  403.41  5280.8  403.36  5317.0  403.92
  5322.9  403.50  5338.0  403.92  5359.1  403.36  5395.3  403.42  5461.8  404.53
  5467.7  404.11  5488.8  404.15  5576.4  404.87  5669.9  406.69  5692.5  407.51
#Mann=3,-1,0
  4392.6     0.1       0  4998.6    0.07       0  5004.6     0.1       0
Bank Sta=4998.6,5004.6
Exp/Cntr=0.3,0.1

Type RM Length L Ch R = 1,189,0,0,0
BEGIN DESCRIPTION:
UNT 102 in RCW 1.0
END DESCRIPTION:
XS GIS Cut Line= 4
      2040630.20     13425268.98      2040831.59     13425529.39
      2041456.59     13425498.14      2041706.60     13424855.75
#Sta/Elev= 30
  4152.0  403.68  4223.1  403.62  4330.9  402.66  4366.2  402.88  4451.3  401.84
  4644.8  401.57  4744.9  400.91  4795.0  400.12  4955.2  400.63  4985.2  399.74
  4995.3  399.02  5002.3  397.71  5002.8  396.91  5007.8  396.91  5008.3  397.71
  5025.3  398.54  5035.3  399.79  5045.3  400.42  5065.0  400.27  5116.1  401.20
  5164.0  401.43  5175.8  401.12  5224.8  401.99  5230.2  401.47  5279.2  402.30
  5309.1  402.03  5368.9  402.69  5616.4  403.76  5689.8  404.59  5796.3  407.29
#Mann=3,-1,0
  4152.0     0.1       0  5002.3    0.07       0  5008.3     0.1       0
Bank Sta=5002.3,5008.3
Exp/Cntr=0.3,0.1

Chan Stop Cuts=-1