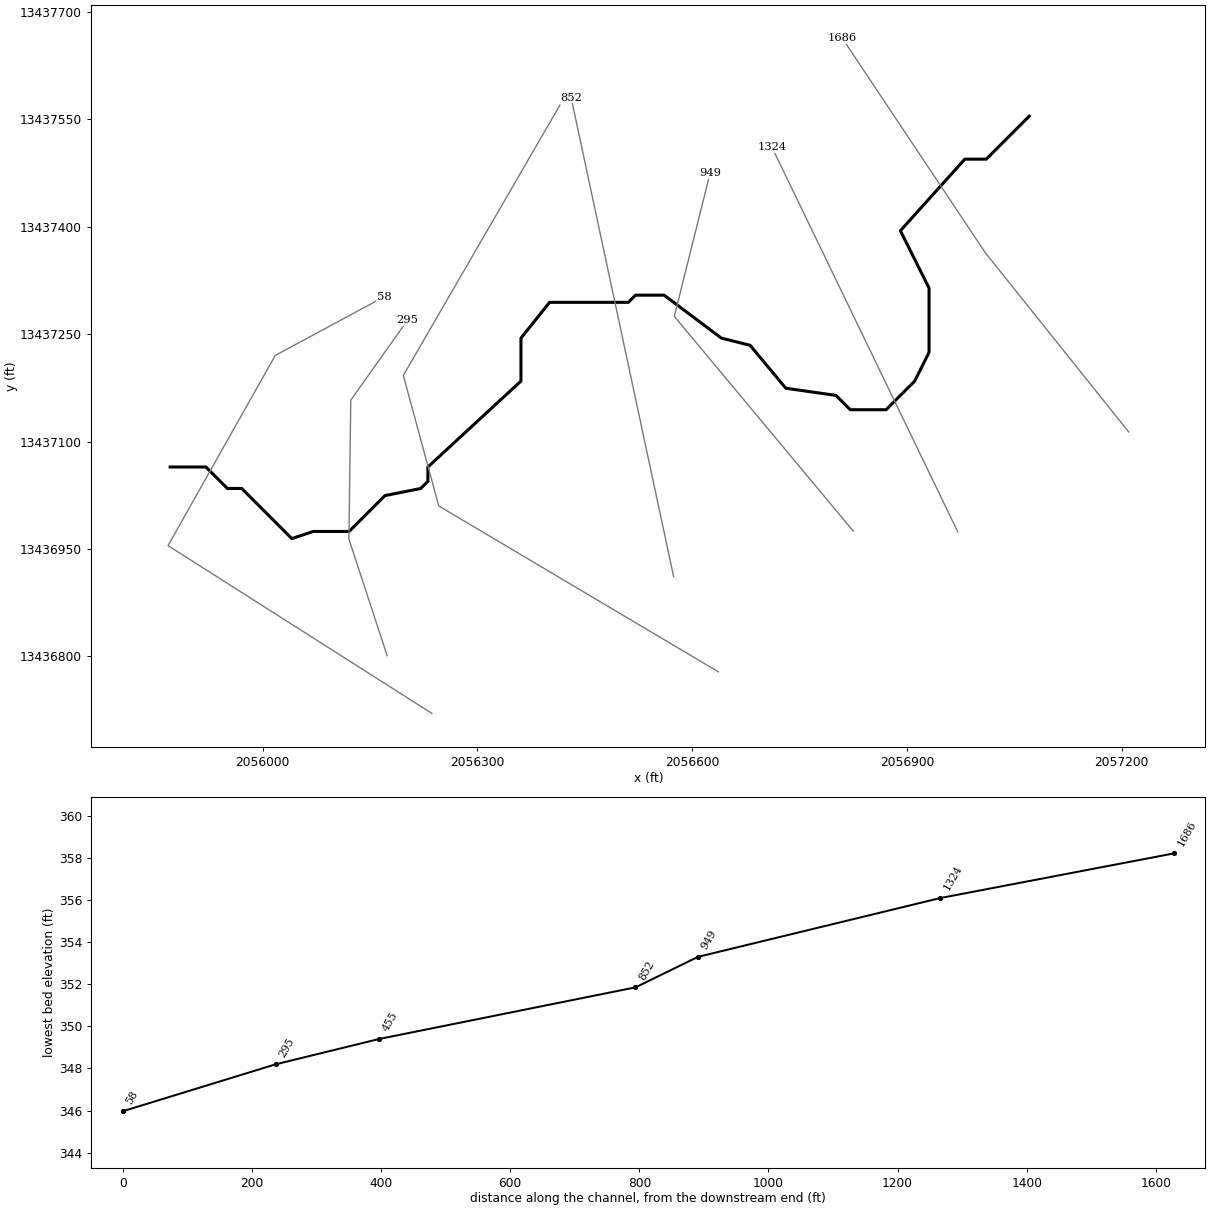
--- UNT 103 in RCW.prj (project) ---

Proj Title=UNT 103 in RCW Base Level Engineering
Current Plan=p01
Default Exp/Contr=0.3,0.1
English Units
Geom File=g01
Flow File=f01
Plan File=p01
Y Axis Title=Elevation
X Axis Title(PF)=Main Channel Distance
X Axis Title(XS)=Station
BEGIN DESCRIPTION:
UNT 103 in RCW
END DESCRIPTION:
DSS Export Rating Curves= 0
DSS Export Rating Curve Sorted= 0
DSS Export Volume Flow Curves= 0
DXF OffsetX= 0
DXF OffsetY= 0
DXF ScaleX= 1
DXF ScaleY= 10

--- UNT 103 in RCW.p01 (plan) ---

Plan Title=Multiple Run
Short Identifier=Multiple
Geom File=g01
Flow File=f01
Subcritical Flow
K Sum by GR= 0
Std Step Tol= 0.01
Critical Tol= 0.01
Num of Std Step Trials= 20
Max Error Tol= 0.3
Flow Tol Ratio= 0.001
Split Flow NTrial= 30
Split Flow Tol= 0.02
Split Flow Ratio= 0.02
Log Output Level= 0
Friction Slope Method= 1
Unsteady Friction Slope Method= 2
Unsteady Bridges Friction Slope Method= 1
Parabolic Critical Depth
Global Vel Dist=  1 , 1 , 1
Global Log Level= 0
CheckData=True
Encroach Param= -1, 0, 0, 0
BEGIN DESCRIPTION:
Multiple Run
END DESCRIPTION:

--- UNT 103 in RCW.f01 (steady flow) ---

Flow Title=Multiple
Number of Profiles=7
Profile Names=10-year,25-year,50-year,1pct_min,100-year,1pct_plu,500-year
River Rch & RM= UNT 103 in RCW,Reach-1,1686
     140     188     227     137     274     547     404
Boundary for River Rch & Prof#=UNT 103 in RCW,Reach-1,1
Up Type=0
Dn Type=3
Dn Slope=0.005
Boundary for River Rch & Prof#=UNT 103 in RCW,Reach-1,2
Up Type=0
Dn Type=3
Dn Slope=0.005
Boundary for River Rch & Prof#=UNT 103 in RCW,Reach-1,3
Up Type=0
Dn Type=3
Dn Slope=0.005
Boundary for River Rch & Prof#=UNT 103 in RCW,Reach-1,4
Up Type=0
Dn Type=3
Dn Slope=0.005
Boundary for River Rch & Prof#=UNT 103 in RCW,Reach-1,5
Up Type=0
Dn Type=3
Dn Slope=0.005
Boundary for River Rch & Prof#=UNT 103 in RCW,Reach-1,6
Up Type=0
Dn Type=3
Dn Slope=0.005
Boundary for River Rch & Prof#=UNT 103 in RCW,Reach-1,7
Up Type=0
Dn Type=3
Dn Slope=0.005

--- UNT 103 in RCW.g01 (geometry) ---

Geom Title=Existing Conditions
Program Version=5.05

River Reach=UNT 103 in RCW  ,Reach-1
Reach XY= 30
       2057070.8     13437554.54       2057010.8     13437494.54
       2056980.8     13437494.54       2056890.8     13437394.54
       2056930.8     13437314.54       2056930.8     13437224.54
       2056910.8     13437184.54       2056870.8     13437144.54
       2056820.8     13437144.54       2056800.8     13437164.54
       2056730.8     13437174.54       2056680.8     13437234.54
       2056640.8     13437244.54       2056560.8     13437304.54
       2056520.8     13437304.54       2056510.8     13437294.54
       2056400.8     13437294.54       2056360.8     13437244.54
       2056360.8     13437184.54       2056230.8     13437064.54
       2056230.8     13437044.54       2056220.8     13437034.54
       2056170.8     13437024.54       2056120.8     13436974.54
       2056070.8     13436974.54       2056040.8     13436964.54
       2055970.8     13437034.54       2055950.8     13437034.54
       2055920.8     13437064.54       2055870.8     13437064.54

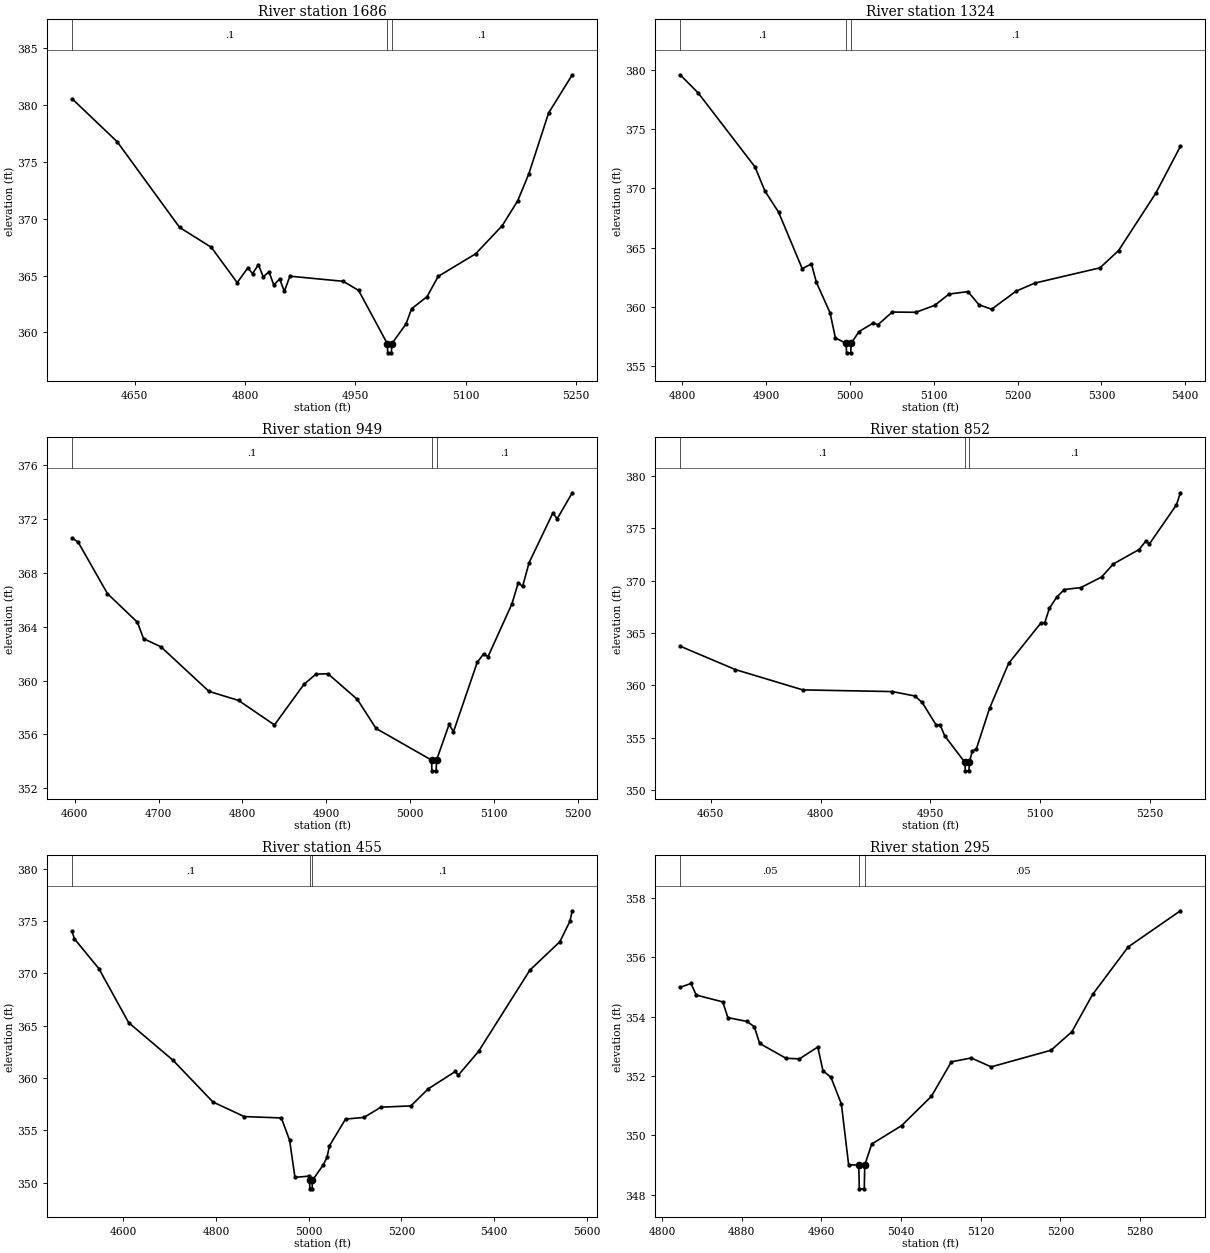
Type RM Length L Ch R = 1 ,1686    ,362,362,362
BEGIN DESCRIPTION:
UNT 103 in RCW 3.0
END DESCRIPTION:
XS GIS Cut Line= 3
      2057209.63     13437113.55      2057009.64     13437363.54
       2056809.8     13437663.29
#Sta/Elev= 30
  4564.6  380.56  4626.1  376.77  4710.9  369.24  4754.1  367.49  4789.3  364.38
  4803.7  365.68  4810.1  365.18  4818.2  365.96  4824.6   364.9  4832.6  365.33
    4839  364.17    4847  364.71  4853.4  363.62    4861  364.95  4933.4   364.5
  4954.4   363.7  4993.5  359.01    4994  358.21    4999  358.21  4999.5  359.01
  5018.7  360.73  5026.5  362.09  5047.5  363.15  5062.6  364.93  5113.6  366.92
  5149.7  369.39  5170.7  371.57  5185.8  373.93  5212.8   379.3    5245  382.66
#Mann= 3 ,-1 , 0
  4564.6      .1       0  4993.5     .07       0  4999.5      .1       0
Bank Sta=4993.5,4999.5
XS Rating Curve= 0 ,0
Exp/Cntr=0.3,0.1

Type RM Length L Ch R = 1 ,1324    ,375,375,375
BEGIN DESCRIPTION:
Mapping XS 3521f748
END DESCRIPTION:
XS GIS Cut Line= 2
      2056970.97     13436973.88      2056711.28     13437511.44
#Sta/Elev= 30
  4797.2  379.61  4818.8  378.07  4886.6  371.81  4898.4  369.78  4914.7  367.99
  4942.9  363.21  4953.9  363.61  4959.9  362.04  4976.1  359.48  4982.5  357.35
  4995.3  356.89  4995.8  356.09  5000.8  356.09  5001.3  356.89  5010.7  357.89
  5027.7  358.61  5033.3  358.47  5050.3  359.54  5078.5  359.52  5101.1  360.11
  5118.1  361.06  5140.7  361.27  5153.8  360.16  5168.9  359.78  5198.2  361.31
  5220.5  361.99  5298.2  363.28  5320.4  364.74  5364.8  369.59  5394.2  373.56
#Mann= 3 ,-1 , 0
  4797.2      .1       0  4995.3     .07       0  5001.3      .1       0
Bank Sta=4995.3,5001.3
XS Rating Curve= 0 ,0
Exp/Cntr=0.3,0.1

Type RM Length L Ch R = 1 ,949     ,97,97,97
BEGIN DESCRIPTION:
UNT 103 in RCW 2.0
END DESCRIPTION:
XS GIS Cut Line= 3
      2056825.03     13436974.97        2056575.       13437275.
        2056625.     13437474.99
#Sta/Elev= 30
  4596.8  370.59    4604   370.3  4639.1  366.46  4674.9  364.33  4682.1  363.12
  4702.9  362.51  4760.2   359.2  4795.4  358.53  4838.3  356.71  4873.5  359.73
  4887.8  360.48  4902.1  360.51  4937.2   358.6  4959.4  356.45  5025.6   354.1
  5026.1   353.3  5031.1   353.3  5031.6   354.1  5046.6  356.75  5051.8   356.2
  5080.1  361.35  5087.9     362    5093  361.78  5121.4  365.68  5129.1  367.27
  5134.2  366.99    5142  368.76  5170.3  372.44  5175.5  372.02  5193.5  373.95
#Mann= 3 ,-1 , 0
  4596.8      .1       0  5025.6     .07       0  5031.6      .1       0
Bank Sta=5025.6,5031.6
XS Rating Curve= 0 ,0
Exp/Cntr=0.3,0.1

Type RM Length L Ch R = 1 ,852     ,397,397,397
BEGIN DESCRIPTION:
Mapping XS 9c26fad5
END DESCRIPTION:
XS GIS Cut Line= 2
       2056574.1     13436911.22      2056430.92     13437580.27
#Sta/Elev= 30
    4608  363.74  4683.5  361.51  4775.8  359.57  4898.2  359.41  4928.9  358.99
  4939.1  358.37  4958.3   356.2  4963.4  356.26  4969.8   355.2  4997.5  352.65
    4998  351.85    5003  351.85  5003.5  352.65  5007.7  353.76  5012.9  353.89
  5031.2  357.81  5057.2  362.09  5101.5  365.96  5106.7  365.98    5113  367.35
  5123.2  368.43  5133.4  369.14  5156.1  369.33  5184.5  370.34  5200.5  371.58
  5235.7  372.96  5244.8  373.75  5249.9   373.5  5286.8  377.22  5292.2  378.37
#Mann= 3 ,-1 , 0
    4608      .1       0  4997.5     .07       0  5003.5      .1       0
Bank Sta=4997.5,5003.5
XS Rating Curve= 0 ,0
Exp/Cntr=0.3,0.1

Type RM Length L Ch R = 1 ,455     ,160,160,160
BEGIN DESCRIPTION:
Mapping XS b045825e
END DESCRIPTION:
XS GIS Cut Line= 4
      2056636.61     13436778.39      2056245.98     13437010.17
       2056196.5     13437192.46      2056415.26     13437570.07
#Sta/Elev= 30
  4489.1  374.03  4494.5   373.3  4547.2  370.45  4611.4  365.29    4707   361.7
  4793.3   357.7  4860.9  356.31  4940.8  356.18  4958.7  354.04  4970.2   350.5
  4999.6  350.61  5001.8   350.2  5002.3   349.4  5007.3   349.4  5007.8   350.2
  5031.2  351.69  5039.4  352.42  5044.6  353.51  5079.3  356.07  5119.1  356.23
  5155.8  357.21  5220.4  357.33  5257.7  358.96  5316.5  360.63  5322.3  360.25
  5366.3  362.54  5477.2  370.32  5541.8  373.03  5563.3  374.97  5568.6  375.99
#Mann= 3 ,-1 , 0
  4489.1      .1       0  5001.8     .07       0  5007.8      .1       0
Bank Sta=5001.8,5007.8
XS Rating Curve= 0 ,0
Exp/Cntr=0.3,0.1

Type RM Length L Ch R = 1 ,295     ,237,237,237
BEGIN DESCRIPTION:
Mapping XS 2a5c498d
END DESCRIPTION:
XS GIS Cut Line= 4
      2056173.89     13436801.07       2056120.5     13436963.87
       2056123.1     13437157.88       2056202.5     13437269.82
#Sta/Elev= 30
    4818  354.99  4828.9  355.12  4834.2  354.73  4860.8   354.5    4866  353.97
  4885.3  353.84  4892.6  353.66  4897.9   353.1  4924.4   352.6  4937.9  352.58
  4956.3  352.98  4961.5  352.18  4969.5  351.96    4980  351.06  4987.3  349.01
  4997.5     349    4998   348.2    5003   348.2  5003.5     349  5010.5  349.71
  5040.5  350.33  5070.5  351.32  5090.5  352.48  5110.5  352.61  5130.5  352.31
  5190.6  352.87  5211.5  353.49  5232.4  354.75  5268.1  356.35  5320.6  357.57
#Mann= 3 ,-1 , 0
    4818     .05       0  4997.5     .03       0  5003.5     .05       0
Bank Sta=4997.5,5003.5
XS Rating Curve= 0 ,0
Exp/Cntr=0.3,0.1

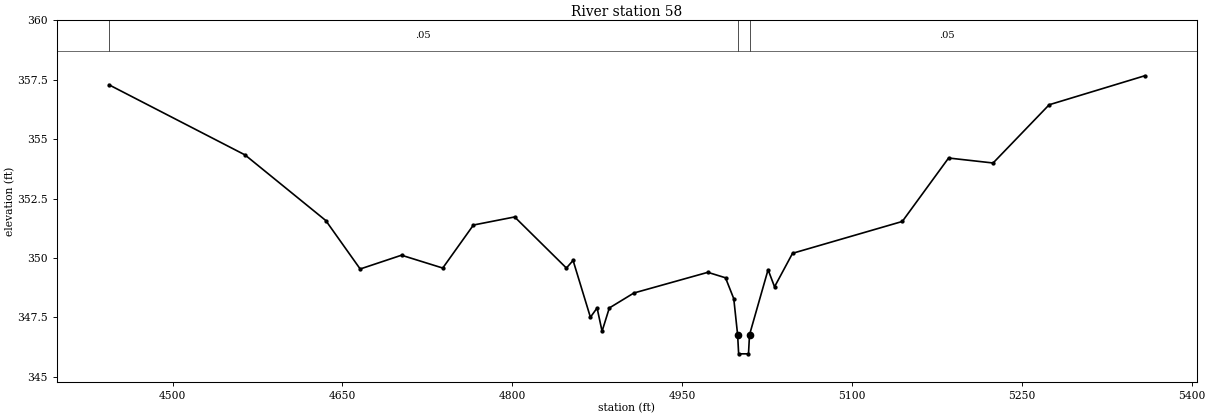
Type RM Length L Ch R = 1 ,58      ,0,0,0
BEGIN DESCRIPTION:
UNT 103 in RCW 1.0
END DESCRIPTION:
XS GIS Cut Line= 4
      2056236.34      13436720.4      2055867.89     13436954.75
      2056017.63     13437220.38      2056169.96      13437302.4
#Sta/Elev= 30
  4443.9  357.29    4564  354.34  4635.3  351.58  4665.7  349.54  4702.2  350.12
  4738.6  349.58  4765.7  351.39  4802.1  351.73  4847.8  349.58  4853.7   349.9
    4869  347.51  4874.9   347.9  4879.3  346.92  4885.7   347.9  4907.4  348.53
  4972.7   349.4  4988.3  349.17  4995.6  348.29    4999  346.77  4999.9  345.97
  5008.6  345.97  5009.5  346.77  5025.9  349.51  5031.6  348.79  5047.5   350.2
  5144.4  351.54  5185.3  354.21  5224.6     354  5274.1  356.45  5358.5  357.67
#Mann= 3 ,-1 , 0
  4443.9     .05       0    4999     .03       0  5009.5     .05       0
Bank Sta=4999,5009.5
XS Rating Curve= 0 ,0
Exp/Cntr=0.3,0.1
LCMann Table=0

Chan Stop Cuts=-1
Use User Specified Reach Order=0
Composite Channel Slope=5