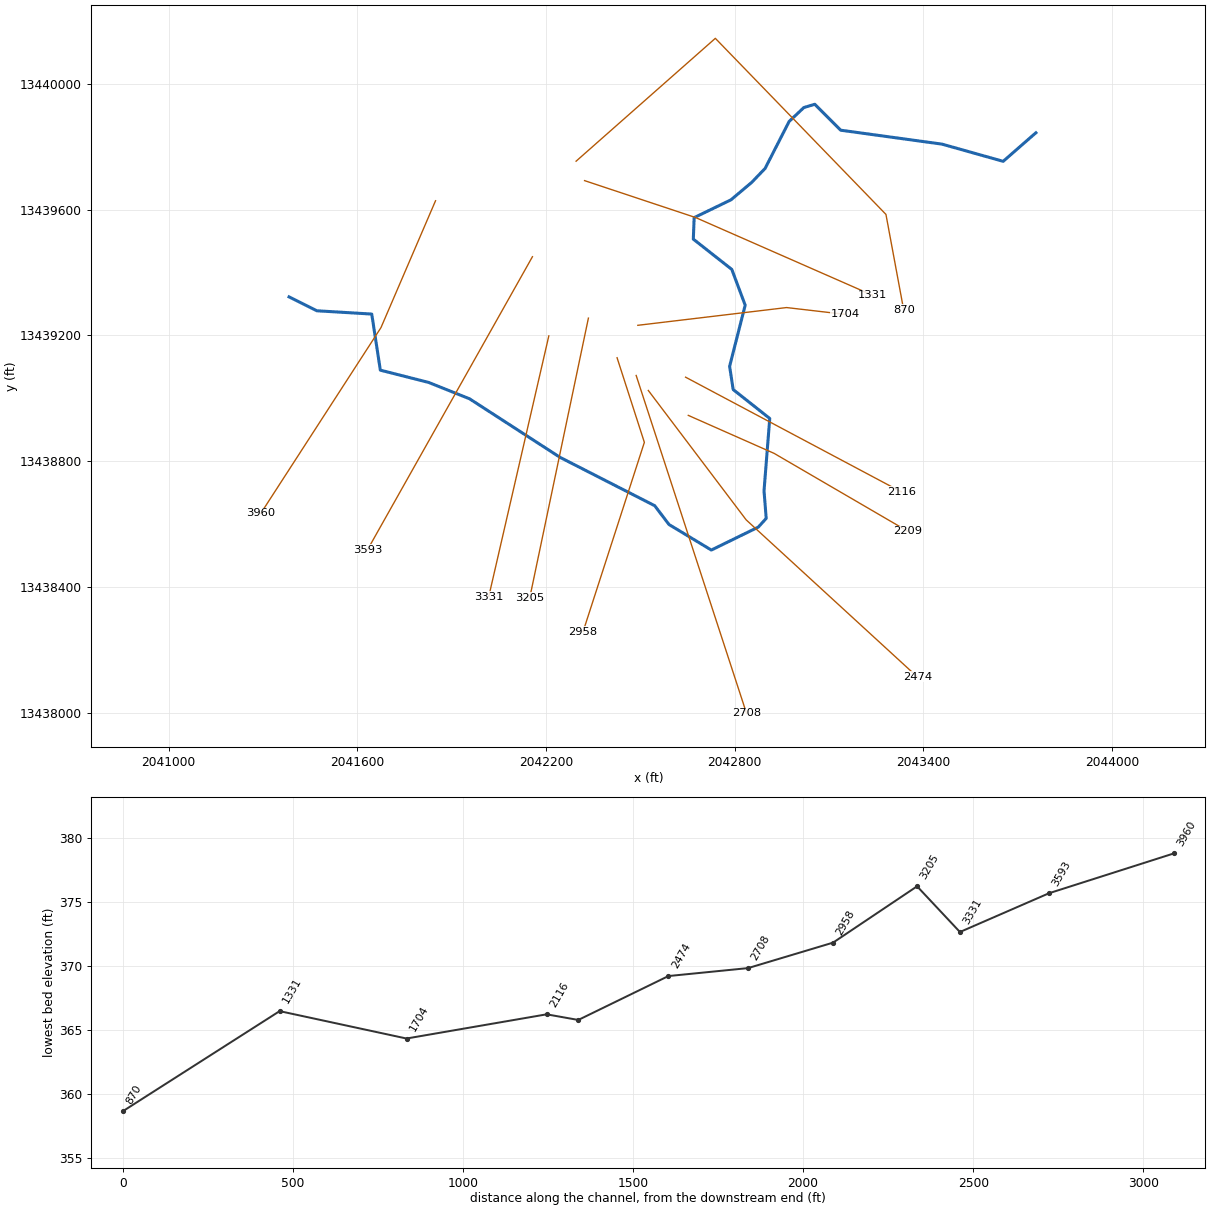
--- UNT 104 in RCW.prj (project) ---

Proj Title=UNT 104 in RCW Base Level Engineering
Current Plan=p01
Default Exp/Contr=0.3,0.1
English Units
Geom File=g01
Flow File=f01
Plan File=p01
BEGIN DESCRIPTION:
UNT 104 in RCW
END DESCRIPTION:

--- UNT 104 in RCW.p01 (plan) ---

Plan Title=Multiple Run
Short Identifier=Multiple
Geom File=g01
Flow File=f01
Subcritical Flow
K Sum by GR= 0
Std Step Tol= 0.01
Critical Tol= 0.01
Num of Std Step Trials= 20
Max Error Tol= 0.3
Flow Tol Ratio= 0.001
Split Flow NTrial= 30
Split Flow Tol= 0.02
Split Flow Ratio= 0.02
Log Output Level= 0
Friction Slope Method= 1
Unsteady Friction Slope Method= 2
Unsteady Bridges Friction Slope Method= 1
Parabolic Critical Depth
Global Vel Dist=  1 , 1 , 1
Global Log Level= 0
CheckData=True
Encroach Param= -1, 0, 0, 0
BEGIN DESCRIPTION:
Multiple Run
END DESCRIPTION:

--- UNT 104 in RCW.f01 (steady flow) ---

Flow Title=Multiple
Number of Profiles=7
Profile Names=10-year,25-year,50-year,1pct_min,100-year,1pct_plu,500-year
River Rch & RM= UNT 104 in RCW,Reach-1,3960
     149     201     244     148     295     589     437
Boundary for River Rch & Prof#=UNT 104 in RCW,Reach-1,1
Up Type=0
Dn Type=3
Dn Slope=0.005
Boundary for River Rch & Prof#=UNT 104 in RCW,Reach-1,2
Up Type=0
Dn Type=3
Dn Slope=0.005
Boundary for River Rch & Prof#=UNT 104 in RCW,Reach-1,3
Up Type=0
Dn Type=3
Dn Slope=0.005
Boundary for River Rch & Prof#=UNT 104 in RCW,Reach-1,4
Up Type=0
Dn Type=3
Dn Slope=0.005
Boundary for River Rch & Prof#=UNT 104 in RCW,Reach-1,5
Up Type=0
Dn Type=3
Dn Slope=0.005
Boundary for River Rch & Prof#=UNT 104 in RCW,Reach-1,6
Up Type=0
Dn Type=3
Dn Slope=0.005
Boundary for River Rch & Prof#=UNT 104 in RCW,Reach-1,7
Up Type=0
Dn Type=3
Dn Slope=0.005

--- UNT 104 in RCW.g01 (geometry) ---

Geom Title=Existing Conditions

River Reach=UNT 104 in RCW,Reach-1
Reach XY= 30
      2041382.56     13439322.63      2041471.10     13439278.36
      2041645.58     13439267.94      2041672.92     13439089.56
      2041826.57     13439050.50      2041956.78     13438998.41
      2042244.54     13438812.21      2042545.32     13438658.57
      2042590.89     13438598.67      2042725.44     13438517.51
      2042874.74     13438590.43      2042899.92     13438618.20
      2042892.97     13438705.88      2042911.20     13438935.91
      2042794.88     13439027.93      2042783.60     13439101.71
      2042833.08     13439296.16      2042790.54     13439409.87
      2042668.15     13439506.22      2042670.80     13439574.54
      2042787.94     13439631.22      2042853.91     13439686.78
      2042896.45     13439731.05      2042972.83     13439880.36
      2043019.71     13439924.63      2043054.43     13439935.04
      2043136.90     13439852.58      2043458.95     13439808.31
      2043653.39     13439753.62      2043757.49     13439844.36

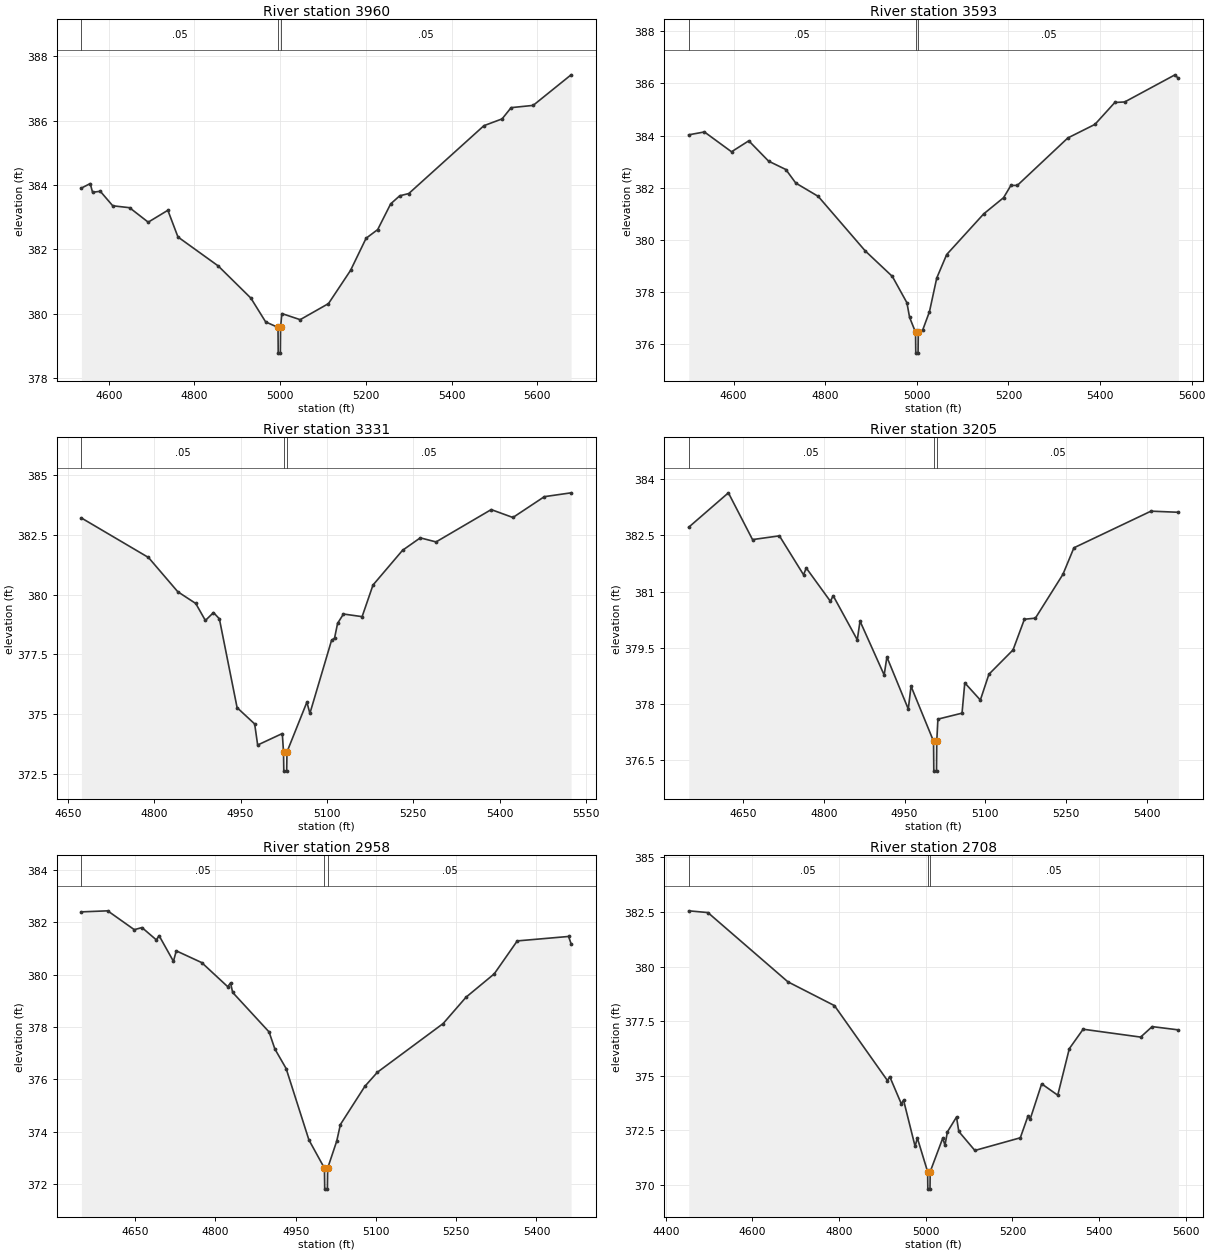
Type RM Length L Ch R = 1,3960,367,367,367
BEGIN DESCRIPTION:
UNT 104 in RCW 8.0
END DESCRIPTION:
XS GIS Cut Line= 3
      2041848.42     13439628.25      2041675.00     13439225.00
      2041292.85     13438634.29
#Sta/Elev= 30
  4536.2  383.90  4556.8  384.04  4562.2  383.77  4580.3  383.80  4609.3  383.35
  4648.6  383.29  4692.1  382.84  4737.9  383.21  4761.5  382.38  4855.4  381.48
  4931.6  380.48  4966.1  379.74  4994.9  379.57  4995.4  378.77  5000.4  378.77
  5000.9  379.57  5003.9  380.00  5046.6  379.81  5112.7  380.31  5164.1  381.34
  5200.4  382.34  5227.5  382.61  5257.8  383.41  5278.9  383.66  5300.0  383.73
  5475.4  385.84  5517.7  386.05  5538.8  386.40  5590.2  386.47  5678.7  387.42
#Mann=3,-1,0
  4536.2    0.05       0  4994.9    0.03       0  5000.9    0.05       0
Bank Sta=4994.9,5000.9
Exp/Cntr=0.3,0.1

Type RM Length L Ch R = 1,3593,262,262,262
BEGIN DESCRIPTION:
Mapping XS 7006643a
END DESCRIPTION:
XS GIS Cut Line= 2
      2042156.58     13439450.29      2041632.19     13438518.51
#Sta/Elev= 30
  4501.9  384.03  4536.2  384.14  4595.4  383.38  4633.1  383.80  4676.4  383.02
  4714.0  382.70  4735.7  382.18  4784.7  381.67  4887.3  379.58  4946.6  378.60
  4978.4  377.59  4984.2  377.03  4997.2  376.46  4997.7  375.66  5002.7  375.66
  5003.2  376.46  5012.9  376.55  5027.6  377.25  5043.5  378.54  5065.2  379.44
  5146.1  381.00  5189.4  381.62  5205.4  382.09  5219.4  382.09  5329.7  383.91
  5388.9  384.43  5432.3  385.27  5453.9  385.29  5563.7  386.33  5571.1  386.19
#Mann=3,-1,0
  4501.9    0.05       0  4997.2    0.03       0  5003.2    0.05       0
Bank Sta=4997.2,5003.2
Exp/Cntr=0.3,0.1

Type RM Length L Ch R = 1,3331,126,126,126
BEGIN DESCRIPTION:
Mapping XS 94708014
END DESCRIPTION:
XS GIS Cut Line= 2
      2042208.65     13439198.50      2042017.74     13438369.80
#Sta/Elev= 30
  4673.7  383.20  4790.2  381.55  4841.1  380.12  4872.3  379.63  4889.0  378.92
  4903.1  379.25  4913.3  378.99  4944.1  375.28  4974.6  374.60  4979.8  373.72
  5022.6  374.20  5024.7  373.43  5025.2  372.63  5030.2  372.63  5030.7  373.43
  5065.3  375.51  5070.5  375.04  5108.1  378.09  5113.3  378.18  5118.6  378.80
  5128.8  379.19  5161.2  379.08  5180.1  380.40  5231.4  381.85  5262.2  382.37
  5289.6  382.20  5385.4  383.55  5423.1  383.22  5477.7  384.09  5524.1  384.25
#Mann=3,-1,0
  4673.7    0.05       0  5024.7    0.03       0  5030.7    0.05       0
Bank Sta=5024.7,5030.7
Exp/Cntr=0.3,0.1

Type RM Length L Ch R = 1,3205,247,247,247
BEGIN DESCRIPTION:
Mapping XS 36964544
END DESCRIPTION:
XS GIS Cut Line= 2
      2042334.53     13439255.01      2042147.88     13438365.17
#Sta/Elev= 30
  4549.2  382.72  4622.9  383.64  4667.7  382.39  4717.6  382.49  4762.4  381.45
  4767.5  381.63  4812.3  380.74  4817.4  380.89  4862.2  379.71  4867.3  380.21
  4912.1  378.77  4917.2  379.25  4956.9  377.86  4962.0  378.47  5003.8  377.00
  5004.3  376.20  5009.3  376.20  5009.8  377.00  5011.9  377.59  5056.7  377.75
  5061.8  378.56  5090.7  378.10  5106.6  378.79  5151.4  379.44  5172.5  380.26
  5192.9  380.29  5244.0  381.46  5264.4  382.17  5407.5  383.15  5458.4  383.12
#Mann=3,-1,0
  4549.2    0.05       0  5003.8    0.03       0  5009.8    0.05       0
Bank Sta=5003.8,5009.8
Exp/Cntr=0.3,0.1

Type RM Length L Ch R = 1,2958,250,250,250
BEGIN DESCRIPTION:
Mapping XS 096e2cd0
END DESCRIPTION:
XS GIS Cut Line= 3
      2042425.68     13439129.05      2042512.47     13438859.99
      2042317.69     13438258.34
#Sta/Elev= 30
  4549.6  382.40  4598.7  382.44  4648.4  381.72  4662.8  381.80  4689.6  381.33
  4694.8  381.49  4721.6  380.51  4726.9  380.91  4774.5  380.46  4823.0  379.54
  4828.3  379.68  4832.3  379.32  4900.3  377.81  4911.1  377.16  4932.2  376.41
  4974.8  373.68  5003.8  372.60  5004.3  371.80  5009.3  371.80  5009.8  372.60
  5026.8  373.64  5033.6  374.27  5079.3  375.73  5102.8  376.27  5225.6  378.13
  5268.5  379.14  5321.1  380.03  5364.1  381.29  5460.1  381.46  5464.7  381.18
#Mann=3,-1,0
  4549.6    0.05       0  5003.8    0.03       0  5009.8    0.05       0
Bank Sta=5003.8,5009.8
Exp/Cntr=0.3,0.1

Type RM Length L Ch R = 1,2708,234,234,234
BEGIN DESCRIPTION:
Mapping XS 7a61d2e5
END DESCRIPTION:
XS GIS Cut Line= 2
      2042486.42     13439072.69      2042837.38     13437998.15
#Sta/Elev= 30
  4452.8  382.55  4497.1  382.47  4681.8  379.30  4789.3  378.21  4911.6  374.78
  4916.9  374.96  4943.5  373.72  4948.8  373.88  4975.4  371.77  4980.6  372.15
  5004.3  370.61  5004.8  369.81  5009.8  369.81  5010.3  370.61  5039.2  372.14
  5044.4  371.82  5050.0  372.43  5071.0  373.11  5076.3  372.45  5113.4  371.58
  5218.3  372.16  5235.7  373.14  5241.0  373.01  5267.6  374.63  5304.7  374.11
  5331.4  376.24  5363.3  377.13  5496.1  376.77  5522.7  377.25  5583.2  377.10
#Mann=3,-1,0
  4452.8    0.05       0  5004.3    0.03       0  5010.3    0.05       0
Bank Sta=5004.3,5010.3
Exp/Cntr=0.3,0.1

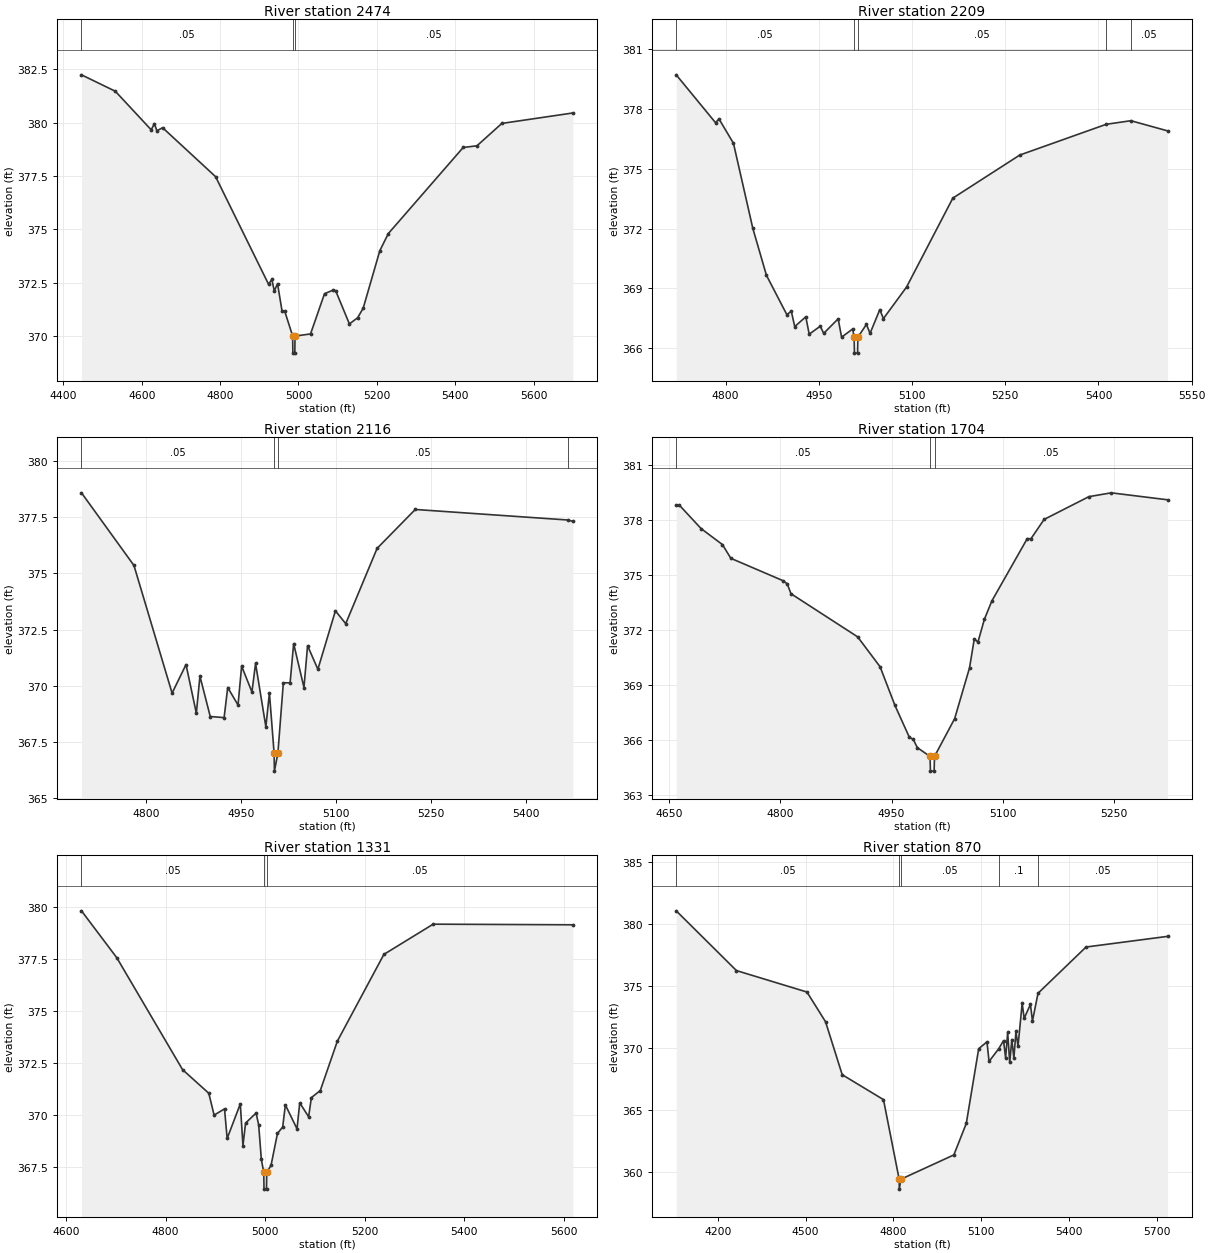
Type RM Length L Ch R = 1,2474,265,265,265
BEGIN DESCRIPTION:
UNT 104 in RCW 5.0
END DESCRIPTION:
XS GIS Cut Line= 3
      2042525.03     13439024.96      2042836.26     13438613.47
      2043380.25     13438114.37
#Sta/Elev= 30
  4446.2  382.25  4532.5  381.48  4624.1  379.67  4632.4  379.96  4638.6  379.62
  4653.2  379.77  4788.5  377.47  4923.7  372.42  4932.0  372.65  4938.3  372.11
  4946.6  372.45  4958.0  371.17  4964.7  371.17  4985.2  369.99  4985.7  369.19
  4990.7  369.19  4991.2  369.99  5030.8  370.09  5066.5  371.98  5087.5  372.14
  5094.9  372.12  5130.0  370.56  5151.0  370.85  5165.2  371.30  5207.7  374.00
  5229.3  374.80  5420.4  378.84  5455.6  378.92  5519.1  379.97  5700.4  380.46
#Mann=3,-1,0
  4446.2    0.05       0  4985.2    0.03       0  4991.2    0.05       0
Bank Sta=4985.2,4991.2
Exp/Cntr=0.3,0.1

Type RM Length L Ch R = 1,2209,93,93,93
BEGIN DESCRIPTION:
UNT 104 in RCW 4.0
END DESCRIPTION:
XS GIS Cut Line= 3
      2042652.26     13438945.70      2042925.00     13438825.00
      2043350.50     13438577.09
#Sta/Elev= 30
  4720.6  379.71  4783.9  377.31  4789.4  377.50  4812.7  376.28  4843.9  372.01
  4865.8  369.66  4898.6  367.69  4905.8  367.86  4911.3  367.09  4929.1  367.58
  4934.6  366.71  4952.4  367.11  4957.9  366.75  4981.2  367.48  4986.7  366.56
  5004.5  366.97  5006.9  366.56  5007.4  365.76  5012.4  365.76  5012.9  366.56
  5026.7  367.20  5032.5  366.75  5048.2  367.94  5054.0  367.49  5091.2  369.07
  5165.7  373.53  5273.5  375.69  5412.5  377.23  5452.2  377.41  5511.3  376.90
#Mann=5,-1,0
  4720.6    0.05       0  5006.9    0.04       0  5012.9    0.05       0
  5412.5    0.08       0  5452.2    0.05       0
Bank Sta=5006.9,5012.9
Exp/Cntr=0.3,0.1

Type RM Length L Ch R = 1,2116,412,412,412
BEGIN DESCRIPTION:
Mapping XS f9abba5f
END DESCRIPTION:
XS GIS Cut Line= 2
      2042643.57     13439067.23      2043329.28     13438702.67
#Sta/Elev= 30
  4697.3  378.58  4780.2  375.35  4840.5  369.67  4862.5  370.94  4878.8  368.78
  4884.5  370.42  4900.8  368.63  4922.7  368.58  4928.4  369.92  4944.7  369.14
  4950.4  370.87  4966.7  369.72  4972.4  370.99  4988.7  368.17  4994.3  369.68
  5001.7  367.00  5002.2  366.20  5007.7  367.00  5016.3  370.13  5027.0  370.13
  5032.6  371.87  5048.9  369.92  5054.6  371.78  5070.9  370.73  5098.6  373.33
  5114.9  372.76  5164.5  376.11  5224.8  377.84  5466.4  377.37  5473.9  377.31
#Mann=4,-1,0
  4697.3    0.05       0  5001.7    0.03       0  5007.7    0.05       0
  5466.4    0.08       0
Bank Sta=5001.7,5007.7
Exp/Cntr=0.3,0.1

Type RM Length L Ch R = 1,1704,373,373,373
BEGIN DESCRIPTION:
UNT 104 in RCW 3.0
END DESCRIPTION:
XS GIS Cut Line= 3
      2042491.68     13439232.18      2042964.73     13439288.60
      2043150.68     13439266.97
#Sta/Elev= 30
  4659.2  378.81  4663.4  378.81  4692.8  377.53  4721.6  376.66  4733.0  375.91
  4803.5  374.69  4809.1  374.52  4814.2  373.98  4904.2  371.63  4934.5  370.00
  4954.6  367.89  4974.1  366.15  4979.2  366.05  4984.8  365.59  5002.0  365.11
  5002.5  364.31  5007.5  364.31  5008.0  365.11  5035.2  367.17  5055.3  369.94
  5061.7  371.51  5066.7  371.35  5075.4  372.59  5085.5  373.59  5133.2  376.98
  5138.3  376.98  5156.0  378.03  5216.4  379.27  5246.6  379.48  5322.8  379.10
#Mann=3,-1,0
  4659.2    0.05       0  5002.0    0.03       0  5008.0    0.05       0
Bank Sta=5002,5008
Exp/Cntr=0.3,0.1

Type RM Length L Ch R = 1,1331,461,461,461
BEGIN DESCRIPTION:
UNT 104 in RCW 2.0
END DESCRIPTION:
XS GIS Cut Line= 3
      2042322.32     13439692.26      2042675.00     13439575.00
      2043238.12     13439327.68
#Sta/Elev= 30
  4631.3  379.80  4702.2  377.55  4834.3  372.18  4886.9  371.05  4897.6  370.00
  4918.5  370.30  4923.8  368.88  4950.2  370.54  4955.5  368.54  4960.8  369.62
  4981.9  370.10  4987.1  369.53  4992.4  367.88  4997.3  367.25  4997.8  366.45
  5002.8  366.45  5003.3  367.25  5011.9  367.59  5024.8  369.12  5035.3  369.43
  5040.7  370.49  5064.1  369.34  5069.5  370.59  5087.4  369.92  5092.9  370.84
  5110.8  371.18  5145.1  373.55  5238.5  377.71  5337.4  379.16  5618.0  379.13
#Mann=3,-1,0
  4631.3    0.05       0  4997.3    0.03       0  5003.3    0.05       0
Bank Sta=4997.3,5003.3
Exp/Cntr=0.3,0.1

Type RM Length L Ch R = 1,870,0,0,0
BEGIN DESCRIPTION:
UNT 104 in RCW 1.0
END DESCRIPTION:
XS GIS Cut Line= 4
      2042295.43     13439754.06      2042738.17     13440144.72
      2043280.70     13439584.82      2043337.13     13439281.00
#Sta/Elev= 30
  4058.0  381.08  4263.8  376.26  4504.7  374.53  4568.3  372.13  4625.2  367.86
  4766.2  365.85  4819.8  359.43  4820.3  358.63  4825.8  359.43  5006.7  361.39
  5049.2  363.93  5091.6  369.96  5119.9  370.51  5126.9  368.93  5160.2  369.96
  5176.5  370.61  5183.5  369.22  5190.6  371.27  5197.6  368.85  5204.8  370.70
  5211.8  369.20  5218.9  371.35  5225.9  370.15  5240.1  373.61  5247.0  372.41
  5268.3  373.53  5275.3  372.20  5294.3  374.43  5458.4  378.16  5737.1  379.02
#Mann=5,-1,0
  4058.0    0.05       0  4819.8    0.03       0  4825.8    0.05       0
  5160.2     0.1       0  5294.3    0.05       0
Bank Sta=4819.8,4825.8
Exp/Cntr=0.3,0.1

Chan Stop Cuts=-1