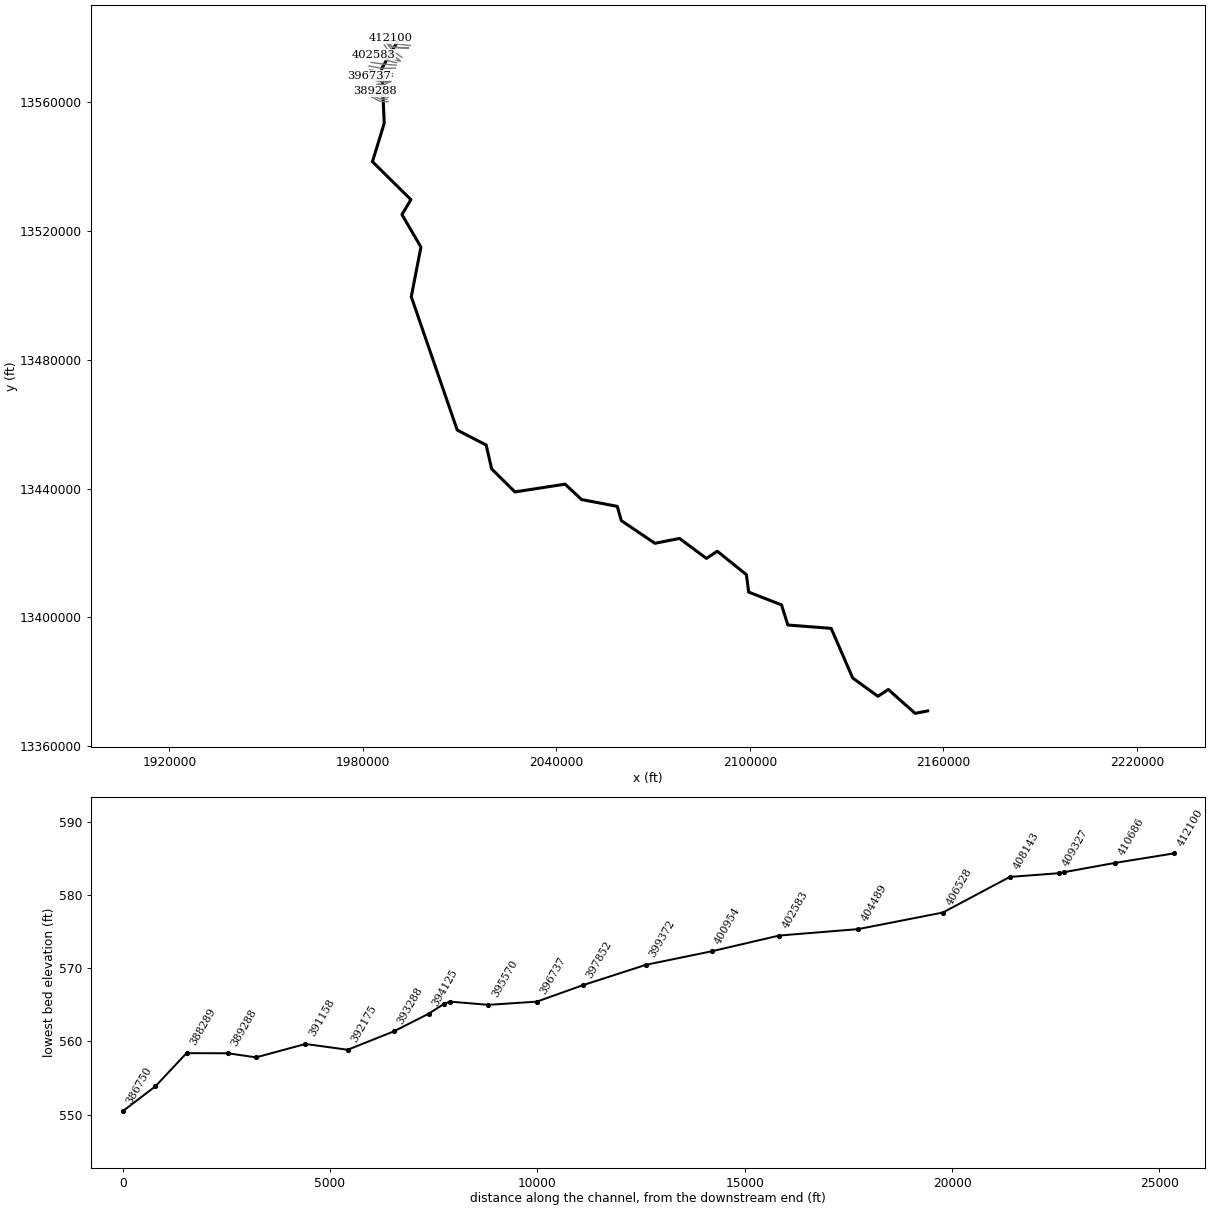
--- San Miguel Creek.prj (project) ---

Proj Title=San Miguel Creek Base Level Engineering
Current Plan=p01
Default Exp/Contr=0.3,0.1
English Units
Geom File=g01
Flow File=f01
Plan File=p01
Y Axis Title=Elevation
X Axis Title(PF)=Main Channel Distance
X Axis Title(XS)=Station
BEGIN DESCRIPTION:
San Miguel Creek
END DESCRIPTION:
DSS Export Rating Curves= 0
DSS Export Rating Curve Sorted= 0
DSS Export Volume Flow Curves= 0
DXF OffsetX= 0
DXF OffsetY= 0
DXF ScaleX= 1
DXF ScaleY= 10

--- San Miguel Creek.p01 (plan) ---

Plan Title=Multiple Run
Short Identifier=Multiple
Geom File=g01
Flow File=f01
Subcritical Flow
K Sum by GR= 0
Std Step Tol= 0.01
Critical Tol= 0.01
Num of Std Step Trials= 20
Max Error Tol= 0.3
Flow Tol Ratio= 0.001
Split Flow NTrial= 30
Split Flow Tol= 0.02
Split Flow Ratio= 0.02
Log Output Level= 0
Friction Slope Method= 1
Unsteady Friction Slope Method= 2
Unsteady Bridges Friction Slope Method= 1
Parabolic Critical Depth
Global Vel Dist=  1 , 1 , 1
Global Log Level= 0
CheckData=True
Encroach Param= -1, 0, 0, 0
BEGIN DESCRIPTION:
Multiple Run
END DESCRIPTION:

--- San Miguel Creek.f01 (steady flow) ---

Flow Title=Multiple
Program Version=5.07
BEGIN FILE DESCRIPTION:
Gage 08206700 analysis results and adjusted with 1996-4307 regression equation flows, see spreadsheet for details.
END FILE DESCRIPTION:
Number of Profiles= 7
Profile Names=10-year,25-year,50-year,1pct_min,100-year,1pct_plu,500-year
River Rch & RM=San Miguel Creek,Reach-1         ,412100
    4350    7660   11000    8050   15700   30600   35800
River Rch & RM=San Miguel Creek,Reach-1         ,410686
    5870   10300   14800    9860   19200   37500   35800
River Rch & RM=San Miguel Creek,Reach-1         ,296851
    7050   12300   17600   12000   23400   45600   45500
River Rch & RM=San Miguel Creek,Reach-1         ,292935
    8070   13900   19800   13100   25500   49600   46000
River Rch & RM=San Miguel Creek,Reach-1         ,239193
    8890   15100   21100   13700   26800   52200   46500
River Rch & RM=San Miguel Creek,Reach-1         ,191995
   10000   16600   22800   14500   28300   55200   46800
River Rch & RM=San Miguel Creek,Reach-1         ,113058
   12200   19200   25200   16100   31300   61000   48200
River Rch & RM=San Miguel Creek,Reach-1         ,68755
   12700   20300   27100   16900   32900   64200   48500
Boundary for River Rch & Prof#=San Miguel Creek,Reach-1         , 1
Up Type= 0
Dn Type= 3
Dn Slope=0.0001
Boundary for River Rch & Prof#=San Miguel Creek,Reach-1         , 2
Up Type= 0
Dn Type= 3
Dn Slope=0.0001
Boundary for River Rch & Prof#=San Miguel Creek,Reach-1         , 3
Up Type= 0
Dn Type= 3
Dn Slope=0.0001
Boundary for River Rch & Prof#=San Miguel Creek,Reach-1         , 4
Up Type= 0
Dn Type= 3
Dn Slope=0.0001
Boundary for River Rch & Prof#=San Miguel Creek,Reach-1         , 5
Up Type= 0
Dn Type= 3
Dn Slope=0.0001
Boundary for River Rch & Prof#=San Miguel Creek,Reach-1         , 6
Up Type= 0
Dn Type= 3
Dn Slope=0.0001
Boundary for River Rch & Prof#=San Miguel Creek,Reach-1         , 7
Up Type= 0
Dn Type= 3
Dn Slope=0.0001
DSS Import GetInterval= 0
DSS Import GetPeak= 0
DSS Import FillOption= 0

--- San Miguel Creek.g01 (geometry) ---

Geom Title=Existing Conditions
Program Version=5.07

River Reach=San Miguel Creek,Reach-1
Reach XY= 30
       1990930.8     13579164.54       1985830.8     13570444.54
      1986607.83      13553456.7       1982950.8     13541504.54
       1994880.8     13529724.54       1992100.8     13525084.54
       1997980.8     13515004.54      1994990.34     13499573.07
       2009240.8     13458184.54       2018220.8     13453534.54
       2019910.8     13446134.54       2027130.8     13438984.54
       2042690.8     13441394.54       2047810.8     13436604.54
      2058867.62     13434504.47       2060140.8     13430064.54
       2070540.8     13423034.54       2078170.8     13424534.54
       2086530.8     13418344.54       2089890.8     13420574.54
       2098920.8     13413294.54       2099630.8     13407884.54
       2109810.8     13403914.54       2111770.8     13397664.54
       2125210.8     13396624.54       2131890.8     13381204.54
       2139711.1     13375536.34       2142916.4     13377648.97
      2151254.17     13370232.41      2155128.48     13370999.29

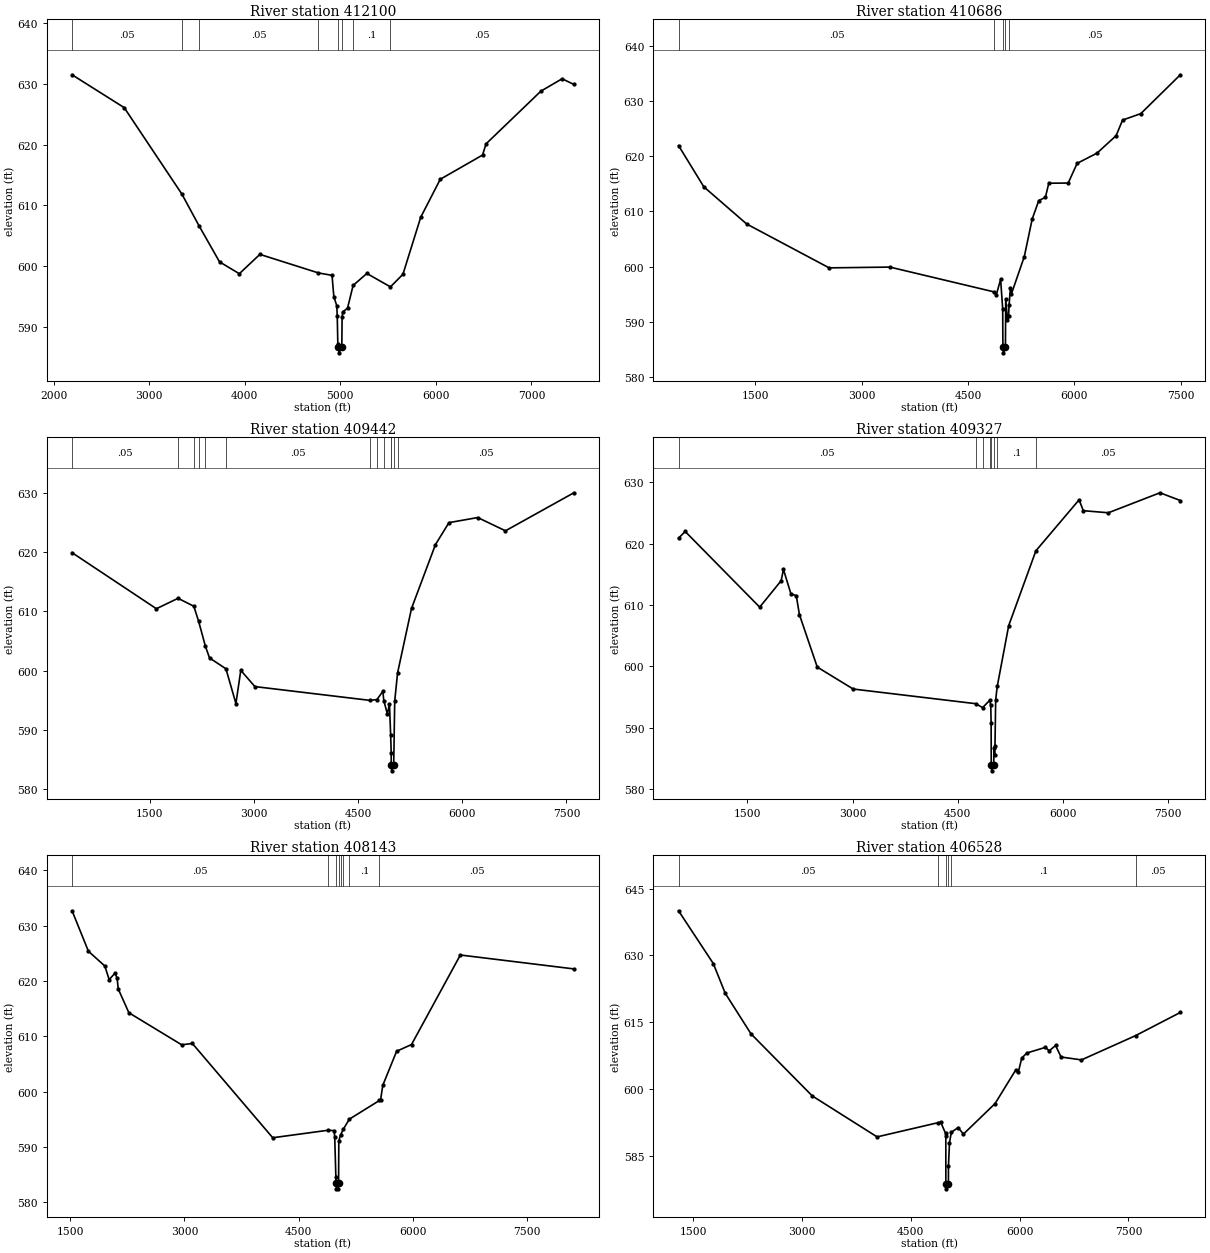
Type RM Length L Ch R = 1 ,412100  ,1414,1414,1414
BEGIN DESCRIPTION:
San Miguel Creek 228.0
END DESCRIPTION:
XS GIS Cut Line= 3
      1993700.01       13578700.       1990930.8     13579164.54
      1988569.11      13579796.2
#Sta/Elev= 30
  2192.1  631.52  2737.9   626.1  3341.8  611.84  3521.2  606.61  3735.9  600.66
  3943.1  598.71  4157.9   601.9  4770.8  598.84  4913.4  598.44  4932.4   594.9
  4962.8  593.44  4967.9  591.76    4974  587.07  4980.2  586.66  4987.5  585.66
  5015.6  586.66  5018.8  591.49  5024.1  592.36  5075.9  593.05    5134  596.78
  5277.7  598.75  5524.8  596.54  5655.6  598.62  5841.9  608.03  6046.5  614.29
  6488.9  618.28  6525.1  620.12  7099.6  628.82  7321.7  630.86  7444.7  629.93
#Mann= 8 ,-1 , 0
  2192.1     .05       0  3341.8     .12       0  3521.2     .05       0
  4770.8     .12       0  4980.2     .07       0  5015.6     .12       0
    5134      .1       0  5524.8     .05       0
Bank Sta=4980.2,5015.6
XS Rating Curve= 0 ,0
Exp/Cntr=0.3,0.1

Type RM Length L Ch R = 1 ,410686  ,1244,1244,1244
BEGIN DESCRIPTION:
San Miguel Creek 227.0
END DESCRIPTION:
XS GIS Cut Line= 3
      1994668.59     13577563.61       1990115.5       13578095.
      1987904.73     13579247.41
#Sta/Elev= 30
     416  621.91   772.5  614.44  1376.5  607.71  2540.2  599.76  3397.2   599.9
    4869   595.4  4897.3  594.86  4958.5  597.67  4987.9  592.34  4990.7  585.37
  4998.1  584.37  5026.4  585.37  5030.6  594.14  5055.5  590.26    5071  590.99
  5077.8  593.04  5096.9  596.09  5110.7  595.04  5292.9  601.81  5403.7   608.6
  5497.2  611.96  5589.8  612.52    5638  615.09  5911.3  615.12  6038.2  618.69
    6317  620.53  6587.5   623.7  6678.7  626.53  6935.4  627.69  7493.1  634.73
#Mann= 5 ,-1 , 0
     416     .05       0    4869     .12       0  4990.7     .07       0
  5026.4     .12       0  5077.8     .05       0
Bank Sta=4990.7,5026.4
XS Rating Curve= 0 ,0
Exp/Cntr=0.3,0.1

Type RM Length L Ch R = 1 ,409442  ,115,115,115
BEGIN DESCRIPTION:
San Miguel Creek 226.0
END DESCRIPTION:
XS GIS Cut Line= 6
      1994164.63     13576879.14      1991628.04     13576943.75
      1990218.16     13577038.15      1989555.98     13577085.22
      1989178.22      13577131.9      1987623.05     13578724.77
#Sta/Elev= 30
   385.7  619.91  1599.2  610.45  1910.8  612.21  2137.9  610.87  2206.2  608.36
  2304.7  604.11  2363.5  602.15  2600.1  600.31  2743.6  594.45  2813.6  600.05
  3016.5  597.31  4673.9  594.98  4772.8  595.12  4858.3  596.51  4871.6  594.93
  4923.3  592.71  4953.4  594.37  4970.4  589.11  4978.4  586.13  4978.6  584.09
    4986  583.09  5014.3  584.09  5028.7  594.84  5069.7  599.61  5270.5   610.5
  5614.9  621.27  5809.4  624.98  6223.1  625.84  6622.6   623.6  7606.8  630.02
#Mann= 13 ,-1 , 0
   385.7     .05       0  1910.8     .08       0  2137.9     .05       0
  2206.2      .1       0  2304.7     .08       0  2600.1     .05       0
  4673.9     .07       0  4772.8     .12       0  4871.6     .16       0
  4970.4     .12       0  4978.6     .07       0  5014.3     .12       0
  5069.7     .05       0
Bank Sta=4978.6,5014.3
XS Rating Curve= 0 ,0
Exp/Cntr=0.3,0.1

Type RM Length L Ch R = 1 ,409327  ,1184,1184,1184
BEGIN DESCRIPTION:
Mapping XS 7335b55c
END DESCRIPTION:
XS GIS Cut Line= 5
      1994012.13     13576672.07      1990195.59     13576909.67
      1989542.28     13576973.98      1989096.98     13577011.25
      1987538.28     13578598.69
#Sta/Elev= 30
   519.6   620.9   614.4  621.99  1676.5  609.65  1982.1  613.96  2014.9   615.8
  2122.3  611.79  2197.5  611.54  2242.6  608.43  2496.8  599.88    3009   596.3
  4754.7  593.91  4853.9  593.27    4953  594.44  4969.6  593.72  4974.7  590.81
  4976.9  583.96  4984.3  582.96  5012.6  583.96  5014.8  586.67  5024.9  585.58
  5029.9  586.98  5039.9  594.56  5062.1  596.72  5225.6  606.65  5613.1  618.84
  6228.7  627.15  6288.9  625.38    6646  625.04  7381.4   628.3  7671.6  627.04
#Mann= 8 ,-1 , 0
   519.6     .05       0  4754.7     .07       0  4853.9     .12       0
    4953     .16       0  4976.9     .07       0  5012.6     .16       0
  5062.1      .1       0  5613.1     .05       0
Bank Sta=4976.9,5012.6
XS Rating Curve= 0 ,0
Exp/Cntr=0.3,0.1

Type RM Length L Ch R = 1 ,408143  ,1615,1615,1615
BEGIN DESCRIPTION:
San Miguel Creek 225.0
END DESCRIPTION:
XS GIS Cut Line= 3
      1992106.07     13573881.93      1989260.15     13575876.19
      1987340.24     13578327.66
#Sta/Elev= 30
  1524.9  632.68  1739.6  625.37  1955.4   622.7    2012  620.24  2087.9  621.41
  2116.2  620.53    2131  618.56  2270.9  614.26    2964  608.47  3104.3  608.71
  4159.6  591.68  4884.9  593.03  4966.6  592.96  4973.8  591.75  4988.6  584.67
  4988.7  583.45  4996.1  582.45    5017  582.45  5024.4  583.45  5027.4  591.13
  5051.1   592.2  5085.9   593.2  5165.3  595.03  5560.8  598.41  5576.2  598.54
    5605  601.15  5786.4   607.3  5982.2  608.52  6623.2  624.69  8113.8  622.18
#Mann= 8 ,-1 , 0
  1524.9     .05       0  4884.9     .12       0  4988.7     .07       0
  5024.4     .12       0  5051.1      .1       0  5085.9     .07       0
  5165.3      .1       0  5560.8     .05       0
Bank Sta=4988.7,5024.4
XS Rating Curve= 0 ,0
Exp/Cntr=0.3,0.1

Type RM Length L Ch R = 1 ,406528  ,2039,2039,2039
BEGIN DESCRIPTION:
San Miguel Creek 224.0
END DESCRIPTION:
XS GIS Cut Line= 3
      1991425.44     13572963.45       1988400.8     13575094.54
      1986628.94     13577776.25
#Sta/Elev= 30
    1300     640  1778.9  628.16  1943.9  621.47  2299.3  612.36  3142.3  598.45
  4035.9  589.25    4874  592.43  4911.6  592.57  4979.6  590.04    4983  589.41
  4983.2  578.59  4990.6  577.59  5018.9  578.59  5019.1  582.64  5033.5  587.95
  5059.1  590.28    5153  591.35  5225.2  589.87  5661.7  596.73  5943.1  604.19
  5982.2  603.81  6028.8  606.92  6098.1  608.07  6353.9  609.34  6408.1  608.57
  6495.4  609.77  6570.6  607.18    6852  606.53  7596.6  611.97  8214.2  617.18
#Mann= 6 ,-1 , 0
    1300     .05       0    4874     .12       0  4983.2     .07       0
  5018.9     .12       0  5059.1      .1       0  7596.6     .05       0
Bank Sta=4983.2,5018.9
XS Rating Curve= 0 ,0
Exp/Cntr=0.3,0.1

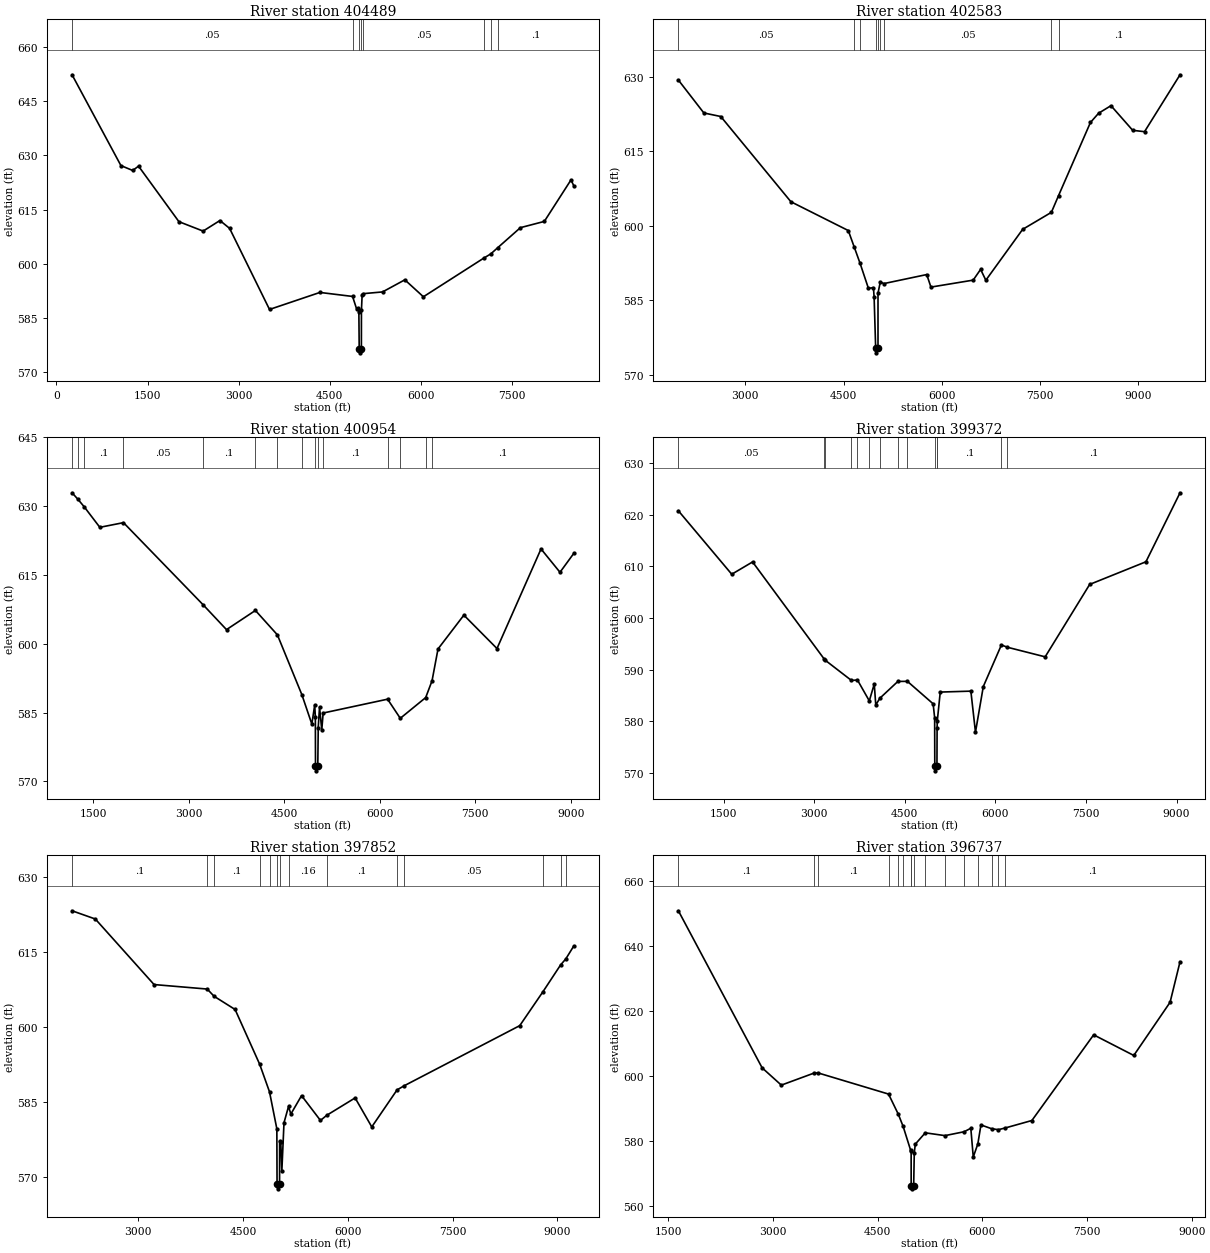
Type RM Length L Ch R = 1 ,404489  ,1906,1906,1906
BEGIN DESCRIPTION:
San Miguel Creek 223.0
END DESCRIPTION:
XS GIS Cut Line= 3
      1991555.67     13572650.93        1987025.       13574125.
      1983904.45     13575709.68
#Sta/Elev= 30
   256.4   652.3  1061.5  627.16  1255.7  625.81  1351.5  627.01  2016.7  611.64
  2415.5  609.03  2692.6  611.96  2851.9  609.78  3509.2  587.34  4339.7  592.05
  4877.6  590.94  4944.6  587.45  4972.9  587.75  4981.4  586.54    4987  576.33
  4994.4  575.33  5022.7  576.33  5023.6  587.12  5034.9   591.3  5051.8  591.71
  5371.3  592.19  5738.6  595.54  6044.3  590.85  7041.8  601.58  7153.9  602.71
    7266  604.39  7642.5  609.98  8036.7  611.71  8476.2  623.21  8520.7  621.61
#Mann= 8 ,-1 , 0
   256.4     .05       0  4877.6     .12       0    4987     .07       0
  5022.7     .12       0  5051.8     .05       0  7041.8      .1       0
  7153.9     .08       0    7266      .1       0
Bank Sta=4987,5022.7
XS Rating Curve= 0 ,0
Exp/Cntr=0.3,0.1

Type RM Length L Ch R = 1 ,402583  ,1629,1629,1629
BEGIN DESCRIPTION:
San Miguel Creek 222.0
END DESCRIPTION:
XS GIS Cut Line= 3
      1990465.73     13572238.08       1987510.8     13572874.54
      1983261.02      13574739.8
#Sta/Elev= 30
  1977.3   629.3  2366.6  622.68    2625  621.97  3696.4  604.83    4573  599.04
    4666  595.64  4753.4  592.44  4880.6  587.42  4957.3  587.56  4967.6  585.67
  4991.2  575.45  4998.6  574.45    5027  575.45  5027.1  586.45  5061.6  588.67
  5118.7  588.38  5771.6  590.19  5835.5  587.67  6481.1  589.07  6594.4  591.23
  6674.5  589.05  7236.9  599.28  7675.8   602.7  7784.7  606.05  8272.4  620.77
  8397.4  622.63  8586.2  624.15    8918  619.19  9098.9  618.92  9641.1  630.36
#Mann= 9 ,-1 , 0
  1977.3     .05       0    4666      .1       0  4753.4     .12       0
  4991.2     .07       0    5027     .12       0  5061.6      .1       0
  5118.7     .05       0  7675.8     .08       0  7784.7      .1       0
Bank Sta=4991.2,5027
XS Rating Curve= 0 ,0
Exp/Cntr=0.3,0.1

Type RM Length L Ch R = 1 ,400954  ,1582,1582,1582
BEGIN DESCRIPTION:
San Miguel Creek 220.0
END DESCRIPTION:
XS GIS Cut Line= 3
      1990348.56     13571436.46       1986530.8     13571774.54
      1982524.05     13572335.34
#Sta/Elev= 30
  1167.3  632.91    1262  631.45    1361   629.8  1603.4  625.38  1974.9   626.4
  3223.9  608.52  3592.8  603.08  4046.8  607.26    4392  601.94  4776.7  588.89
    4933  582.49  4978.2  586.66  4988.3  584.03  4990.5   573.3  4997.9   572.3
  5026.3   573.3  5033.6  581.72  5053.8   586.2  5089.2   581.2  5110.4   584.9
  6122.5  587.92    6322  583.75  6721.1  588.27  6820.8  591.93  6914.7  598.87
  7320.7  606.24  7840.7  598.96  8532.4  620.67  8830.3  615.58  9045.8  619.68
#Mann= 15 ,-1 , 0
  1167.3      .1       0    1262     .05       0    1361      .1       0
  1974.9     .05       0  3223.9      .1       0  4046.8     .05       0
    4392      .1       0  4776.7     .12       0  4990.5     .07       0
  5026.3     .12       0  5110.4      .1       0  6122.5     .12       0
    6322      .1       0  6721.1     .08       0  6820.8      .1       0
Bank Sta=4990.5,5026.3
XS Rating Curve= 0 ,0
Exp/Cntr=0.3,0.1

Type RM Length L Ch R = 1 ,399372  ,1520,1520,1520
BEGIN DESCRIPTION:
San Miguel Creek 219.0
END DESCRIPTION:
XS GIS Cut Line= 3
      1990101.37     13570558.56       1985850.8     13570474.54
      1981860.86       13571213.
#Sta/Elev= 30
   748.6  620.74  1632.6  608.47  1977.7  610.85    3163  592.09  3180.5  591.85
    3616  587.93  3714.3  588.03  3910.9  583.99  3993.1  587.25  4018.1   583.2
    4086   584.5  4384.5  587.75  4542.4  587.76  4968.3  583.42  4993.3  580.72
  4995.6  571.46  5003.1  570.46  5031.4  571.46  5033.9  578.82  5037.2  580.12
  5086.1  585.69  5593.2  585.87  5669.5  577.93  5799.2  586.76  6099.1   594.8
  6199.7  594.35  6823.8   592.5  7561.1   606.5  8492.9  610.88  9057.7  624.22
#Mann= 14 ,-1 , 0
   748.6     .05       0    3163      .1       0  3180.5     .05       0
    3616      .1       0  3714.3     .16       0  3910.9      .1       0
    4086     .05       0  4384.5      .1       0  4542.4     .12       0
  4995.6     .07       0  5031.4     .12       0  5037.2      .1       0
  6099.1     .08       0  6199.7      .1       0
Bank Sta=4995.6,5031.4
XS Rating Curve= 0 ,0
Exp/Cntr=0.3,0.1

Type RM Length L Ch R = 1 ,397852  ,1115,1115,1115
BEGIN DESCRIPTION:
San Miguel Creek 217.0
END DESCRIPTION:
XS GIS Cut Line= 3
      1989205.97     13568868.76       1986270.8     13569144.54
      1982144.41     13570085.87
#Sta/Elev= 30
  2051.9  623.31  2385.1  621.66  3225.5  608.55  3986.2  607.65  4085.3   606.2
  4385.6  603.56  4737.5   592.6    4878  587.09  4983.2  579.68  4986.1  568.68
  4993.5  567.68    5022  568.68  5022.9   577.2  5039.3  577.06  5054.7  571.28
  5085.4   580.9  5150.3  584.16  5183.7  582.64  5336.7  586.33  5607.5  581.36
  5696.8  582.39  6103.5  585.87  6341.9  580.07    6704  587.48  6805.6   588.3
    8460  600.33  8794.2  607.16  9044.3  612.47    9119  613.68  9232.4  616.24
#Mann= 14 ,-1 , 0
  2051.9      .1       0  3986.2     .08       0  4085.3      .1       0
  4737.5     .16       0    4878     .12       0  4986.1     .07       0
    5022     .12       0  5150.3     .16       0  5696.8      .1       0
    6704     .08       0  6805.6     .05       0  8794.2      .1       0
  9044.3     .05       0    9119      .1       0
Bank Sta=4986.1,5022
XS Rating Curve= 0 ,0
Exp/Cntr=0.3,0.1

Type RM Length L Ch R = 1 ,396737  ,1167,1167,1167
BEGIN DESCRIPTION:
San Miguel Creek 216.0
END DESCRIPTION:
XS GIS Cut Line= 3
       1989137.3     13568152.81      1985783.51     13568211.15
      1981949.89     13568248.29
#Sta/Elev= 30
  1645.7  650.96  2845.7  602.65  3120.7  597.33  3595.1  601.08  3652.7  601.05
  4657.1  594.58  4797.5  588.36  4866.4  584.62  4973.5  577.31    4981  576.99
  4981.3  566.43  4988.8  565.43  5017.2  566.43    5026  576.58    5041  579.19
  5183.5  582.66    5466   581.8  5739.6  582.99    5836  584.06    5871  575.23
  5936.4  579.23  5981.1  585.09  6133.2  583.93  6231.6  583.63    6330  584.16
  6711.1  586.45  7596.1   612.8  8171.2  606.46  8691.2  622.81  8833.8  635.29
#Mann= 16 ,-1 , 0
  1645.7      .1       0  3595.1     .08       0  3652.7      .1       0
  4657.1     .12       0  4797.5     .16       0  4866.4     .12       0
  4973.5      .1       0  4981.3     .07       0  5017.2      .1       0
  5183.5     .05       0    5466      .1       0  5739.6     .12       0
  5936.4     .05       0  6133.2      .1       0  6231.6     .08       0
    6330      .1       0
Bank Sta=4981.3,5017.2
XS Rating Curve= 0 ,0
Exp/Cntr=0.3,0.1

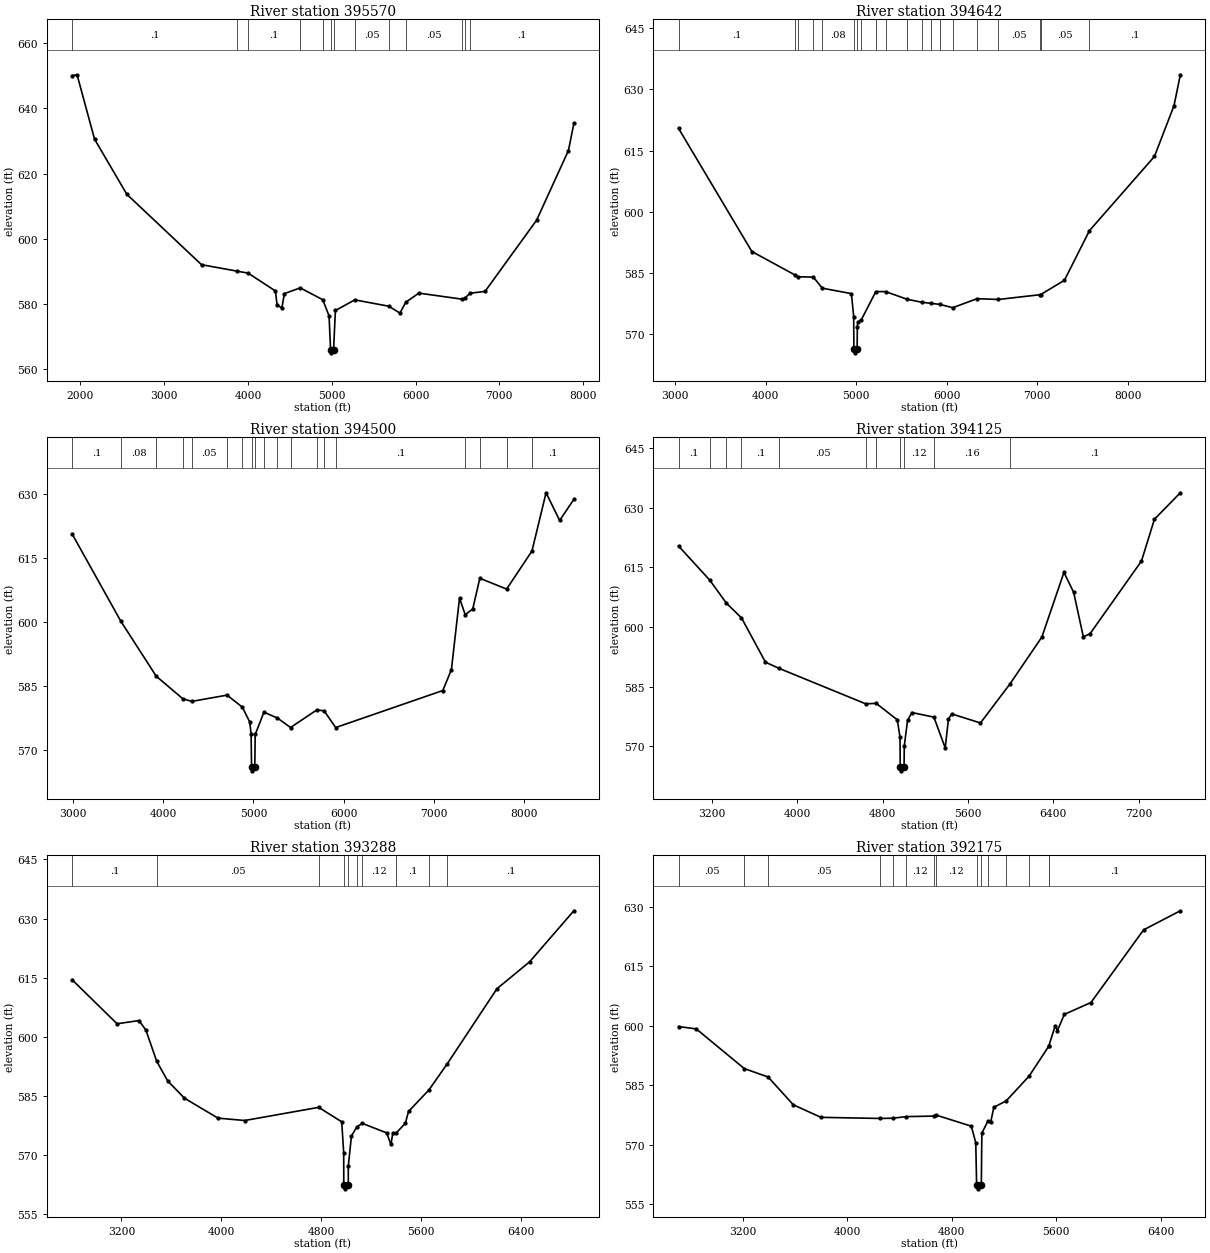
Type RM Length L Ch R = 1 ,395570  ,928,928,928
BEGIN DESCRIPTION:
San Miguel Creek 215.0
END DESCRIPTION:
XS GIS Cut Line= 3
      1989059.19     13567987.89      1986036.54      13567308.8
      1983147.74     13567310.79
#Sta/Elev= 30
    1902  650.08  1961.7  650.34  2170.2  630.58  2555.5  613.65  3446.3  592.05
  3865.8  590.09  4003.1  589.45  4327.7  583.99  4348.2  579.68  4404.6  578.75
  4435.3  583.17  4624.4  584.93  4893.1  581.29  4968.3  576.31  4986.1  565.99
  4993.5  564.99    5022  565.99    5044  577.99  5275.5  581.25  5680.5   579.3
    5814  577.19  5881.8  580.48    6039  583.32  6554.2  581.47  6585.5  581.73
  6652.6   583.3    6829  583.84    7444  605.69    7824  627.09  7888.8  635.39
#Mann= 13 ,-1 , 0
    1902      .1       0  3865.8     .05       0  4003.1      .1       0
  4624.4     .16       0  4893.1     .12       0  4986.1     .07       0
    5022     .12       0  5275.5     .05       0  5680.5      .1       0
  5881.8     .05       0  6554.2     .08       0  6585.5     .05       0
  6652.6      .1       0
Bank Sta=4986.1,5022
XS Rating Curve= 0 ,0
Exp/Cntr=0.3,0.1

Type RM Length L Ch R = 1 ,394642  ,142,142,142
BEGIN DESCRIPTION:
San Miguel Creek 214.0
END DESCRIPTION:
XS GIS Cut Line= 6
      1988624.97     13566774.99      1987908.75     13566596.99
      1987240.35     13566614.35      1986690.91     13566679.33
      1984403.77     13567079.89      1983152.92     13567196.21
#Sta/Elev= 30
  3040.1  620.44  3849.4  590.26  4330.3  584.45    4360  584.07    4528  583.99
  4627.4  581.27  4948.1  579.94  4973.2  574.33  4975.4  566.43  4982.9  565.43
  5011.3  566.43  5013.6  571.83  5018.7  572.96  5057.7  573.54    5218  580.45
    5326  580.43  5562.1  578.56    5727  577.82  5827.3  577.56  5927.5  577.29
  6066.4  576.49  6334.1   578.7  6570.8  578.51  7031.9  579.68  7035.4  579.69
  7299.4  583.21  7575.4  595.37  8292.7  613.55  8508.6  625.99  8578.5  633.57
#Mann= 20 ,-1 , 0
  3040.1      .1       0  4330.3     .08       0    4360     .16       0
    4528      .1       0  4627.4     .08       0  4975.4     .07       0
  5011.3     .08       0  5057.7     .16       0    5218     .12       0
    5326     .08       0  5562.1     .16       0    5727      .1       0
  5827.3     .08       0  5927.5     .05       0  6066.4      .1       0
  6334.1     .08       0  6570.8     .05       0  7031.9     .08       0
  7035.4     .05       0  7575.4      .1       0
Bank Sta=4975.4,5011.3
XS Rating Curve= 0 ,0
Exp/Cntr=0.3,0.1

Type RM Length L Ch R = 1 ,394500  ,375,375,375
BEGIN DESCRIPTION:
Mapping XS 1f2e739d
END DESCRIPTION:
XS GIS Cut Line= 6
      1988646.59     13566714.18      1987900.07      13566458.1
      1987305.45      13566458.1      1986684.79     13566540.57
      1984393.12     13566909.49      1983160.53     13567035.36
#Sta/Elev= 30
  2986.6  620.69  3526.4  600.26  3920.8  587.32  4216.2  582.03  4314.8  581.41
    4707  582.88    4877  580.07  4959.1  576.57  4974.2  573.72  4979.1  566.13
  4986.5  565.13    5015  566.13  5019.7  573.65  5116.5  578.88  5266.9   577.5
  5412.3  575.29  5704.8  579.43  5785.5  579.18    5913  575.28  7102.5  583.96
  7197.8  588.85    7288  605.62  7350.9  601.75  7434.5  603.07  7513.3  610.28
  7810.8  607.74  8092.1  616.67  8248.7  630.32  8399.5  623.83  8557.3  628.78
#Mann= 19 ,-1 , 0
  2986.6      .1       0  3526.4     .08       0  3920.8     .05       0
  4216.2     .08       0  4314.8     .05       0    4707     .08       0
    4877     .12       0  4979.1     .07       0    5015     .12       0
  5116.5     .16       0  5266.9     .08       0  5412.3      .1       0
  5704.8     .16       0  5785.5     .08       0    5913      .1       0
  7350.9     .08       0  7513.3      .1       0  7810.8     .08       0
  8092.1      .1       0
Bank Sta=4979.1,5015
XS Rating Curve= 0 ,0
Exp/Cntr=0.3,0.1

Type RM Length L Ch R = 1 ,394125  ,837,837,837
BEGIN DESCRIPTION:
San Miguel Creek 213.0
END DESCRIPTION:
XS GIS Cut Line= 4
      1988663.95     13566653.41      1987904.41     13566358.28
        1986625.       13566175.      1984067.65     13566605.66
#Sta/Elev= 30
  2888.4  620.41  3182.1  611.76    3337     606  3478.2   602.3    3703  591.13
  3833.2  589.55  4641.7  580.65  4740.7  580.76  4937.7  576.62    4963  572.26
  4965.2  564.77  4972.6  563.77  5001.1  564.77  5003.3  570.08  5033.8  576.46
  5074.3  578.46  5280.6  577.29  5386.7  569.55  5416.9   576.8  5447.2  578.11
    5717  575.83  5991.5   585.6  6292.1  597.47  6498.9  613.75  6589.7  608.75
  6680.5  597.53  6743.5  598.31  7225.3  616.62  7346.3  627.14  7589.1  633.81
#Mann= 11 ,-1 , 0
  2888.4      .1       0  3182.1     .05       0    3337     .08       0
  3478.2      .1       0  3833.2     .05       0  4641.7     .08       0
  4740.7     .12       0  4965.2     .07       0  5001.1     .12       0
  5280.6     .16       0  5991.5      .1       0
Bank Sta=4965.2,5001.1
XS Rating Curve= 0 ,0
Exp/Cntr=0.3,0.1

Type RM Length L Ch R = 1 ,393288  ,1113,1113,1113
BEGIN DESCRIPTION:
San Miguel Creek 212.0
END DESCRIPTION:
XS GIS Cut Line= 3
      1988594.52     13566384.32      1986599.83     13565469.42
      1984784.42     13565642.07
#Sta/Elev= 30
  2805.5  614.47  3165.8  603.28  3341.1  604.09  3396.3  601.71  3482.9  593.79
  3570.5   588.8  3705.2  584.39  3973.9  579.32  4188.4  578.72  4780.3  582.06
  4964.7  578.39  4980.6   570.5  4981.2  562.37  4988.7  561.37  5017.2  562.37
  5017.4  567.13  5042.5  574.78  5087.1  577.17  5131.1  577.97  5324.7  575.57
  5358.9  572.64  5373.7  575.49  5400.9  575.54  5474.5  578.04  5499.6  581.01
  5663.8  586.51  5809.8  593.12  6207.8  612.18  6468.9     619  6823.6  631.97
#Mann= 10 ,-1 , 0
  2805.5      .1       0  3482.9     .05       0  4780.3     .12       0
  4981.2     .07       0  5017.2     .12       0  5087.1     .16       0
  5131.1     .12       0  5400.9      .1       0  5663.8     .05       0
  5809.8      .1       0
Bank Sta=4981.2,5017.2
XS Rating Curve= 0 ,0
Exp/Cntr=0.3,0.1

Type RM Length L Ch R = 1 ,392175  ,1017,1017,1017
BEGIN DESCRIPTION:
San Miguel Creek 211.0
END DESCRIPTION:
XS GIS Cut Line= 4
      1988455.61     13564570.08      1986580.62     13564778.42
      1986199.83     13564915.95      1984779.69      13565533.5
#Sta/Elev= 30
  2708.6  599.81  2844.4  599.21  3211.9   589.2    3394  587.08  3587.1  580.06
  3798.4   576.9    4250  576.62  4349.3  576.68  4448.6  577.08  4660.1  577.22
  4676.6   577.5  4949.3  574.67  4983.2  570.49  4989.7  559.86  4997.2  558.86
  5025.7  559.86  5029.8   572.9  5075.8  575.95  5097.9  575.74  5121.4  579.45
  5215.6  581.03  5391.6  587.31  5540.8   594.8  5541.2  594.82  5591.4  600.06
  5607.7  598.75  5660.8  602.88  5864.7  605.87  6267.5   624.2  6548.6  629.02
#Mann= 15 ,-1 , 0
  2708.6     .05       0  3211.9      .1       0    3394     .05       0
    4250      .1       0  4349.3     .05       0  4448.6     .12       0
  4660.1      .1       0  4676.6     .12       0  4989.7     .07       0
  5025.7     .12       0  5075.8      .1       0  5215.6     .05       0
  5391.6      .1       0  5540.8     .05       0  5541.2      .1       0
Bank Sta=4989.7,5025.7
XS Rating Curve= 0 ,0
Exp/Cntr=0.3,0.1

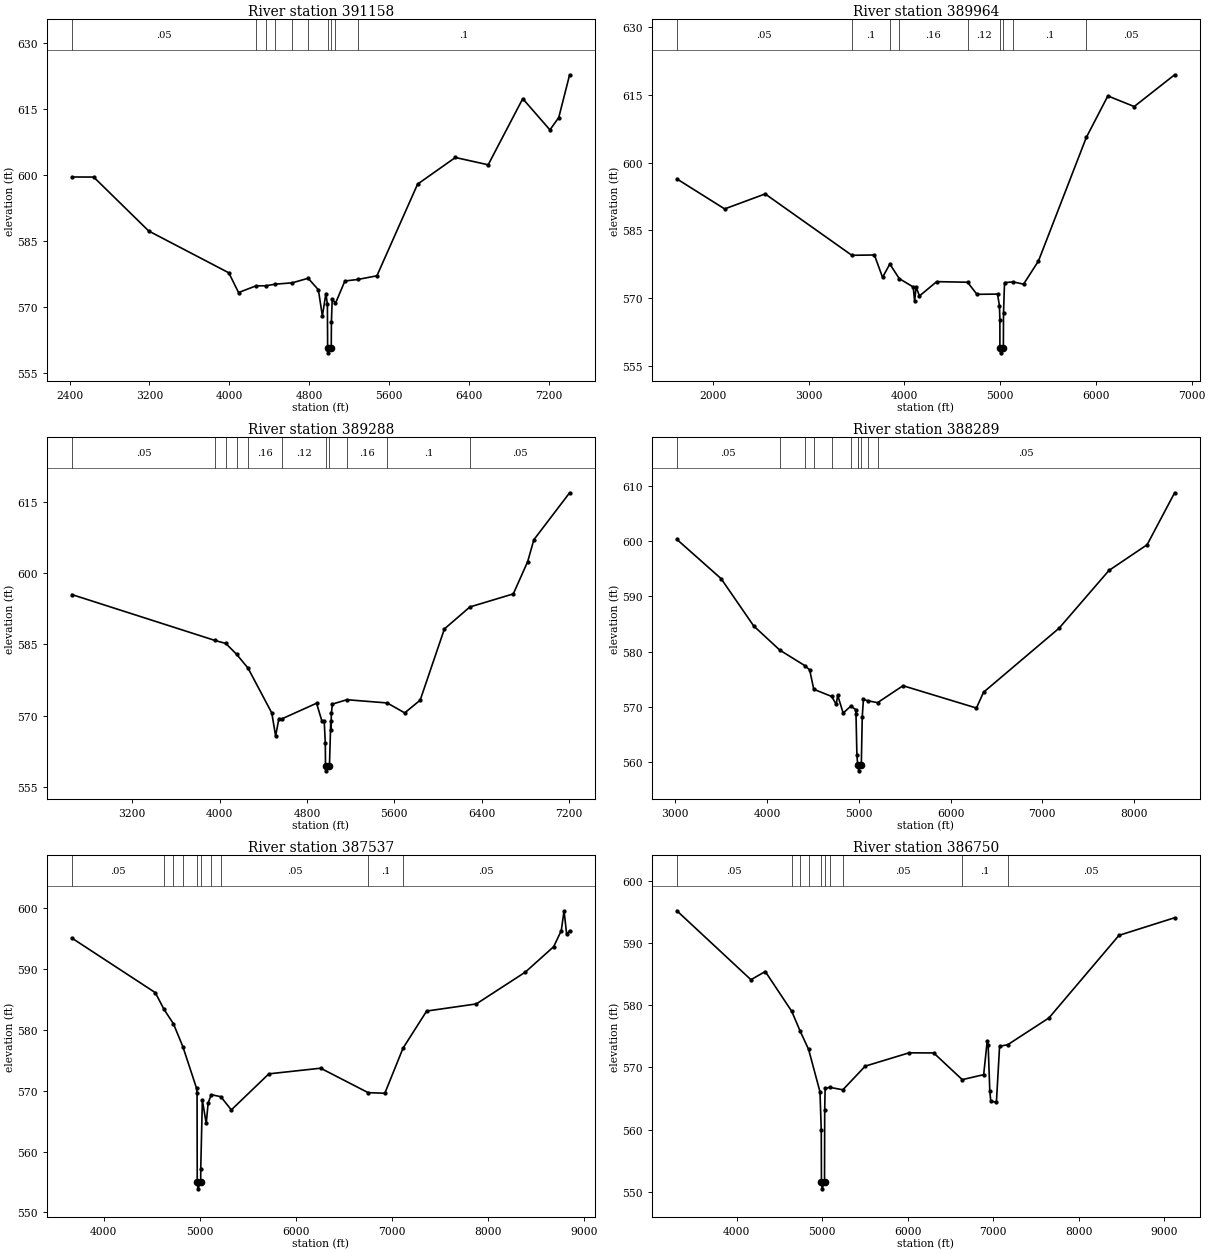
Type RM Length L Ch R = 1 ,391158  ,1194,1194,1194
BEGIN DESCRIPTION:
San Miguel Creek 210.0
END DESCRIPTION:
XS GIS Cut Line= 4
       1988685.3      13564182.1       1986120.8     13563924.54
      1985669.53      13564145.1      1984324.49     13565498.81
#Sta/Elev= 30
  2422.6  599.62  2641.3   599.6  3192.9  587.34  3995.2  577.84    4093  573.35
  4268.5  574.88    4367  574.89  4460.9  575.26  4630.7  575.56  4790.3   576.6
  4892.8  573.98    4933  568.03  4968.1  573.12  4983.2  570.71  4985.8  560.65
  4993.3  559.65  5021.8  560.65  5023.5  566.64  5031.5  571.91  5064.1   570.9
  5158.6  575.98  5286.5  576.32  5479.4  577.16  5887.3     598  6265.6  604.05
  6594.4  602.39  6940.9  617.42  7213.1  610.33  7301.5  613.12  7410.6  622.85
#Mann= 10 ,-1 , 0
  2422.6     .05       0  4268.5      .1       0    4367     .05       0
  4460.9      .1       0  4630.7     .16       0  4790.3     .12       0
  4985.8     .07       0  5021.8     .12       0  5064.1     .16       0
  5286.5      .1       0
Bank Sta=4985.8,5021.8
XS Rating Curve= 0 ,0
Exp/Cntr=0.3,0.1

Type RM Length L Ch R = 1 ,389964  ,676,676,676
BEGIN DESCRIPTION:
San Miguel Creek 209.0
END DESCRIPTION:
XS GIS Cut Line= 3
      1988904.11     13563124.81       1985530.8     13563024.54
      1983831.16     13563682.09
#Sta/Elev= 30
  1625.2  596.37  2124.1  589.72  2547.2  593.04  3452.1  579.44  3687.7  579.51
  3772.8  574.55  3848.9  577.51  3947.2  574.27  4092.9  572.42  4107.9  569.25
  4122.9  572.44  4157.9  570.42    4338   573.6  4660.3  573.47  4758.2  570.79
  4973.3  570.84  4993.3  568.23  4997.9  565.19    4998  558.82  5005.5  557.82
  5034.1  558.82  5035.7  566.61  5046.4  573.39  5137.8  573.54  5244.8  573.04
  5400.3  578.16  5900.3  605.56  6125.2  614.76  6400.5  612.41  6822.4  619.45
#Mann= 9 ,-1 , 0
  1625.2     .05       0  3452.1      .1       0  3848.9     .05       0
  3947.2     .16       0  4660.3     .12       0    4998     .07       0
  5034.1     .12       0  5137.8      .1       0  5900.3     .05       0
Bank Sta=4998,5034.1
XS Rating Curve= 0 ,0
Exp/Cntr=0.3,0.1

Type RM Length L Ch R = 1 ,389288  ,999,999,999
BEGIN DESCRIPTION:
San Miguel Creek 208.0
END DESCRIPTION:
XS GIS Cut Line= 4
      1988013.39     13562390.43        1985675.       13562425.
      1984816.82     13562551.46      1983789.72     13563431.89
#Sta/Elev= 30
    2647  595.46  3958.8   585.8  4057.2  585.17  4155.6   582.9  4259.8  580.01
  4478.1  570.55  4513.1  565.71  4543.1  569.38  4570.1  569.31  4888.1   572.6
  4938.1  568.78  4958.1  568.88  4968.1  564.31  4970.1  559.38  4977.7  558.38
  5006.2  559.38    5018  568.77  5020.5  566.92  5023.6  570.53  5033.7  572.42
    5166  573.34    5535  572.66  5695.7  570.57  5837.2  573.25    6059  588.23
  6292.2  592.85  6690.1   595.6  6821.2  602.36  6878.3  606.99  7205.9  616.87
#Mann= 11 ,-1 , 0
    2647     .05       0  3958.8      .1       0  4057.2     .08       0
  4155.6      .1       0  4259.8     .16       0  4570.1     .12       0
  4970.1     .07       0  5006.2     .12       0    5166     .16       0
    5535      .1       0  6292.2     .05       0
Bank Sta=4970.1,5006.2
XS Rating Curve= 0 ,0
Exp/Cntr=0.3,0.1

Type RM Length L Ch R = 1 ,388289  ,752,752,752
BEGIN DESCRIPTION:
San Miguel Creek 207.0
END DESCRIPTION:
XS GIS Cut Line= 4
      1987924.98       13561575.        1985925.       13561575.
      1984816.82     13561843.12      1982699.36     13562703.99
#Sta/Elev= 30
  3016.5   600.3    3499  593.19    3854  584.63  4138.9  580.25  4410.2  577.46
    4464  576.68  4508.6  573.17  4703.6  571.87    4754  570.42    4769  572.11
    4829  568.86  4913.9  570.13    4964   569.5    4969  568.69    4979  561.24
  4987.5  559.56  4990.9   559.5  4998.4   558.4    5027   559.5  5037.4   568.2
  5049.9  571.32  5101.7  571.08  5203.7  570.74  5481.8  573.81  6281.9  569.77
  6359.5  572.63    7184  584.24    7726  594.67  8142.3  599.33  8442.4  608.74
#Mann= 11 ,-1 , 0
  3016.5     .05       0  4138.9      .1       0  4410.2     .05       0
  4508.6      .1       0  4703.6     .12       0  4913.9     .16       0
  4987.5     .12       0  4990.9     .07       0    5027     .12       0
  5101.7     .16       0  5203.7     .05       0
Bank Sta=4990.9,5027
XS Rating Curve= 0 ,0
Exp/Cntr=0.3,0.1

Type RM Length L Ch R = 1 ,387537  ,787,787,787
BEGIN DESCRIPTION:
San Miguel Creek 206.0
END DESCRIPTION:
XS GIS Cut Line= 4
      1987511.27     13560905.62       1986180.8     13560913.65
      1985080.71     13561030.62      1982615.43     13562242.65
#Sta/Elev= 30
  3669.5   595.1  4538.3  586.13  4628.7  583.39  4727.1  581.01  4825.4  577.25
  4968.3  570.39  4973.3  569.55  4975.2  554.96  4982.7  553.86  5011.3  554.96
  5011.8  557.18  5028.5  568.46  5068.7  564.61  5088.8  567.99  5121.6  569.35
  5220.9  569.01  5330.1  566.84    5721  572.77  6260.3   573.7    6755  569.68
  6928.9  569.58  7118.5     577  7364.5   583.1  7881.5  584.27  8392.8  589.51
  8687.7  593.69  8766.4  596.32  8795.4  599.59  8822.6  595.72  8853.4  596.32
#Mann= 10 ,-1 , 0
  3669.5     .05       0  4628.7      .1       0  4727.1     .05       0
  4825.4     .12       0  4975.2     .07       0  5011.3     .12       0
  5121.6      .1       0  5220.9     .05       0    6755      .1       0
  7118.5     .05       0
Bank Sta=4975.2,5011.3
XS Rating Curve= 0 ,0
Exp/Cntr=0.3,0.1

Type RM Length L Ch R = 1 ,386750  ,1349,1349,1349
BEGIN DESCRIPTION:
Mapping XS 8bca09ed
END DESCRIPTION:
XS GIS Cut Line= 4
      1987820.32     13560108.75      1986101.55     13560160.83
       1985094.6     13560317.08      1982364.38      13561747.5
#Sta/Elev= 30
  3299.7  595.16  4165.9  584.08  4333.5   585.4  4642.9     579  4741.4  575.82
  4839.9  572.89  4973.3  566.06  4988.3  559.87  4990.3  551.57  4997.8  550.47
  5026.4  551.57  5028.4  563.21  5033.5  566.61  5087.5  566.78  5241.2  566.39
  5502.2  570.19  6015.1  572.33  6303.1  572.31    6637  568.02  6887.5  568.82
  6928.8  574.21  6939.9  573.56  6959.1  566.23  6970.1   564.6  7036.3  564.36
  7073.6  573.39  7167.1  573.62    7651  577.94  8469.7  591.21  9120.5  594.04
#Mann= 10 ,-1 , 0
  3299.7     .05       0  4642.9      .1       0  4741.4     .16       0
  4839.9     .12       0  4990.3     .07       0  5026.4     .12       0
  5087.5     .16       0  5241.2     .05       0    6637      .1       0
  7167.1     .05       0
Bank Sta=4990.3,5026.4
XS Rating Curve= 0 ,0
Exp/Cntr=0.3,0.1