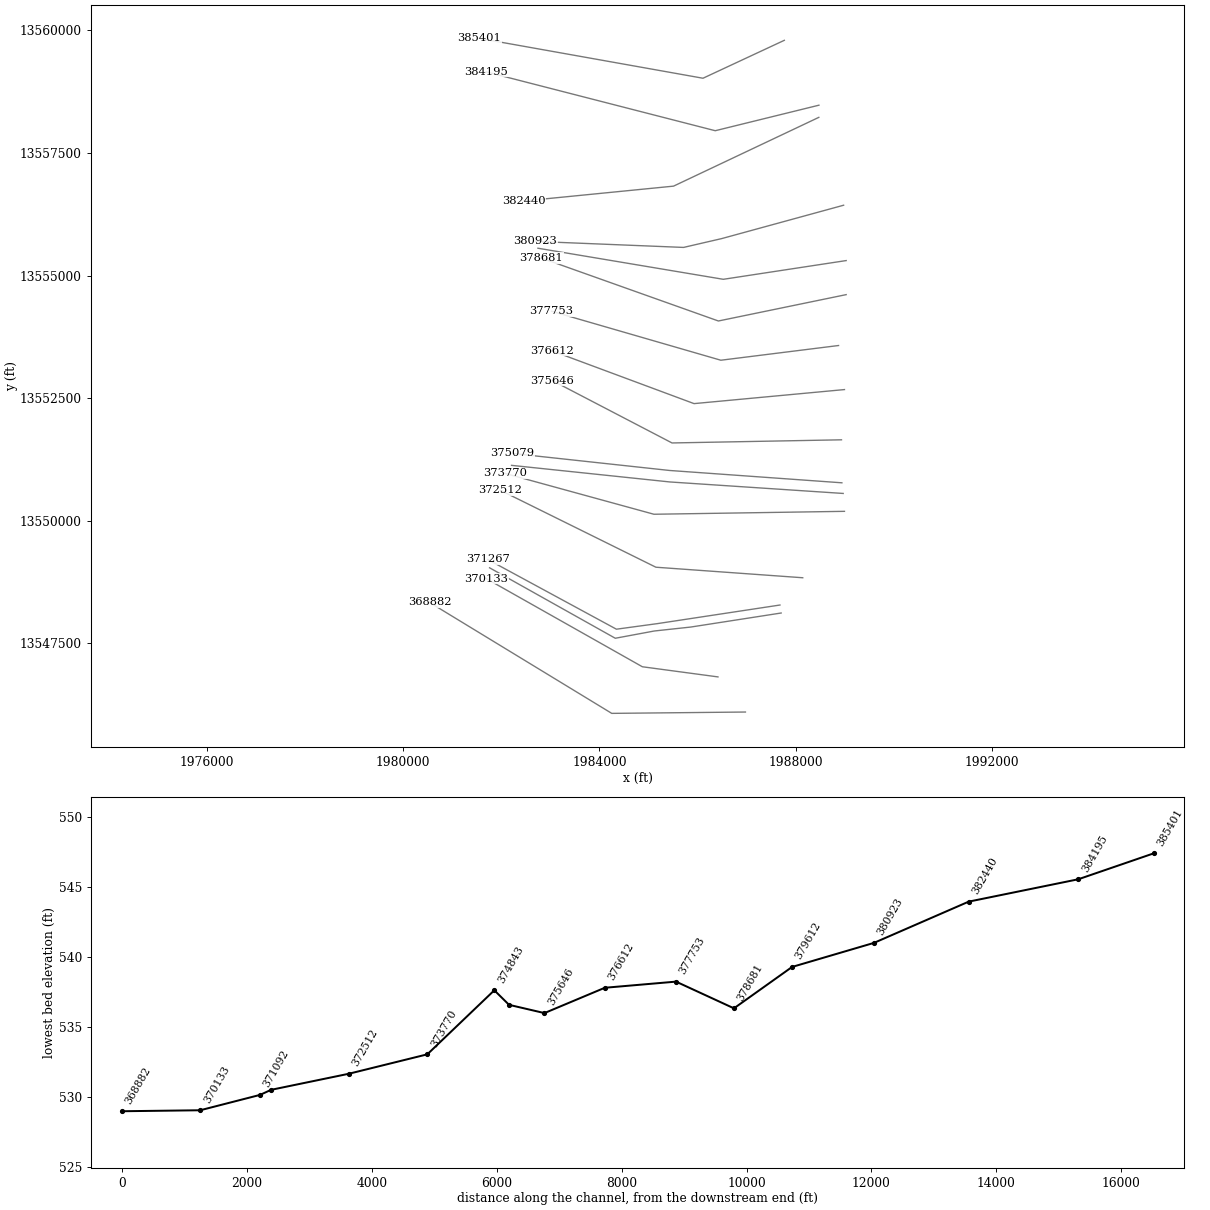
HEC-RAS study San Miguel Creek.prj: San Miguel Creek Base Level Engineering

--- San Miguel Creek.g01 (geometry) --- (continued)

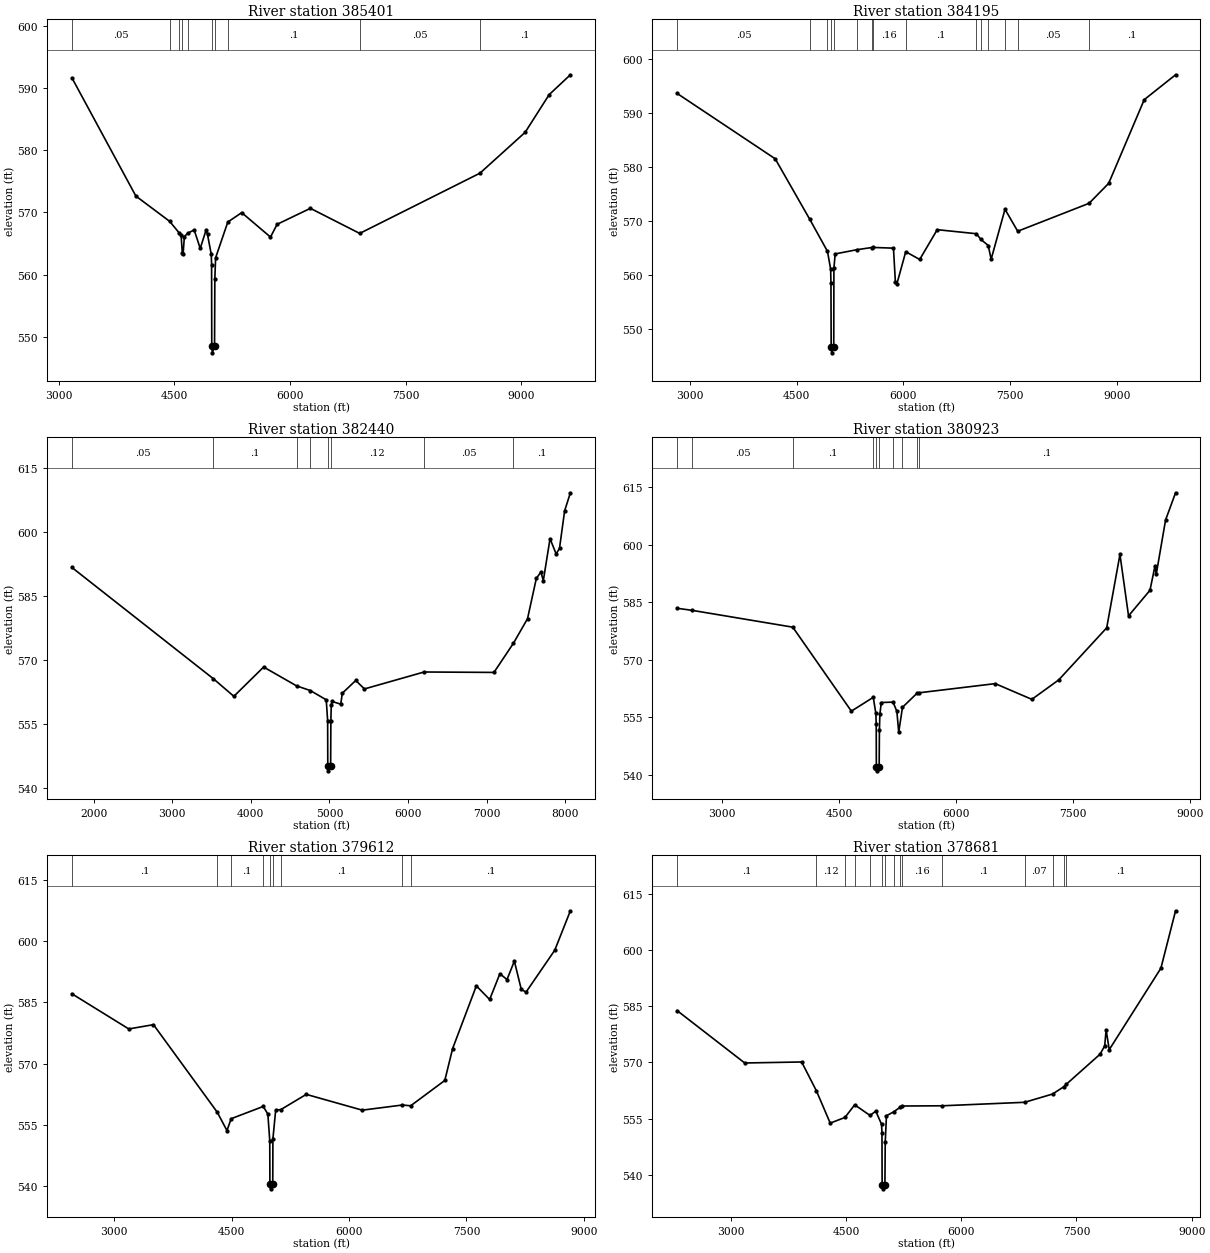
Type RM Length L Ch R = 1 ,385401  ,1206,1206,1206
BEGIN DESCRIPTION:
San Miguel Creek 205.0
END DESCRIPTION:
XS GIS Cut Line= 3
      1987769.53     13559797.99       1986110.8     13559024.54
      1981547.76     13559838.12
#Sta/Elev= 30
  3169.8  591.61  3999.6  572.61  4437.5  568.55  4562.6  566.67    4586  566.38
  4601.6  563.43  4611.9  563.28  4628.5  566.09  4669.6  566.62  4755.4  567.17
  4834.3   564.2  4909.9  567.15  4928.5  566.44    4977  563.26  4981.6  561.61
  4983.7  548.52  4991.2  547.42  5019.8  548.52  5023.7  559.35  5033.8   562.7
    5192  568.44  5372.3  569.95  5745.3  566.02  5831.2  568.07  6262.9  570.64
  6902.5  566.61  8462.3  576.29  9048.1  582.85  9359.7  588.91    9635   592.1
#Mann= 10 ,-1 , 0
  3169.8     .05       0  4437.5      .1       0  4562.6     .12       0
  4601.6     .16       0  4669.6     .12       0  4983.7     .07       0
  5019.8     .12       0    5192      .1       0  6902.5     .05       0
  8462.3      .1       0
Bank Sta=4983.7,5019.8
XS Rating Curve= 0 ,0
Exp/Cntr=0.3,0.1

Type RM Length L Ch R = 1 ,384195  ,1755,1755,1755
BEGIN DESCRIPTION:
San Miguel Creek 204.0
END DESCRIPTION:
XS GIS Cut Line= 3
      1988474.98     13558474.99       1986360.8     13557954.54
      1981691.78      13559153.9
#Sta/Elev= 30
  2822.7  593.62  4200.1  581.51  4686.2  570.28  4933.9  564.37  4978.7  561.05
  4982.8  558.58  4985.9  546.67  4993.4  545.57    5022  546.67  5024.3  561.21
  5042.1  563.89  5346.3  564.67  5553.1  565.07  5571.4  565.09  5860.4  564.96
  5887.4  558.64  5907.8  558.32  6032.7   564.3  6228.6  562.86  6474.7  568.38
    7026  567.63  7084.8  566.61  7190.5  565.45  7231.8  562.91  7426.1  572.16
  7604.4  568.09  8605.9  573.26  8881.7  576.96  9380.7  592.46  9820.6  597.07
#Mann= 15 ,-1 , 0
  2822.7     .05       0  4686.2      .1       0  4933.9     .12       0
  4985.9     .07       0    5022     .12       0  5346.3     .16       0
  5553.1     .12       0  5571.4     .16       0  6032.7      .1       0
    7026     .16       0  7084.8      .1       0  7190.5     .16       0
  7426.1      .1       0  7604.4     .05       0  8605.9      .1       0
Bank Sta=4985.9,5022
XS Rating Curve= 0 ,0
Exp/Cntr=0.3,0.1

Type RM Length L Ch R = 1 ,382440  ,1517,1517,1517
BEGIN DESCRIPTION:
San Miguel Creek 203.0
END DESCRIPTION:
XS GIS Cut Line= 3
      1988472.62     13558226.79       1985510.8     13556824.54
      1982459.64      13556522.2
#Sta/Elev= 30
    1723  591.62  3524.5  565.53  3783.8  561.43  4162.8  568.29  4582.7  563.87
  4757.2  562.78  4959.4  560.61  4977.2  555.72    4979  545.07  4986.6  543.97
  5015.2  545.07  5018.4  555.69  5023.4  559.44  5033.5  560.23    5144  559.59
  5164.1  562.16  5334.9  565.14  5445.5  563.16  6204.6  567.13  7093.5  567.03
  7340.5  573.84  7520.6  579.61  7632.9  589.06  7691.4  590.56  7721.6  588.52
    7807  598.36  7885.2  594.78  7927.6   596.1  7992.9   604.9  8066.1  609.12
#Mann= 8 ,-1 , 0
    1723     .05       0  3524.5      .1       0  4582.7     .16       0
  4757.2     .12       0    4979     .07       0  5015.2     .12       0
  6204.6     .05       0  7340.5      .1       0
Bank Sta=4979,5015.2
XS Rating Curve= 0 ,0
Exp/Cntr=0.3,0.1

Type RM Length L Ch R = 1 ,380923  ,1311,1311,1311
BEGIN DESCRIPTION:
San Miguel Creek 201.0
END DESCRIPTION:
XS GIS Cut Line= 4
      1988978.31     13556435.36       1986490.8     13555754.54
      1985714.39       13555575.      1982694.27     13555697.48
#Sta/Elev= 30
    2421  583.43  2616.8  582.88    3906   578.5    4658  556.59  4939.3   560.2
  4972.3  555.99  4977.1  553.29  4978.8  542.12  4986.4  541.02    5015  542.12
  5018.2  551.67  5023.9  555.77  5042.1  558.84  5193.1  558.95    5242  556.55
    5266  551.12  5314.4   557.6  5505.4  561.35  5522.4  561.37  6504.4  563.77
  6974.8  559.67    7320  564.75  7935.5  578.33  8105.7  597.46  8215.8  581.45
    8491  588.12  8556.1  594.54  8571.1  592.26  8691.2  606.46  8819.5  613.56
#Mann= 10 ,-1 , 0
    2421      .1       0  2616.8     .05       0    3906      .1       0
  4939.3     .12       0  4978.8     .07       0    5015     .12       0
  5193.1     .16       0  5314.4      .1       0  5505.4     .16       0
  5522.4      .1       0
Bank Sta=4978.8,5015
XS Rating Curve= 0 ,0
Exp/Cntr=0.3,0.1

Type RM Length L Ch R = 1 ,379612  ,931,931,931
BEGIN DESCRIPTION:
San Miguel Creek 200.0
END DESCRIPTION:
XS GIS Cut Line= 3
       1989030.4     13555306.89        1986525.       13554925.
      1982745.68     13555558.61
#Sta/Elev= 30
  2461.4  587.12  3187.6   578.5  3503.1  579.55  4317.3   558.1  4441.9  553.58
    4496   556.5  4905.4   559.5    4964  557.63  4988.2  551.14  4990.3   540.4
  4997.9   539.3  5026.5   540.4  5028.7   551.6  5064.2  558.63  5128.5  558.71
  5454.6  562.46  6169.4  558.59  6682.1  559.85  6787.9  559.66  7223.9  565.87
  7323.5  573.67  7626.8  589.06  7796.8  585.72  7927.5  592.04  8018.5   590.6
  8112.1  595.14  8200.5  588.21  8261.2  587.52  8628.2   597.8  8827.8  607.47
#Mann= 9 ,-1 , 0
  2461.4      .1       0  4317.3     .12       0    4496      .1       0
  4905.4     .12       0  4990.3     .07       0  5026.5     .12       0
  5128.5      .1       0  6682.1     .12       0  6787.9      .1       0
Bank Sta=4990.3,5026.5
XS Rating Curve= 0 ,0
Exp/Cntr=0.3,0.1

Type RM Length L Ch R = 1 ,378681  ,928,928,928
BEGIN DESCRIPTION:
San Miguel Creek 199.0
END DESCRIPTION:
XS GIS Cut Line= 3
      1989030.32     13554612.43        1986425.       13554075.
      1982815.11     13555358.96
#Sta/Elev= 30
  2299.2  583.82  3180.2  569.86  3921.5  570.13  4113.7  562.44  4293.4  553.84
  4484.6  555.35  4612.6  558.72  4812.2  555.88  4886.5  557.04    4962  553.54
  4967.3  551.22  4969.5  537.44    4977  536.34  5005.7  537.44  5009.8  548.73
  5025.7  555.81  5120.4  556.85  5204.6  558.09  5225.9   558.4  5752.3  558.46
  6825.7  559.39  7189.1  561.59  7337.3  563.56  7366.1  564.16  7809.2  572.23
  7868.2  574.46  7886.3  578.68  7927.2  573.41  8599.9  595.11  8790.8   610.4
#Mann= 15 ,-1 , 0
  2299.2      .1       0  4113.7     .12       0  4484.6      .1       0
  4612.6     .16       0  4812.2     .12       0  4969.5     .07       0
  5005.7     .12       0  5120.4     .16       0  5204.6      .1       0
  5225.9     .16       0  5752.3      .1       0  6825.7     .07       0
  7189.1     .12       0  7337.3     .07       0  7366.1      .1       0
Bank Sta=4969.5,5005.7
XS Rating Curve= 0 ,0
Exp/Cntr=0.3,0.1

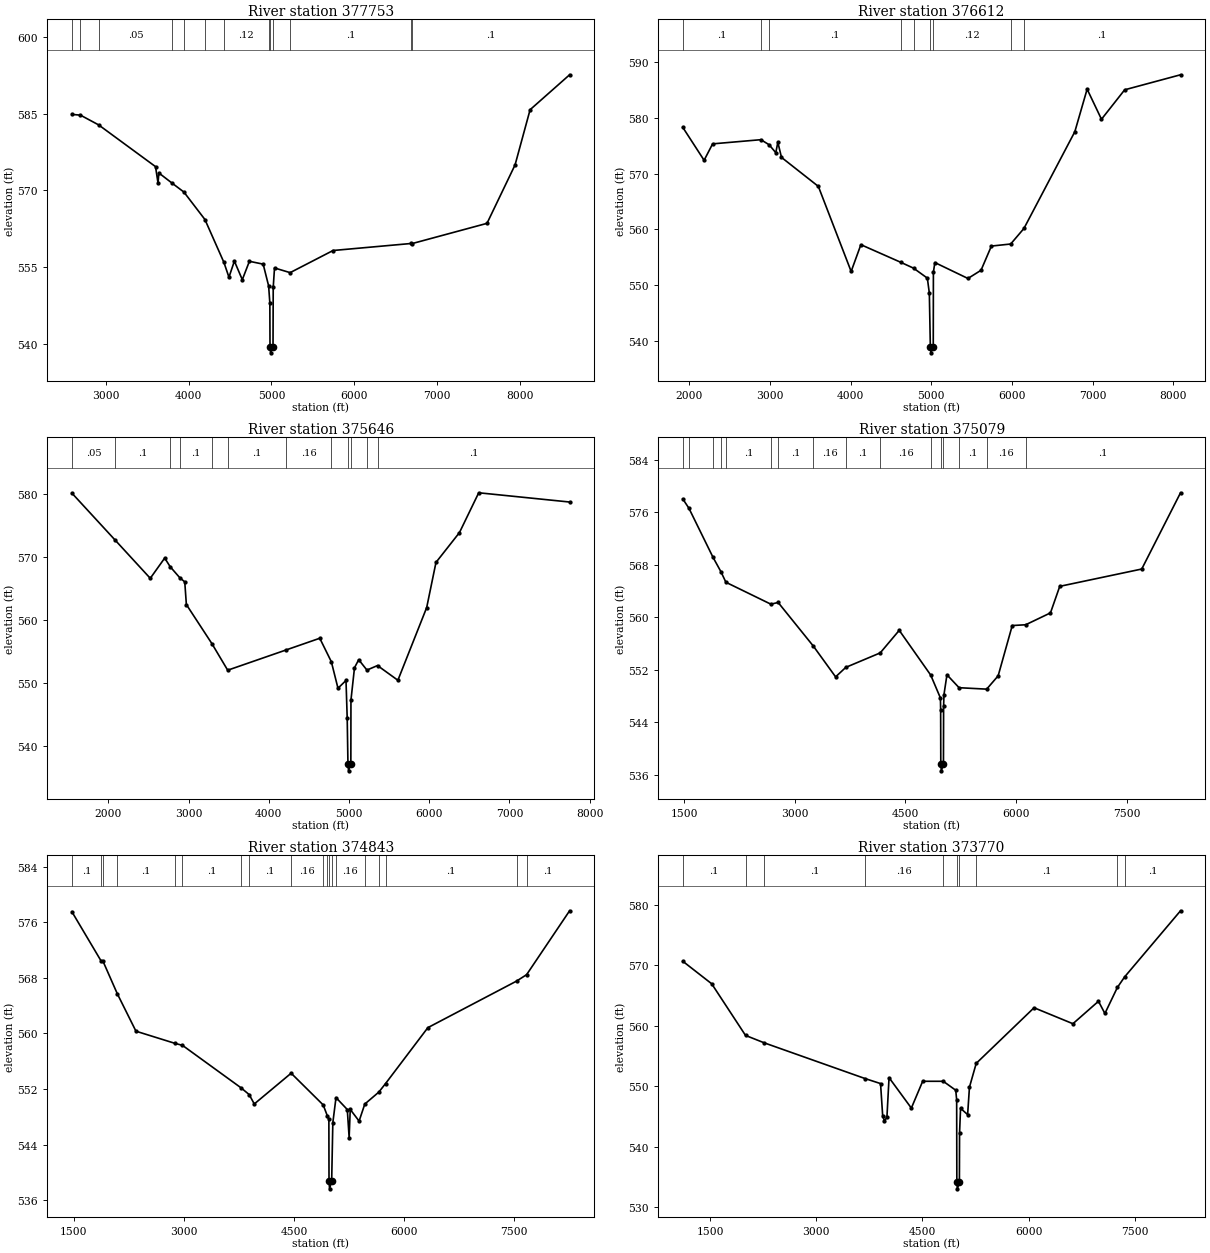
Type RM Length L Ch R = 1 ,377753  ,1141,1141,1141
BEGIN DESCRIPTION:
San Miguel Creek 198.0
END DESCRIPTION:
XS GIS Cut Line= 3
      1988874.97       13553575.        1986475.       13553275.
      1983024.25     13554273.65
#Sta/Elev= 30
  2589.4  584.87  2692.6  584.73  2912.8  582.82  3599.7  574.66  3629.9  571.45
    3640  573.42  3803.1  571.39  3942.4  569.69  4196.3  564.32  4425.8  555.93
  4486.5  553.03    4552  556.19  4647.8  552.55  4733.4  556.15  4899.7  555.59
  4965.6  551.34  4980.3     548  4982.4  539.35  4989.9  538.25  5018.6  539.35
  5021.1  551.05  5036.7  554.85  5225.2  553.93  5743.7  558.26  6685.3  559.63
    6693  559.59  7602.8  563.57  7941.8     575  8123.3  585.79  8600.4  592.62
#Mann= 13 ,-1 , 0
  2589.4     .05       0  2692.6      .1       0  2912.8     .05       0
  3803.1      .1       0  3942.4     .05       0  4196.3     .16       0
  4425.8     .12       0  4965.6     .16       0  4982.4     .07       0
  5018.6     .12       0  5225.2      .1       0  6685.3     .05       0
    6693      .1       0
Bank Sta=4982.4,5018.6
XS Rating Curve= 0 ,0
Exp/Cntr=0.3,0.1

Type RM Length L Ch R = 1 ,376612  ,966,966,966
BEGIN DESCRIPTION:
San Miguel Creek 197.0
END DESCRIPTION:
XS GIS Cut Line= 3
       1988995.6     13552676.67      1985928.84     13552390.32
      1983032.13     13553466.59
#Sta/Elev= 30
  1919.9  578.31  2184.1   572.4  2289.6  575.35  2888.2   576.1    2990  575.19
    3073  573.76  3098.1  575.64  3143.3  572.92  3600.3  567.71    4007  552.43
  4127.6  557.24  4619.6  554.09  4780.6  553.02  4951.6  551.23  4976.2  548.54
  4988.7  538.91  4996.2  537.81  5024.9  538.91  5026.6  552.28  5044.5  554.03
  5454.8  551.17  5616.9  552.64  5745.6  556.99  5984.7  557.36  6148.8  560.15
  6779.8  577.53  6932.3  585.18  7110.2  579.77  7397.8  585.06  8090.2  587.76
#Mann= 9 ,-1 , 0
  1919.9      .1       0  2888.2     .05       0    2990      .1       0
  4619.6     .16       0  4780.6     .12       0  4988.7     .07       0
  5024.9     .12       0  5984.7     .05       0  6148.8      .1       0
Bank Sta=4988.7,5024.9
XS Rating Curve= 0 ,0
Exp/Cntr=0.3,0.1

Type RM Length L Ch R = 1 ,375646  ,567,567,567
BEGIN DESCRIPTION:
San Miguel Creek 196.0
END DESCRIPTION:
XS GIS Cut Line= 3
      1988934.83     13551652.37      1985479.63     13551588.24
      1983040.82     13552858.95
#Sta/Elev= 30
  1544.2  580.16    2087  572.64  2521.7  566.61  2701.7  569.83  2770.1  568.45
  2888.8  566.72  2951.8  566.04  2971.8  562.44  3289.9  556.23  3487.1     552
  4208.6  555.19    4635  557.08  4779.5  553.34  4862.1  549.13  4962.1  550.37
  4977.1   544.4  4986.4   537.1    4994     536  5022.6   537.1  5023.8  547.24
    5068  552.39  5120.4  553.67  5223.2  552.02  5354.9  552.74  5609.1   550.4
  5968.1  561.96    6084  569.14  6376.6  573.88  6616.9  580.21    7750  578.74
#Mann= 12 ,-1 , 0
  1544.2     .05       0    2087      .1       0  2770.1     .05       0
  2888.8      .1       0  3289.9     .16       0  3487.1      .1       0
  4208.6     .16       0  4779.5     .12       0  4986.4     .07       0
  5022.6     .12       0  5223.2     .16       0  5354.9      .1       0
Bank Sta=4986.4,5022.6
XS Rating Curve= 0 ,0
Exp/Cntr=0.3,0.1

Type RM Length L Ch R = 1 ,375079  ,236,236,236
BEGIN DESCRIPTION:
Mapping XS d471e6fc
END DESCRIPTION:
XS GIS Cut Line= 3
      1988943.53     13550775.63      1985427.94     13551027.37
       1982224.9     13551374.58
#Sta/Elev= 30
  1484.2  578.06  1567.3  576.64  1893.2  569.17  1999.7  566.99  2068.6  565.35
  2677.9  562.01  2776.7  562.27  3254.8   555.6  3555.5  550.92  3693.4  552.37
  4160.3  554.58  4417.9  558.02  4844.3   551.2  4976.2   547.7  4979.2  545.89
  4981.1  537.69  4988.7  536.59  5017.3  537.69  5019.3  546.41  5024.3  548.22
  5064.6  551.24  5228.9  549.27  5602.9  549.05  5758.6  551.08  5949.7  558.75
  6131.8  558.87  6467.7  560.68  6593.5  564.73  7704.9  567.37  8230.6     579
#Mann= 16 ,-1 , 0
  1484.2      .1       0  1567.3     .05       0  1893.2      .1       0
  1999.7     .05       0  2068.6      .1       0  2677.9     .08       0
  2776.7      .1       0  3254.8     .16       0  3693.4      .1       0
  4160.3     .16       0  4844.3     .12       0  4981.1     .07       0
  5017.3     .12       0  5228.9      .1       0  5602.9     .16       0
  6131.8      .1       0
Bank Sta=4981.1,5017.3
XS Rating Curve= 0 ,0
Exp/Cntr=0.3,0.1

Type RM Length L Ch R = 1 ,374843  ,1073,1073,1073
BEGIN DESCRIPTION:
Mapping XS 5c4f15a8
END DESCRIPTION:
XS GIS Cut Line= 3
      1988969.58     13550558.62      1985436.62     13550792.99
      1982207.45     13551131.53
#Sta/Elev= 30
  1472.3  577.54  1871.7  570.43  1894.5  570.46  2092.1  565.72  2346.3  560.33
  2881.1  558.57    2981  558.29  3778.8  552.18  3890.5   551.2  3959.8  549.85
  4462.6  554.28  4899.8  549.71  4956.5  548.13  4977.1  547.62    4979  538.73
  4986.6  537.63  5015.2  538.73    5031  547.15  5074.3  550.77  5228.3  549.05
  5253.5  545.01  5268.5  549.06  5389.2  547.39  5467.2  549.84  5658.2  551.56
    5750  552.79  6326.9  560.84  7535.9  567.54  7673.5  568.47  8259.9  577.67
#Mann= 19 ,-1 , 0
  1472.3      .1       0  1871.7     .08       0  1894.5     .05       0
  2092.1      .1       0  2881.1     .05       0    2981      .1       0
  3778.8     .12       0  3890.5      .1       0  4462.6     .16       0
  4899.8     .05       0  4956.5     .12       0    4979     .07       0
  5015.2     .12       0  5074.3     .16       0  5467.2      .1       0
  5658.2     .05       0    5750      .1       0  7535.9     .05       0
  7673.5      .1       0
Bank Sta=4979,5015.2
XS Rating Curve= 0 ,0
Exp/Cntr=0.3,0.1

Type RM Length L Ch R = 1 ,373770  ,1258,1258,1258
BEGIN DESCRIPTION:
San Miguel Creek 194.0
END DESCRIPTION:
XS GIS Cut Line= 3
      1988995.64     13550194.03       1985110.8     13550134.54
      1982077.24      13550966.6
#Sta/Elev= 30
  1114.7  570.65  1522.9  566.93  2000.8   558.4  2267.5  557.16  3694.6  551.25
  3908.2  550.44  3938.2  545.12  3963.2  544.27  3998.2  544.87  4028.2  551.42
  4343.2  546.39  4503.2  550.82    4794  550.82  4970.3  549.34  4983.3  547.75
  4985.8  534.15  4993.3  533.05    5022  534.15  5024.2  542.24  5038.3  546.36
  5138.2  545.31  5164.1  549.85  5259.5  553.78  6076.6  562.97  6625.5  560.33
  6986.5  564.04  7077.3  562.02  7253.4  566.32  7356.2  568.07  8145.6  578.99
#Mann= 10 ,-1 , 0
  1114.7      .1       0  2000.8     .12       0  2267.5      .1       0
  3694.6     .16       0    4794     .12       0  4985.8     .07       0
    5022     .12       0  5259.5      .1       0  7253.4     .05       0
  7356.2      .1       0
Bank Sta=4985.8,5022
XS Rating Curve= 0 ,0
Exp/Cntr=0.3,0.1

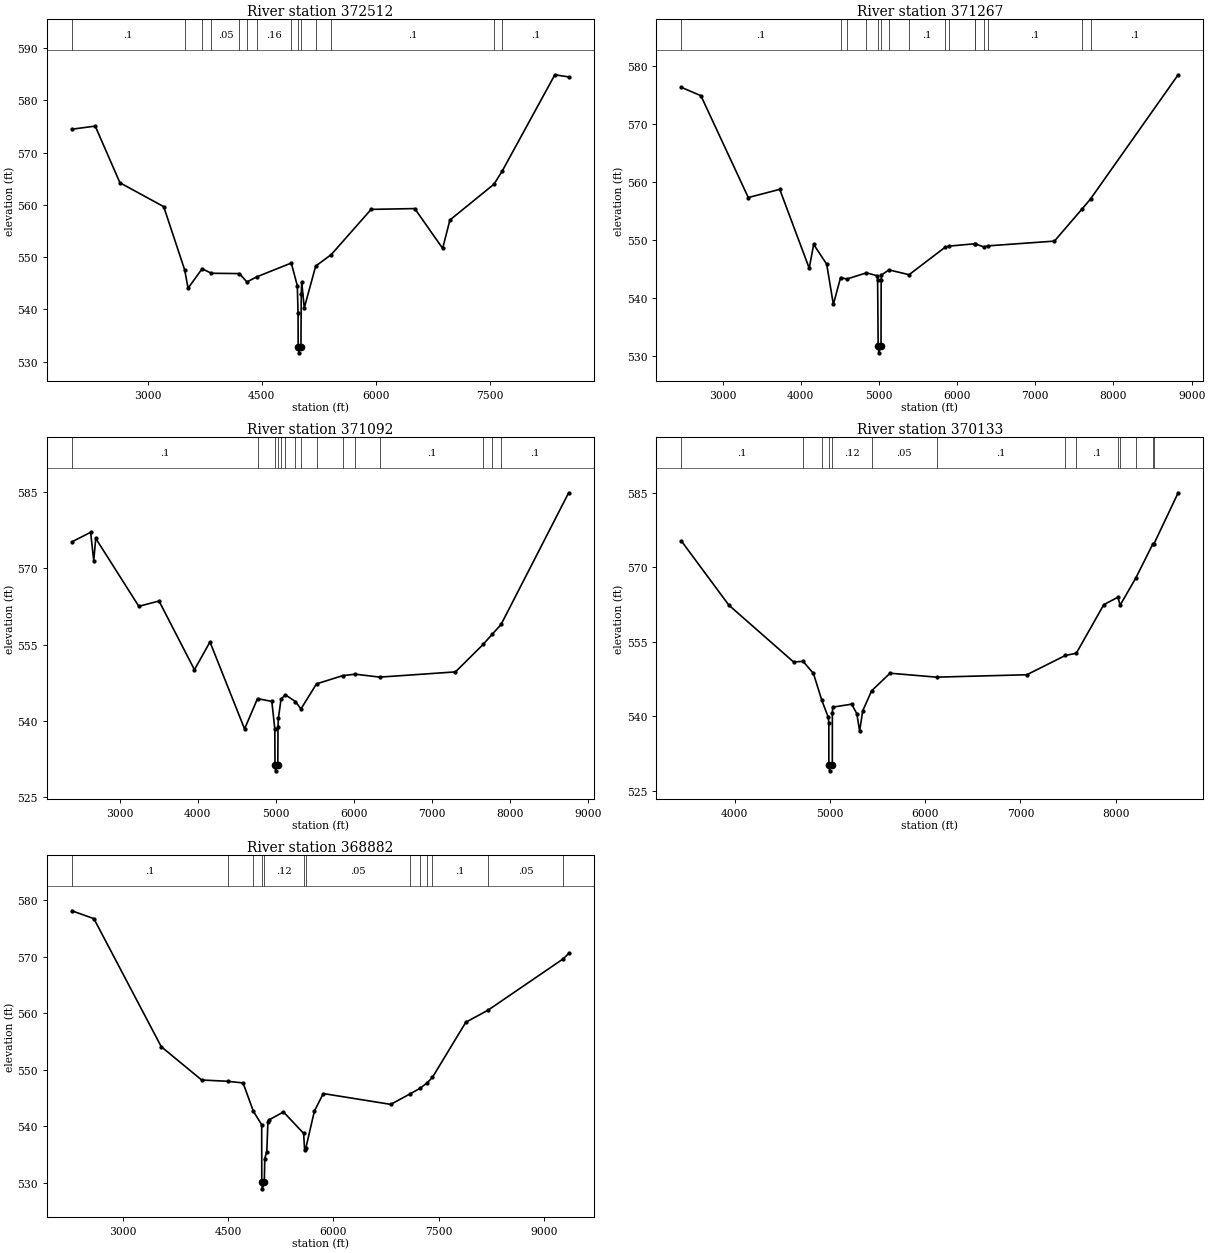
Type RM Length L Ch R = 1 ,372512  ,1245,1245,1245
BEGIN DESCRIPTION:
San Miguel Creek 193.0
END DESCRIPTION:
XS GIS Cut Line= 3
      1988144.91     13548839.87       1985150.8     13549054.54
      1981974.99     13550625.01
#Sta/Elev= 30
  1998.2  574.49  2306.4  575.09  2632.2  564.23  3208.7  559.66  3484.8  547.54
  3529.5  544.04  3714.3  547.76  3836.5   546.9  4206.1  546.84  4304.9  545.23
  4431.2   546.2  4888.7  548.86  4968.2  544.54  4978.2  539.29  4979.8  532.76
  4987.3  531.66    5016  532.76  5020.4  542.91  5026.2  545.21  5059.8  540.26
  5210.2  548.27  5414.6  550.47  5940.8  559.14  6515.3  559.29  6882.7  551.67
  6978.3   557.1  7559.7  563.97  7671.1  566.58  8360.6  584.92  8542.9  584.51
#Mann= 14 ,-1 , 0
  1998.2      .1       0  3484.8     .12       0  3714.3      .1       0
  3836.5     .05       0  4206.1     .12       0  4304.9      .1       0
  4431.2     .16       0  4888.7     .12       0  4979.8     .07       0
    5016     .12       0  5210.2     .16       0  5414.6      .1       0
  7559.7     .08       0  7671.1      .1       0
Bank Sta=4979.8,5016
XS Rating Curve= 0 ,0
Exp/Cntr=0.3,0.1

Type RM Length L Ch R = 1 ,371267  ,175,175,175
BEGIN DESCRIPTION:
San Miguel Creek 191.0
END DESCRIPTION:
XS GIS Cut Line= 4
      1987680.49     13548283.81       1985180.8     13547904.54
      1984345.86     13547790.92      1981721.36     13549213.12
#Sta/Elev= 30
  2471.7  576.28  2722.5  574.83  3328.6  557.28  3730.9  558.69  4108.2  545.09
    4165   549.2  4331.8  545.78  4416.7  538.87  4509.9  543.49  4589.3  543.23
  4840.2   544.3  4978.1   543.8  4983.1     543  4990.3  531.61  4997.8  530.51
  5026.5  531.61  5028.6  543.05  5032.4  543.93  5127.2  544.81  5385.9  543.98
  5849.4  548.74  5898.9  548.91  6227.1  549.31  6232.5   549.3  6340.9  548.76
  6393.1  548.95  7244.8  549.77  7601.1  555.35  7706.5  557.03  8827.7  578.44
#Mann= 16 ,-1 , 0
  2471.7      .1       0  4509.9     .12       0  4589.3      .1       0
  4840.2     .12       0  4990.3     .07       0  5026.5     .12       0
  5127.2     .16       0  5385.9      .1       0  5849.4     .16       0
  5898.9      .1       0  6227.1     .16       0  6232.5      .1       0
  6340.9     .16       0  6393.1      .1       0  7601.1     .05       0
  7706.5      .1       0
Bank Sta=4990.3,5026.5
XS Rating Curve= 0 ,0
Exp/Cntr=0.3,0.1

Type RM Length L Ch R = 1 ,371092  ,959,959,959
BEGIN DESCRIPTION:
Mapping XS 94d7856f
END DESCRIPTION:
XS GIS Cut Line= 5
      1987704.97     13548121.04      1985861.64     13547834.78
       1985120.8     13547754.54      1984322.83     13547606.18
      1981759.39     13549043.02
#Sta/Elev= 30
  2389.4  575.22  2629.7  577.11  2670.2  571.51  2695.5  575.92    3247  562.54
  3505.8  563.58  3959.1  550.06    4158  555.52    4601   538.4  4766.5  544.36
  4949.9  543.82  4988.2  538.38  4990.3  531.25  4997.9  530.15  5026.5  531.25
  5028.8  538.77  5033.9  540.49  5068.2  544.31    5124   545.1  5252.4  543.79
  5322.9  542.34  5521.8  547.27  5857.5  548.89  6016.6  549.18  6330.9   548.6
  7300.8  549.63  7657.8  555.08  7772.5  557.06  7884.6  558.96  8750.3  584.89
#Mann= 15 ,-1 , 0
  2389.4      .1       0  4766.5     .12       0  4990.3     .07       0
  5026.5     .12       0  5068.2     .16       0    5124      .1       0
  5252.4     .16       0  5322.9      .1       0  5521.8     .05       0
  5857.5      .1       0  6016.6     .16       0  6330.9      .1       0
  7657.8     .08       0  7772.5     .05       0  7884.6      .1       0
Bank Sta=4990.3,5026.5
XS Rating Curve= 0 ,0
Exp/Cntr=0.3,0.1

Type RM Length L Ch R = 1 ,370133  ,1251,1251,1251
BEGIN DESCRIPTION:
San Miguel Creek 190.0
END DESCRIPTION:
XS GIS Cut Line= 3
      1986416.64     13546818.12        1984875.       13547025.
      1981690.09     13548823.33
#Sta/Elev= 30
  3441.8  575.34  3940.4  562.41  4620.1  550.96  4719.6  551.09  4828.3  548.65
  4916.8  543.21  4984.6   539.8  4989.7  538.59  4989.9  530.25  4997.5  529.05
  5026.2  530.25  5026.9  540.62  5029.7  541.87    5229  542.47  5283.2  540.57
  5312.8  537.05  5345.3  541.13  5438.9  545.16  5631.7   548.7  6119.6  547.91
  7067.2  548.39  7471.1  552.27  7586.1  552.72  7874.6   562.5  8022.6  563.99
    8046  562.39  8212.5  567.94    8391  574.78  8402.4   574.8  8654.8  585.02
#Mann= 14 ,-1 , 0
  3441.8      .1       0  4719.6     .16       0  4916.8     .12       0
  4989.9     .07       0  5026.2     .12       0  5438.9     .05       0
  6119.6      .1       0  7471.1     .05       0  7586.1      .1       0
  8022.6     .05       0    8046     .08       0  8212.5     .05       0
    8391     .08       0  8402.4      .1       0
Bank Sta=4989.9,5026.2
XS Rating Curve= 0 ,0
Exp/Cntr=0.3,0.1

Type RM Length L Ch R = 1 ,368882  ,1351,1351,1351
BEGIN DESCRIPTION:
San Miguel Creek 189.0
END DESCRIPTION:
XS GIS Cut Line= 3
      1986976.56     13546101.98       1984250.8     13546074.54
      1980534.51     13548337.57
#Sta/Elev= 30
  2274.1  578.13  2588.2  576.74  3548.2   554.1  4123.3  548.22    4495  547.99
  4713.3   547.7  4859.1  542.72  4978.3   540.3  4979.7  530.18  4987.3  528.98
    5016  530.18  5022.2  534.34  5051.3  535.58  5066.8  540.78  5077.4  541.13
  5288.5  542.57  5575.4  538.79  5589.8  535.89  5608.3  536.25  5729.2  542.72
  5856.1  545.82  6816.8  543.91  7097.2   545.8    7230  546.72    7332  547.68
  7410.2  548.68    7886  558.43  8203.7  560.57  9271.6  569.62  9351.1  570.59
#Mann= 13 ,-1 , 0
  2274.1      .1       0    4495     .16       0  4859.1     .12       0
  4979.7     .07       0    5016     .12       0  5575.4     .16       0
  5608.3     .05       0  7097.2      .1       0    7230     .05       0
    7332     .08       0  7410.2      .1       0  8203.7     .05       0
  9271.6      .1       0
Bank Sta=4979.7,5016
XS Rating Curve= 0 ,0
Exp/Cntr=0.3,0.1