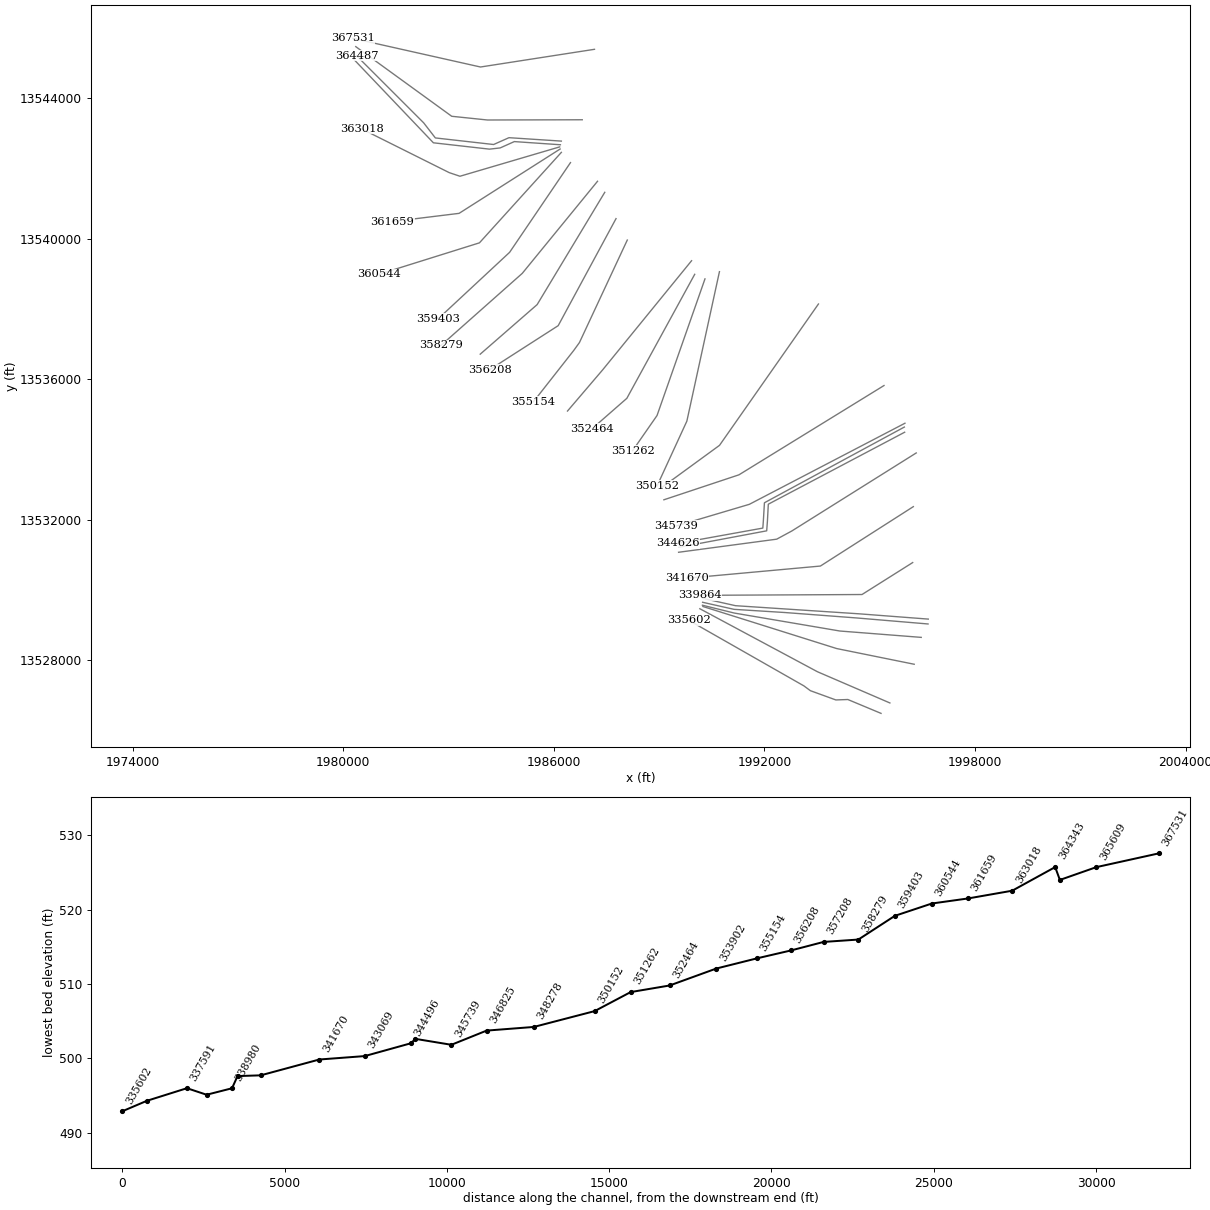
HEC-RAS study San Miguel Creek.prj: San Miguel Creek Base Level Engineering

--- San Miguel Creek.g01 (geometry) --- (continued)

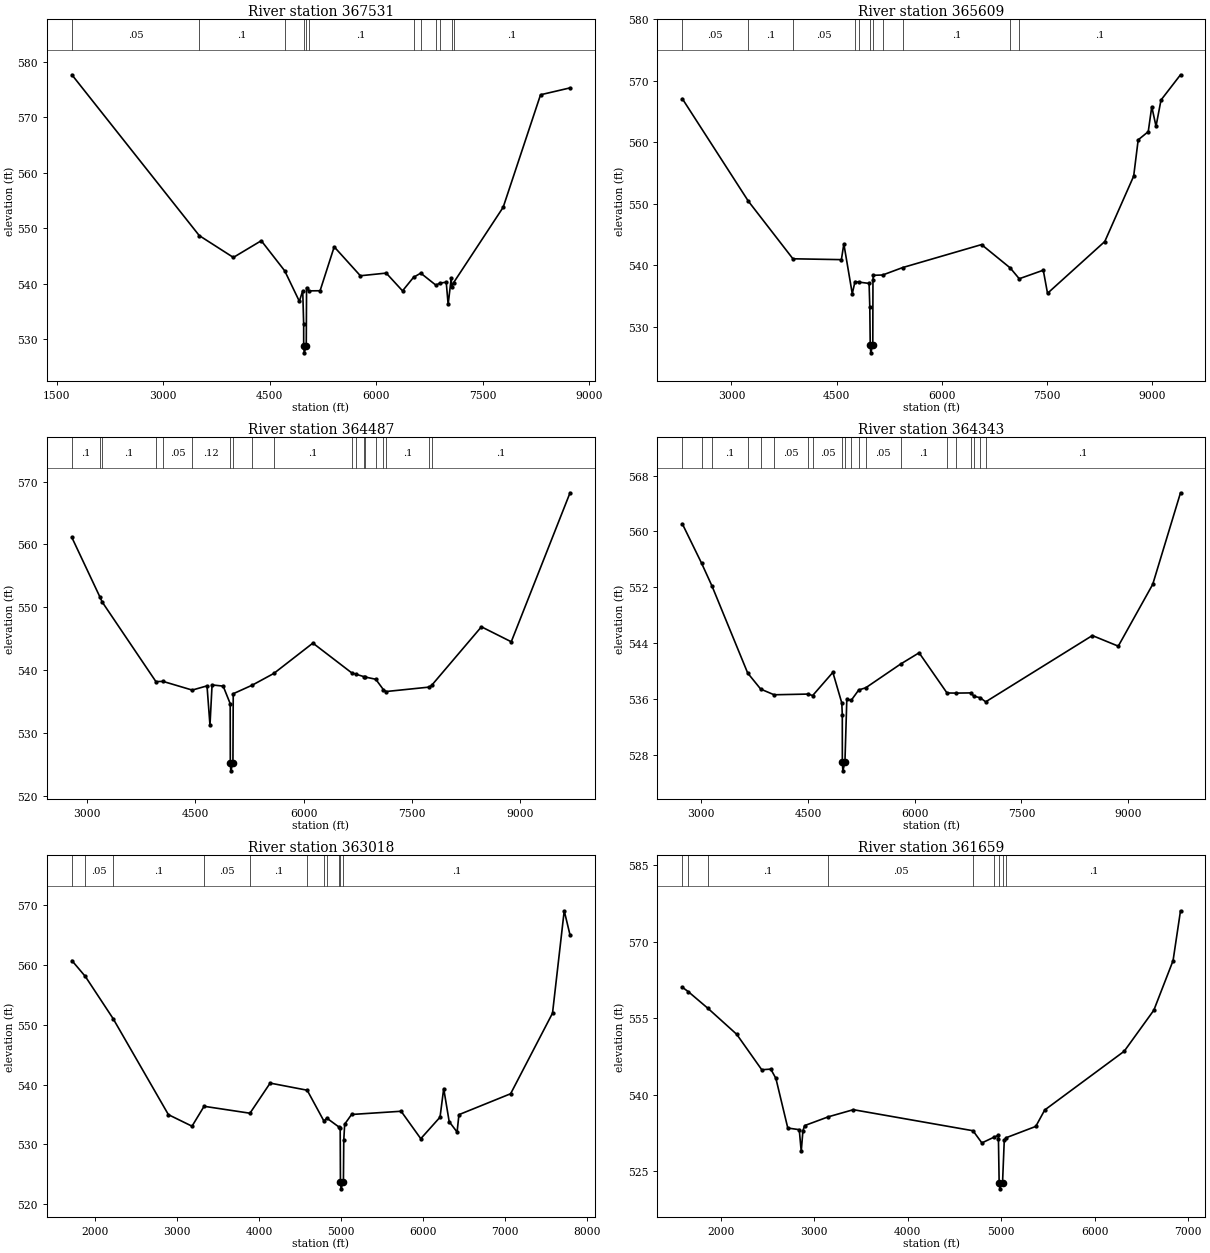
Type RM Length L Ch R = 1 ,367531  ,1922,1922,1922
BEGIN DESCRIPTION:
San Miguel Creek 188.0
END DESCRIPTION:
XS GIS Cut Line= 3
      1987158.88     13545398.86       1983910.8     13544894.54
      1980270.82     13545711.35
#Sta/Elev= 30
    1713  577.64  3507.5  548.68  3987.8  544.75    4381  547.76  4710.9  542.34
  4917.3  536.85  4964.9  538.76    4978   532.7  4978.2  528.77  4985.8  527.57
  5014.5  528.77  5018.8  539.31  5051.4  538.73  5209.3  538.75  5408.2  546.66
  5776.6  541.45    6141  541.93  6370.6  538.73  6525.7  541.17  6627.2  541.92
  6842.4  539.74  6894.2  540.12  6986.4  540.29  7013.2  536.29  7056.5  540.97
  7063.9  539.39  7091.3  540.23  7788.3  553.78  8314.8  574.04  8730.5  575.28
#Mann= 12 ,-1 , 0
    1713     .05       0  3507.5      .1       0  4710.9     .12       0
  4978.2     .07       0  5014.5     .12       0  5051.4      .1       0
  6525.7     .08       0  6627.2      .1       0  6842.4     .12       0
  6894.2      .1       0  7063.9     .16       0  7091.3      .1       0
Bank Sta=4978.2,5014.5
XS Rating Curve= 0 ,0
Exp/Cntr=0.3,0.1

Type RM Length L Ch R = 1 ,365609  ,1122,1122,1122
BEGIN DESCRIPTION:
San Miguel Creek 187.0
END DESCRIPTION:
XS GIS Cut Line= 4
      1986810.19      13543391.4       1984110.8     13543384.54
      1983091.46     13543490.36      1980357.05     13545474.75
#Sta/Elev= 30
  2300.6  567.08    3242   550.4  3877.1  541.03  4568.3  540.89  4603.3  543.45
  4723.3  535.35  4762.2  537.31  4820.9  537.23  4963.3  537.02  4973.3  533.14
  4979.7  526.92  4987.3  525.72    5016  526.92  5018.4  537.56  5023.4  538.34
  5156.9  538.39  5441.6   539.6  6566.6  543.34  6975.4  539.54  7104.1  537.78
  7446.7  539.17  7507.4  535.41  8323.7  543.84  8735.6  554.48    8800  560.39
  8943.4  561.72  8993.6  565.79  9054.3   562.6  9125.4  566.87  9403.4  570.98
#Mann= 11 ,-1 , 0
  2300.6     .05       0    3242      .1       0  3877.1     .05       0
  4762.2      .1       0  4820.9     .12       0  4979.7     .07       0
    5016     .12       0  5156.9     .16       0  5441.6      .1       0
  6975.4     .05       0  7104.1      .1       0
Bank Sta=4979.7,5016
XS Rating Curve= 0 ,0
Exp/Cntr=0.3,0.1

Type RM Length L Ch R = 1 ,364487  ,144,144,144
BEGIN DESCRIPTION:
Mapping XS 534d1d64
END DESCRIPTION:
XS GIS Cut Line= 6
      1986215.12      13542783.4      1984722.03     13542880.62
      1984284.53     13542686.18       1982624.8     13542873.68
      1982291.47     13543304.23      1980381.72     13545213.98
#Sta/Elev= 30
  2788.4   561.1  3177.4  551.63  3208.2  550.85  3952.7  538.19  4051.5  538.22
  4456.2  536.84  4661.2  537.51  4702.2  531.25  4731.2  537.66    4885  537.47
  4982.5  534.68    4984   525.2  4991.5     524  5020.3   525.2  5024.7  536.26
  5290.7  537.64  5587.6  539.49  6128.6  544.31  6666.4  539.58  6730.4  539.35
  6833.9  538.98  6852.1  538.92    7000  538.56    7107  536.89  7143.6  536.61
  7736.3  537.31    7773  537.57  8464.2   546.9  8877.8  544.52  9692.6  568.21
#Mann= 19 ,-1 , 0
  2788.4      .1       0  3177.4     .05       0  3208.2      .1       0
  3952.7     .08       0  4051.5     .05       0  4456.2     .12       0
    4984     .07       0  5020.3     .12       0  5290.7     .16       0
  5587.6      .1       0  6666.4     .08       0  6730.4      .1       0
  6833.9     .08       0  6852.1      .1       0    7000     .08       0
    7107     .05       0  7143.6      .1       0  7736.3     .12       0
    7773      .1       0
Bank Sta=4984,5020.3
XS Rating Curve= 0 ,0
Exp/Cntr=0.3,0.1

Type RM Length L Ch R = 1 ,364343  ,1325,1325,1325
BEGIN DESCRIPTION:
Mapping XS 919f25d7
END DESCRIPTION:
XS GIS Cut Line= 6
      1986187.33     13542679.23       1984874.8     13542769.51
      1984472.03     13542588.96      1984166.47     13542554.23
      1982569.25     13542734.79      1980291.49     13545123.65
#Sta/Elev= 30
  2733.8  561.09  3005.4  555.43    3151  552.18  3652.3  539.73  3835.4  537.43
  4023.5  536.62  4499.6  536.72  4565.4  536.51  4849.4  539.83    4975  535.44
  4982.1  533.71  4982.5  526.93  4990.1  525.73  5018.8  526.93  5045.5  535.99
  5107.6  535.83  5213.2  537.31  5311.4  537.62  5800.2  541.01  6061.4  542.63
  6453.4  536.88    6583  536.86  6797.2  536.89  6828.4  536.41  6918.4  536.21
  6997.3  535.61  8496.5   545.1  8860.8  543.58  9345.1  552.43  9735.6  565.54
#Mann= 20 ,-1 , 0
  2733.8      .1       0  3005.4     .05       0    3151      .1       0
  3652.3     .05       0  3835.4      .1       0  4023.5     .05       0
  4499.6      .1       0  4565.4     .05       0  4982.5     .04       0
  5018.8     .05       0  5107.6     .05       0  5213.2      .1       0
  5311.4     .05       0  5800.2      .1       0  6453.4     .05       0
    6583      .1       0  6797.2     .05       0  6828.4      .1       0
  6918.4     .05       0  6997.3      .1       0
Bank Sta=4982.5,5018.8
XS Rating Curve= 0 ,0
Exp/Cntr=0.3,0.1

Type RM Length L Ch R = 1 ,363018  ,1359,1359,1359
BEGIN DESCRIPTION:
San Miguel Creek 186.0
END DESCRIPTION:
XS GIS Cut Line= 4
      1986166.35     13542618.08      1983325.83     13541782.03
       1983020.8     13541884.54      1980524.34     13543130.69
#Sta/Elev= 30
  1717.2  560.74  1881.3  558.08  2219.6  551.03  2893.9  534.96  3181.7  533.03
  3328.7  536.36  3888.1   535.2  4134.1  540.24  4585.6  539.05  4790.1  533.88
    4825  534.38  4970.2  532.92    4988  532.66  4991.1  523.75  4998.7  522.55
  5027.4  523.75  5031.6  530.67  5042.8  533.37  5126.8  534.99  5730.8  535.53
  5970.5  530.94  6205.2  534.54  6249.9  539.32  6316.9  533.79  6413.2  532.05
  6435.6  534.96  7065.8  538.46  7576.5  551.94  7719.1  569.07  7790.2     565
#Mann= 11 ,-1 , 0
  1717.2      .1       0  1881.3     .05       0  2219.6      .1       0
  3328.7     .05       0  3888.1      .1       0  4585.6     .05       0
  4790.1      .1       0    4825     .12       0  4970.2      .1       0
  4991.1     .07       0  5027.4      .1       0
Bank Sta=4991.1,5027.4
XS Rating Curve= 0 ,0
Exp/Cntr=0.3,0.1

Type RM Length L Ch R = 1 ,361659  ,1115,1115,1115
BEGIN DESCRIPTION:
San Miguel Creek 185.0
END DESCRIPTION:
XS GIS Cut Line= 3
      1986179.96     13542558.04       1983300.8     13540724.54
      1981394.32     13540490.45
#Sta/Elev= 30
  1586.6  561.06    1651  560.19  1859.2  556.95  2168.4  551.84  2436.8  544.88
  2533.7     545  2588.3  543.18  2715.7  533.44  2838.4  533.12  2859.6  528.84
  2877.8  532.91    2896  533.92  3150.8  535.65  3417.5  537.04  4698.9  532.91
  4793.9  530.52  4926.3  531.67  4968.3     532  4971.3  531.27  4978.9  522.71
  4986.5  521.51  5015.2  522.71  5033.5     531  5053.9  531.54  5371.1  533.76
  5466.8  536.98  6318.1  548.51  6635.2  556.56    6841  566.28  6920.8  576.07
#Mann= 9 ,-1 , 0
  1586.6      .1       0    1651     .05       0  1859.2      .1       0
  3150.8     .05       0  4698.9      .1       0  4926.3     .12       0
  4978.9     .07       0  5015.2     .12       0  5053.9      .1       0
Bank Sta=4978.9,5015.2
XS Rating Curve= 0 ,0
Exp/Cntr=0.3,0.1

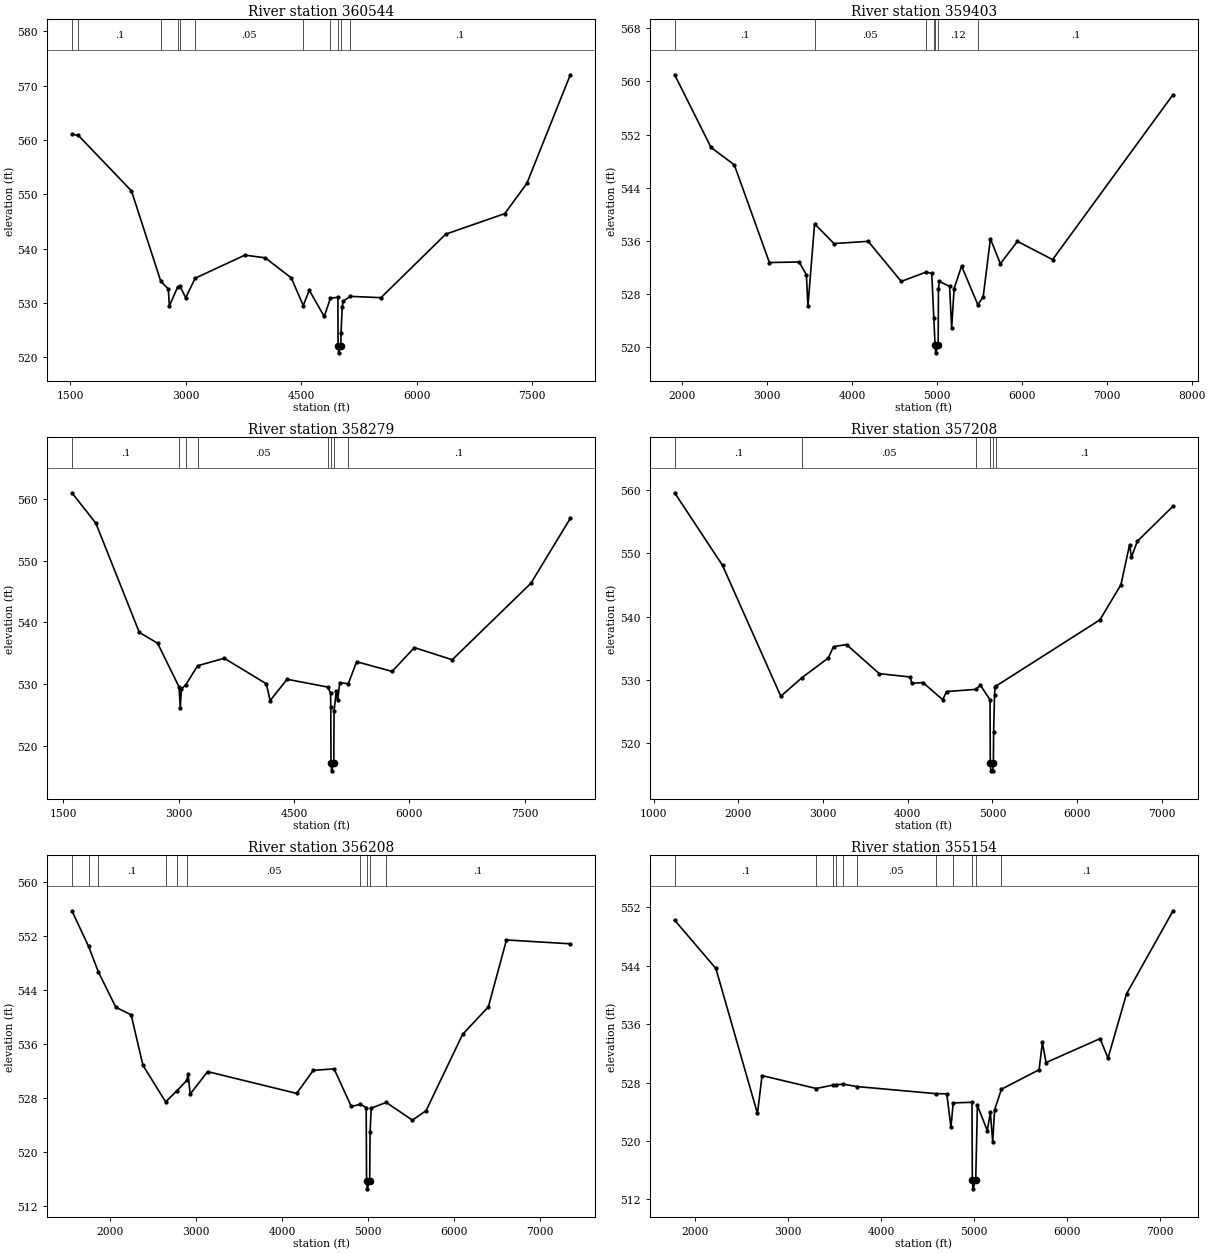
Type RM Length L Ch R = 1 ,360544  ,1141,1141,1141
BEGIN DESCRIPTION:
San Miguel Creek 184.0
END DESCRIPTION:
XS GIS Cut Line= 3
      1986214.94     13542462.42       1983880.8     13539884.54
      1981024.33     13538990.54
#Sta/Elev= 30
  1522.4  561.06  1605.6  560.85  2295.8  550.63  2675.9  534.02  2773.7  532.59
  2787.9  529.46  2893.5  532.88  2926.9  533.07  3000.1  530.95    3122  534.56
  3768.4  538.81  4033.8  538.31    4370  534.62  4526.1  529.54  4603.9  532.34
  4798.5  527.52  4878.6  530.88  4975.6  531.06  4978.4  522.03    4986  520.83
  5014.7  522.03  5015.9   524.4  5032.1  529.28  5045.4  530.36  5136.7  531.22
  5534.7  530.98  6376.1  542.67  7142.4  546.45  7429.2  552.02  7993.1     572
#Mann= 11 ,-1 , 0
  1522.4     .05       0  1605.6      .1       0  2675.9     .07       0
  2893.5     .12       0  2926.9      .1       0    3122     .05       0
  4526.1      .1       0  4878.6     .12       0  4978.4     .07       0
  5014.7     .12       0  5136.7      .1       0
Bank Sta=4978.4,5014.7
XS Rating Curve= 0 ,0
Exp/Cntr=0.3,0.1

Type RM Length L Ch R = 1 ,359403  ,1124,1124,1124
BEGIN DESCRIPTION:
San Miguel Creek 183.0
END DESCRIPTION:
XS GIS Cut Line= 3
      1986474.95     13542170.59       1984740.8     13539614.54
      1982704.89     13537720.07
#Sta/Elev= 30
  1911.2  560.98  2339.7  550.05  2613.7  547.44    3027  532.75  3377.1  532.83
  3462.7  530.91  3480.7  526.17  3559.2  538.57  3787.6   535.6  4190.4  535.94
  4579.5  529.91  4870.3   531.3  4939.1  531.11  4963.7  524.35  4978.2  520.37
  4985.8  519.17  5014.6  520.37    5018  528.83  5028.5  529.91  5148.7  529.17
  5173.7  522.87    5202  528.81  5290.4  532.22  5482.1  526.39    5545   527.6
    5630  536.32  5746.8  532.57  5948.3  535.93  6362.4  533.19    7781     558
#Mann= 7 ,-1 , 0
  1911.2      .1       0  3559.2     .05       0  4870.3      .1       0
  4963.7     .12       0  4978.2     .07       0  5014.6     .12       0
  5482.1      .1       0
Bank Sta=4978.2,5014.6
XS Rating Curve= 0 ,0
Exp/Cntr=0.3,0.1

Type RM Length L Ch R = 1 ,358279  ,1071,1071,1071
BEGIN DESCRIPTION:
San Miguel Creek 182.0
END DESCRIPTION:
XS GIS Cut Line= 3
      1987245.31     13541638.86       1985100.8     13539014.54
        1982785.     13536961.68
#Sta/Elev= 30
  1610.9  560.96  1922.7  556.03    2488  538.37    2726  536.62  3004.9  529.55
  3020.7   526.2  3035.1  529.21    3092  529.89  3246.6  532.98  3593.2  534.19
  4140.3  530.06  4189.8  527.34  4410.2  530.79  4936.1  529.54  4975.6  528.59
  4978.8  526.26  4981.5  517.18  4989.1  515.98  5017.9  517.18  5021.5   525.7
    5050  528.86  5067.5  527.38    5096  530.24  5206.3  530.07  5315.5  533.63
  5775.9  532.06  6066.5  535.92  6558.7  533.95  7582.4  546.33  8094.7  556.82
#Mann= 8 ,-1 , 0
  1610.9      .1       0  3004.9     .07       0    3092      .1       0
  3246.6     .05       0  4936.1     .12       0  4981.5     .07       0
  5017.9     .12       0  5206.3      .1       0
Bank Sta=4981.5,5017.9
XS Rating Curve= 0 ,0
Exp/Cntr=0.3,0.1

Type RM Length L Ch R = 1 ,357208  ,1000,1000,1000
BEGIN DESCRIPTION:
San Miguel Creek 181.0
END DESCRIPTION:
XS GIS Cut Line= 3
      1987451.46     13541324.16        1985525.       13538125.
      1983903.31     13536712.66
#Sta/Elev= 30
  1248.1  559.52  1813.2  548.07  2501.6  527.42  2751.9  530.36  3062.9  533.47
    3124  535.25  3277.4  535.58  3663.9  530.99  4031.9  530.46  4045.8  529.46
  4180.5  529.59  4413.5  526.87  4458.2  528.17  4804.3  528.51  4858.2  529.17
  4971.8  526.86  4974.8  516.86  4982.4  515.66  5003.6  515.66  5011.2  516.86
  5014.3  521.76  5025.2  527.65  5032.2  528.95  5047.7  529.08    6269  539.47
  6517.3  545.01  6619.8  551.33  6641.2  549.38  6711.9  551.88    7133  557.41
#Mann= 6 ,-1 , 0
  1248.1      .1       0  2751.9     .05       0  4804.3     .12       0
  4974.8     .07       0  5011.2     .12       0  5047.7      .1       0
Bank Sta=4974.8,5011.2
XS Rating Curve= 0 ,0
Exp/Cntr=0.3,0.1

Type RM Length L Ch R = 1 ,356208  ,1054,1054,1054
BEGIN DESCRIPTION:
San Miguel Creek 180.0
END DESCRIPTION:
XS GIS Cut Line= 3
      1987772.51     13540574.61        1986125.       13537525.
      1984170.82     13536269.52
#Sta/Elev= 30
  1559.9   555.7  1754.1  550.41    1868  546.62  2070.5  541.41    2248  540.29
  2384.6  532.83  2648.2   527.4  2779.9  529.04  2893.9  530.58    2909  531.52
  2933.7  528.56  3136.5  531.88  4170.8  528.65  4362.3  532.06  4605.4  532.29
  4804.8  526.72  4910.1  527.03  4977.8  526.56  4982.3  515.72  4989.9  514.52
  5018.7  515.72  5023.2  522.98  5036.6  526.47  5210.4  527.32  5514.9  524.69
  5673.7   526.1  6097.5  537.39    6397  541.47  6607.4  551.38  7348.8  550.81
#Mann= 10 ,-1 , 0
  1559.9      .1       0  1754.1     .05       0    1868      .1       0
  2648.2     .07       0  2779.9      .1       0  2893.9     .05       0
  4910.1     .12       0  4982.3     .07       0  5018.7     .12       0
  5210.4      .1       0
Bank Sta=4982.3,5018.7
XS Rating Curve= 0 ,0
Exp/Cntr=0.3,0.1

Type RM Length L Ch R = 1 ,355154  ,1252,1252,1252
BEGIN DESCRIPTION:
San Miguel Creek 179.0
END DESCRIPTION:
XS GIS Cut Line= 4
      1988093.46      13539964.2       1986730.8     13537044.54
      1986567.64     13536818.52      1985420.08     13535357.59
#Sta/Elev= 30
    1778  550.24  2221.1  543.63  2668.2  523.77  2717.6  528.96    3300  527.19
  3479.3  527.66  3517.9  527.71  3589.7  527.79  3735.8  527.46  4583.4  526.49
  4703.9  526.46  4748.4  521.87  4772.9  525.22  4974.7   525.3  4978.5  514.65
  4986.1  513.45  5014.9  514.65  5032.9  524.87  5139.7  521.41  5172.2  523.93
  5197.3  519.87  5218.3  524.29    5291  527.09  5696.2  529.76  5731.5   533.5
  5770.7  530.74  6351.4  534.02  6437.2  531.35  6636.1  540.15  7136.5  551.53
#Mann= 11 ,-1 , 0
    1778      .1       0    3300     .05       0  3479.3     .16       0
  3517.9     .05       0  3589.7      .1       0  3735.8     .05       0
  4583.4     .16       0  4772.9     .12       0  4978.5     .07       0
  5014.9     .12       0    5291      .1       0
Bank Sta=4978.5,5014.9
XS Rating Curve= 0 ,0
Exp/Cntr=0.3,0.1

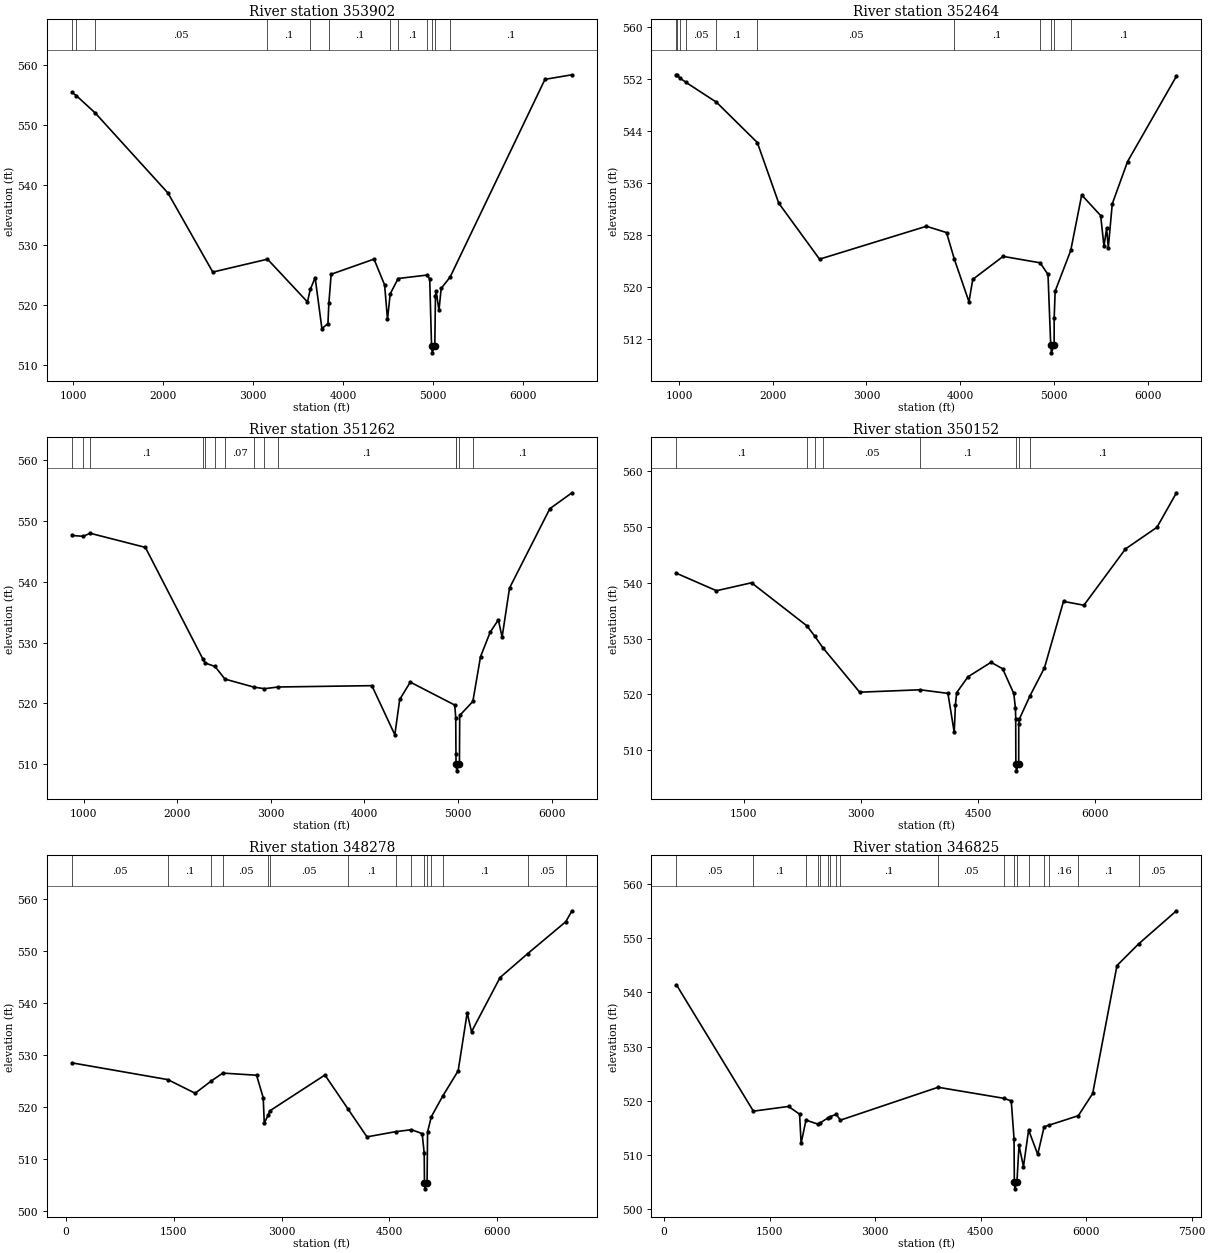
Type RM Length L Ch R = 1 ,353902  ,1438,1438,1438
BEGIN DESCRIPTION:
San Miguel Creek 178.0
END DESCRIPTION:
XS GIS Cut Line= 3
      1989924.98     13539374.98       1987390.8     13536264.54
      1986389.99     13535092.36
#Sta/Elev= 30
   987.9  555.45  1035.3  554.93  1245.4  552.04  2054.3  538.69  2551.9  525.53
  3159.5  527.68  3603.2  520.56  3634.8  522.63  3688.7  524.61  3763.7  516.12
  3830.9  516.94  3840.9   520.3  3866.8  525.17  4342.9  527.69  4460.3  523.38
  4492.3  517.66  4522.4   521.9  4610.7  524.46  4930.8  525.03  4961.2  524.41
  4981.5  513.28  4989.1  512.08  5017.9  513.28    5025  521.61  5032.1  522.36
    5064  519.16  5088.7  522.81  5187.3  524.69  6241.5  557.63  6541.3  558.39
#Mann= 12 ,-1 , 0
   987.9     .05       0  1035.3      .1       0  1245.4     .05       0
  3159.5      .1       0  3634.8     .16       0  3840.9      .1       0
  4522.4     .12       0  4610.7      .1       0  4930.8     .12       0
  4981.5     .07       0  5017.9     .12       0  5187.3      .1       0
Bank Sta=4981.5,5017.9
XS Rating Curve= 0 ,0
Exp/Cntr=0.3,0.1

Type RM Length L Ch R = 1 ,352464  ,1202,1202,1202
BEGIN DESCRIPTION:
San Miguel Creek 177.0
END DESCRIPTION:
XS GIS Cut Line= 3
      1990014.06      13538987.7       1988080.8     13535454.54
      1987095.18     13534593.12
#Sta/Elev= 30
   972.5  552.61   973.6  552.64  1011.8  552.11  1074.1  551.47  1399.4  548.41
  1835.5   542.2  2064.2  532.86  2499.6  524.23  3640.1   529.3  3854.9  528.33
  3939.1   524.2  4094.3  517.67  4135.1  521.12    4459  524.66    4854  523.67
    4938  521.87    4967     511  4974.6   509.8  5003.4     511    5004   515.2
  5014.4  519.31  5180.6  525.57  5297.8  534.12  5499.9  530.95  5535.5  526.22
  5563.5  528.97  5581.6     526  5623.8  532.75  5787.1  539.27    6309  552.43
#Mann= 11 ,-1 , 0
   972.5     .05       0   973.6      .1       0  1011.8     .08       0
  1074.1     .05       0  1399.4      .1       0  1835.5     .05       0
  3939.1      .1       0    4854     .12       0    4967     .07       0
  5003.4     .12       0  5180.6      .1       0
Bank Sta=4967,5003.4
XS Rating Curve= 0 ,0
Exp/Cntr=0.3,0.1

Type RM Length L Ch R = 1 ,351262  ,1110,1110,1110
BEGIN DESCRIPTION:
San Miguel Creek 175.0
END DESCRIPTION:
XS GIS Cut Line= 3
      1990307.02     13538857.46       1988940.8     13534964.54
       1988245.8     13533964.41
#Sta/Elev= 30
   874.3  547.62   993.4  547.48  1068.8  547.98  1658.5  545.66  2270.5  527.38
  2297.7  526.65  2403.3  526.07    2509     524  2820.8  522.67  2931.6  522.42
  3078.8   522.7  4079.4  522.92  4324.7  514.84  4376.9  520.65  4489.9   523.5
  4965.1  519.73  4975.7  517.64  4978.1  511.62  4978.7  510.11  4986.3  508.91
  5015.1  510.11  5018.3  518.02  5158.5  520.32  5240.5  527.68  5344.8  531.75
  5431.2  533.74  5471.3  530.89  5550.4  538.97  5981.2  552.02  6217.9  554.64
#Mann= 14 ,-1 , 0
   874.3      .1       0   993.4     .05       0  1068.8      .1       0
  2270.5     .05       0  2297.7     .08       0  2403.3     .05       0
    2509     .07       0  2820.8     .12       0  2931.6     .05       0
  3078.8      .1       0  4978.1     .12       0  4978.7     .07       0
  5015.1     .12       0  5158.5      .1       0
Bank Sta=4978.7,5015.1
XS Rating Curve= 0 ,0
Exp/Cntr=0.3,0.1

Type RM Length L Ch R = 1 ,350152  ,1874,1874,1874
BEGIN DESCRIPTION:
San Miguel Creek 174.0
END DESCRIPTION:
XS GIS Cut Line= 3
      1990719.34     13539063.59       1989790.8     13534804.54
        1988940.     13532955.05
#Sta/Elev= 30
   640.9  541.67  1152.7  538.55  1600.9  539.97  2310.4  532.26    2412  530.38
  2513.6  528.35  2984.2  520.41  3756.2  520.84    4113   520.2  4193.5  513.23
  4208.9  518.17  4224.2  520.32    4370  523.17  4664.3  525.75  4812.7   524.6
  4955.1  520.18  4976.5  517.55  4979.7  515.67  4981.6  507.55  4989.2  506.35
    5018  507.55  5018.8  514.77  5026.4   515.6  5161.9  519.75  5347.5  524.76
  5591.1  536.64    5852  535.96  6383.7  546.02  6786.4  549.89  7035.8  556.06
#Mann= 8 ,-1 , 0
   640.9      .1       0  2310.4     .05       0    2412      .1       0
  2513.6     .05       0  3756.2      .1       0  4981.6     .07       0
    5018      .1       0  5161.9      .1       0
Bank Sta=4981.6,5018
XS Rating Curve= 0 ,0
Exp/Cntr=0.3,0.1

Type RM Length L Ch R = 1 ,348278  ,1453,1453,1453
BEGIN DESCRIPTION:
San Miguel Creek 173.0
END DESCRIPTION:
XS GIS Cut Line= 3
      1993539.83     13538142.08       1990720.8     13534114.54
      1989071.18     13532910.99
#Sta/Elev= 30
    83.9  528.48  1416.6  525.26  1798.3  522.63  2018.3  524.95  2182.4  526.51
  2652.8   526.1  2745.2  521.77    2760  516.85  2813.4  518.43    2839  519.26
    3604  526.14  3920.8  519.69  4189.1  514.23  4588.8  515.23  4808.8  515.61
  4957.3  514.85  4985.6  511.08  4989.2  505.42  4996.8  504.22  5025.6  505.42
  5032.5  515.18  5084.2  518.09  5241.1  522.03  5458.2  526.95  5583.7   538.1
  5644.3  534.47  6041.7  544.92    6426  549.52  6955.5  555.66    7042  557.77
#Mann= 15 ,-1 , 0
    83.9     .05       0  1416.6      .1       0  2018.3     .08       0
  2182.4     .05       0  2813.4      .1       0    2839     .05       0
  3920.8      .1       0  4588.8     .16       0  4808.8     .12       0
  4989.2     .07       0  5025.6     .12       0  5084.2     .16       0
  5241.1      .1       0    6426     .05       0  6955.5      .1       0
Bank Sta=4989.2,5025.6
XS Rating Curve= 0 ,0
Exp/Cntr=0.3,0.1

Type RM Length L Ch R = 1 ,346825  ,1086,1086,1086
BEGIN DESCRIPTION:
San Miguel Creek 171.0
END DESCRIPTION:
XS GIS Cut Line= 3
        1995408.     13535818.98        1991275.       13533275.
      1989136.35     13532563.79
#Sta/Elev= 30
   177.1  541.39  1270.7  518.07  1769.9  518.94  1927.3  517.51  1948.6  512.12
    2018  516.41  2189.8  515.67  2220.9  515.92  2334.2  516.84  2361.6  517.06
  2447.5  517.48  2507.6  516.41  3895.8  522.48  4826.7  520.45  4935.6  519.97
  4975.3  513.01  4979.8  504.93  4987.4  503.73  5016.2  504.93  5046.1  511.75
  5109.4  507.84  5182.5  514.59  5312.2  510.09  5402.9  515.18  5474.7  515.49
  5889.1  517.23  6093.3  521.33  6438.8  544.95  6745.9  548.94  7284.1  555.06
#Mann= 18 ,-1 , 0
   177.1     .05       0  1270.7      .1       0    2018     .12       0
  2189.8      .1       0  2220.9     .12       0  2334.2     .05       0
  2361.6     .12       0  2447.5     .05       0  2507.6      .1       0
  3895.8     .05       0  4826.7     .12       0  4979.8     .07       0
  5016.2     .12       0  5182.5     .16       0  5402.9      .1       0
  5474.7     .16       0  5889.1      .1       0  6745.9     .05       0
Bank Sta=4979.8,5016.2
XS Rating Curve= 0 ,0
Exp/Cntr=0.3,0.1

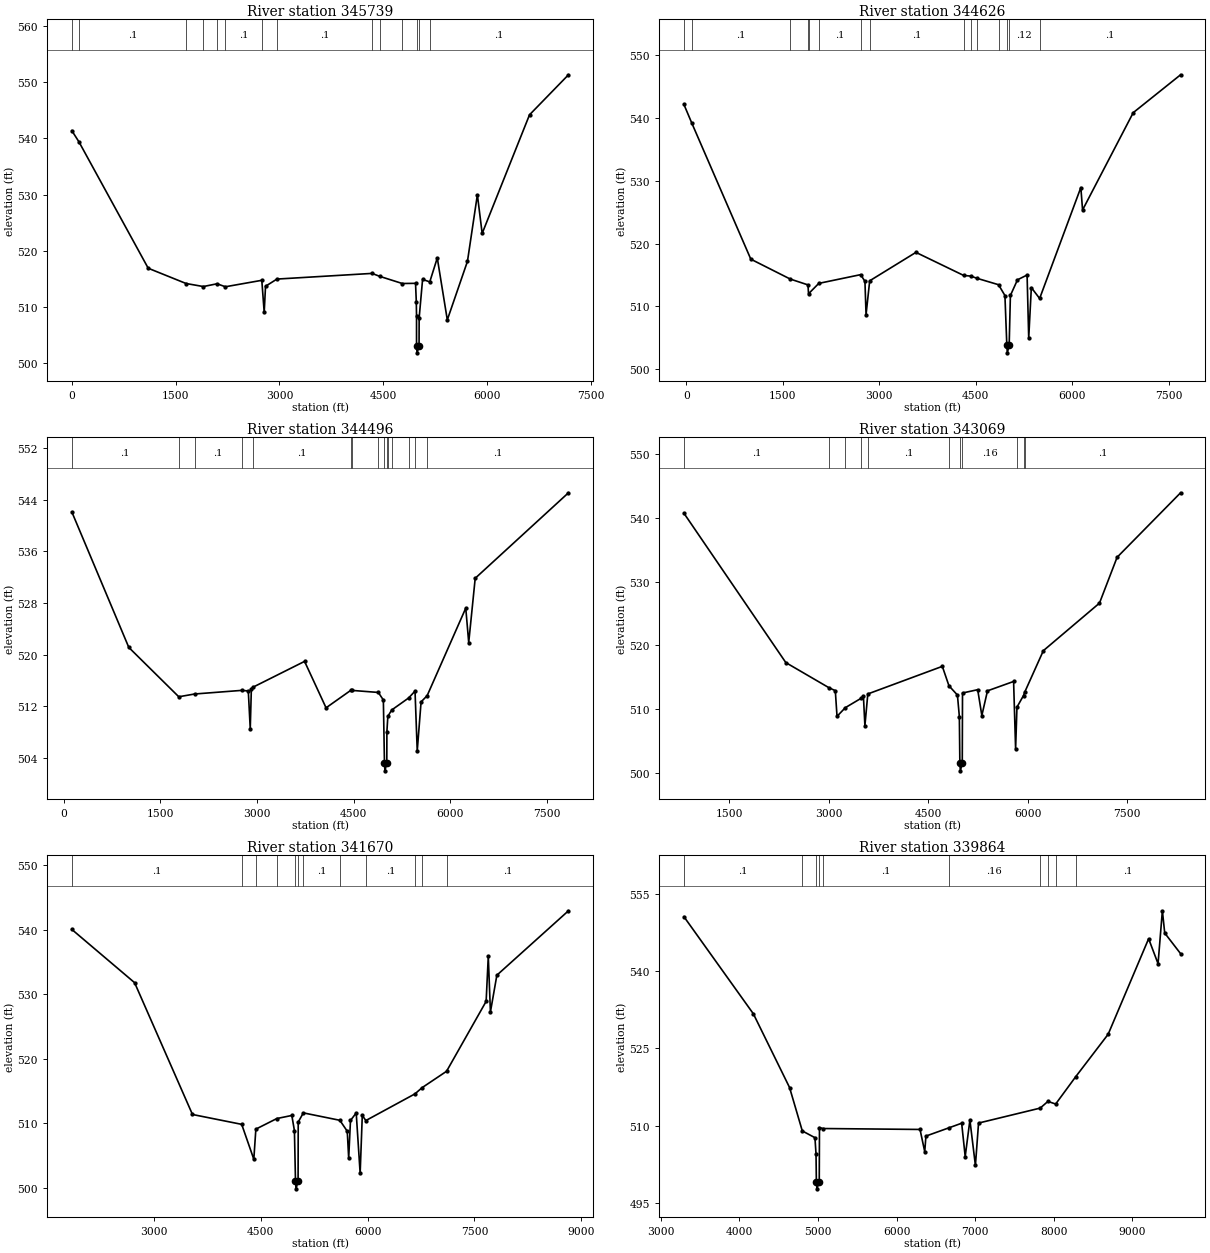
Type RM Length L Ch R = 1 ,345739  ,1113,1113,1113
BEGIN DESCRIPTION:
San Miguel Creek 170.0
END DESCRIPTION:
XS GIS Cut Line= 3
      1996004.75     13534744.75       1991570.8     13532434.54
      1989484.25      13531815.3
#Sta/Elev= 30
      .3   541.4   103.5   539.4  1104.3  516.89  1651.4  514.17  1900.5  513.63
    2099  514.12  2219.7  513.59  2745.6  514.74  2780.1  509.04  2799.3  513.68
  2964.3  514.96  4339.1  515.97  4448.2  515.45  4775.5  514.17  4966.8   514.2
  4977.9  510.94  4981.2  508.33  4981.3  503.02  4988.9  501.82  5017.7  503.02
  5019.1  508.04  5068.7   514.9  5172.5  514.46    5281  518.72  5425.9  507.69
  5717.1  518.12  5860.4  529.98  5929.5  523.09  6613.8  544.22  7176.5  551.35
#Mann= 14 ,-1 , 0
      .3     .05       0   103.5      .1       0  1651.4     .12       0
  1900.5      .1       0    2099     .05       0  2219.7      .1       0
  2745.6     .12       0  2964.3      .1       0  4339.1     .08       0
  4448.2     .16       0  4775.5     .12       0  4981.3     .07       0
  5017.7     .12       0  5172.5      .1       0
Bank Sta=4981.3,5017.7
XS Rating Curve= 0 ,0
Exp/Cntr=0.3,0.1

Type RM Length L Ch R = 1 ,344626  ,130,130,130
BEGIN DESCRIPTION:
Mapping XS 7b328871
END DESCRIPTION:
XS GIS Cut Line= 5
      1995987.29     13534635.97      1992001.05     13532479.07
       1991970.8     13531974.54      1991955.16     13531757.49
       1989529.4     13531319.46
#Sta/Elev= 30
   -37.8   542.1    85.3  539.12  1001.9  517.51  1614.5  514.35  1890.5  513.42
    1899  512.01  2058.5  513.66  2709.4  515.05    2776  513.98  2793.2  508.69
  2849.9  514.07  3568.6  518.59  4311.1  514.92  4421.1  514.82  4517.3  514.47
  4852.4  513.45    4952  511.73  4981.6  503.82  4989.2  502.62    5018  503.82
  5037.1  511.74  5147.4  514.23  5296.5  514.99  5321.9  504.97  5362.6  512.99
  5491.6  511.26  6132.2   528.9  6158.9  525.33  6946.6   540.8  7682.6  546.82
#Mann= 15 ,-1 , 0
   -37.8     .05       0    85.3      .1       0  1614.5     .12       0
  1890.5      .1       0    1899     .05       0  2058.5      .1       0
  2709.4     .12       0  2849.9      .1       0  4311.1     .08       0
  4421.1     .05       0  4517.3     .08       0  4852.4     .12       0
  4981.6     .07       0    5018     .12       0  5491.6      .1       0
Bank Sta=4981.6,5018
XS Rating Curve= 0 ,0
Exp/Cntr=0.3,0.1

Type RM Length L Ch R = 1 ,344496  ,1427,1427,1427
BEGIN DESCRIPTION:
Mapping XS 55b231b6
END DESCRIPTION:
XS GIS Cut Line= 5
      1995995.99     13534488.41      1992111.41     13532438.04
      1992086.35     13531958.99       1992065.4     13531679.36
      1989556.56     13531208.23
#Sta/Elev= 30
   127.8  542.13  1012.2  521.14  1787.4   513.5    2034  513.93  2763.6  514.49
  2865.9   514.4  2896.1  508.56  2913.4  514.75  2946.1  515.02  3738.8  518.98
  4072.4  511.79  4459.1  514.52  4470.6  514.49    4883  514.17  4961.4     513
  4978.3  503.23  4985.9  502.03  5014.7  503.23    5016  508.06  5030.8  510.47
  5091.9  511.46  5353.1  513.31  5452.6  514.38  5486.9  505.12  5546.6  512.71
  5640.7  513.67  6239.8  527.23  6285.6   521.9  6386.2  531.85  7833.1  545.09
#Mann= 15 ,-1 , 0
   127.8      .1       0  1787.4     .12       0    2034      .1       0
  2763.6     .12       0  2946.1      .1       0  4459.1     .08       0
  4470.6      .1       0    4883     .16       0  4978.3     .07       0
  5014.7     .16       0  5030.8     .05       0  5091.9     .08       0
  5353.1     .05       0  5452.6     .12       0  5640.7      .1       0
Bank Sta=4978.3,5014.7
XS Rating Curve= 0 ,0
Exp/Cntr=0.3,0.1

Type RM Length L Ch R = 1 ,343069  ,1399,1399,1399
BEGIN DESCRIPTION:
Mapping XS 7797c3c3
END DESCRIPTION:
XS GIS Cut Line= 4
      1996325.84     13533898.13       1992780.8     13531674.54
      1992350.13     13531441.52      1989555.01     13531068.26
#Sta/Elev= 30
   815.3  540.71  2352.9  517.28  3003.5  513.34  3099.4  512.88  3125.3  508.85
  3250.7  510.21  3485.3  511.66  3523.6  512.02  3546.1  507.38    3590  512.36
  4714.3  516.69  4814.5  513.64  4942.3  512.19  4971.2  508.82  4978.9   501.5
  4986.5   500.3  5015.3   501.5    5019  512.51  5248.2  513.03  5310.7  508.98
  5395.7  512.85  5789.9  514.32  5820.2  503.73  5840.5  510.29  5939.3  512.11
  5957.5  512.64  6238.9  519.15  7085.7  526.61  7351.6   533.8  8309.6  543.92
#Mann= 11 ,-1 , 0
   815.3      .1       0  3003.5     .12       0  3250.7      .1       0
  3485.3     .12       0    3590      .1       0  4814.5     .16       0
  4978.9     .07       0  5015.3     .16       0  5840.5     .08       0
  5939.3     .12       0  5957.5      .1       0
Bank Sta=4978.9,5015.3
XS Rating Curve= 0 ,0
Exp/Cntr=0.3,0.1

Type RM Length L Ch R = 1 ,341670  ,1806,1806,1806
BEGIN DESCRIPTION:
Mapping XS 3dde8a63
END DESCRIPTION:
XS GIS Cut Line= 3
      1996243.52     13532368.47      1993595.94     13530675.76
      1989787.38     13530328.54
#Sta/Elev= 30
  1851.7  540.07  2732.4  531.81  3544.3  511.37  4234.8  509.84  4404.8  504.43
  4433.4   509.1  4727.5  510.74  4937.9  511.22  4974.3  508.87  4989.4  501.04
    4997  499.84  5025.8  501.04  5027.7  510.19  5099.3  511.62  5611.3  510.47
  5715.6  508.77  5735.6  504.58  5760.8  510.44  5841.1  511.61  5896.3  502.25
  5926.4  511.22  5976.3  510.43  6665.6  514.57  6764.1  515.52  7108.5  518.07
  7663.6  528.91  7693.7  535.89  7723.9  527.27  7814.2  532.97  8818.5  542.96
#Mann= 12 ,-1 , 0
  1851.7      .1       0  4234.8     .12       0  4433.4      .1       0
  4727.5     .16       0  4989.4     .07       0  5025.8     .16       0
  5099.3      .1       0  5611.3     .16       0  5976.3      .1       0
  6665.6     .08       0  6764.1     .16       0  7108.5      .1       0
Bank Sta=4989.4,5025.8
XS Rating Curve= 0 ,0
Exp/Cntr=0.3,0.1

Type RM Length L Ch R = 1 ,339864  ,714,714,714
BEGIN DESCRIPTION:
San Miguel Creek 168.0
END DESCRIPTION:
XS GIS Cut Line= 3
      1996224.97     13530774.98       1994780.8     13529864.54
      1990165.66     13529841.56
#Sta/Elev= 30
  3292.8  550.59  4176.7  531.72  4637.4   517.4  4799.7  508.96  4960.6  507.65
  4974.3  504.51  4978.7  499.11  4986.4  497.71  5015.5  499.11  5018.3  509.62
  5060.8  509.43  6298.3  509.25  6358.3  504.93  6373.3  507.96  6661.5  509.54
  6828.3  510.46  6873.3  503.99  6933.3  511.07  7003.3  502.25  7043.3  510.49
  7828.3   513.4  7926.3   514.7    8025  514.19  8278.8  519.47  8693.3  527.75
  9208.4  546.31  9328.4  541.46  9383.4  551.74  9413.4  547.41  9615.2  543.41
#Mann= 10 ,-1 , 0
  3292.8      .1       0  4799.7     .12       0  4978.7     .07       0
  5015.5     .12       0  5060.8      .1       0  6661.5     .16       0
  7828.3     .05       0  7926.3     .08       0    8025     .16       0
  8278.8      .1       0
Bank Sta=4978.7,5015.5
XS Rating Curve= 0 ,0
Exp/Cntr=0.3,0.1

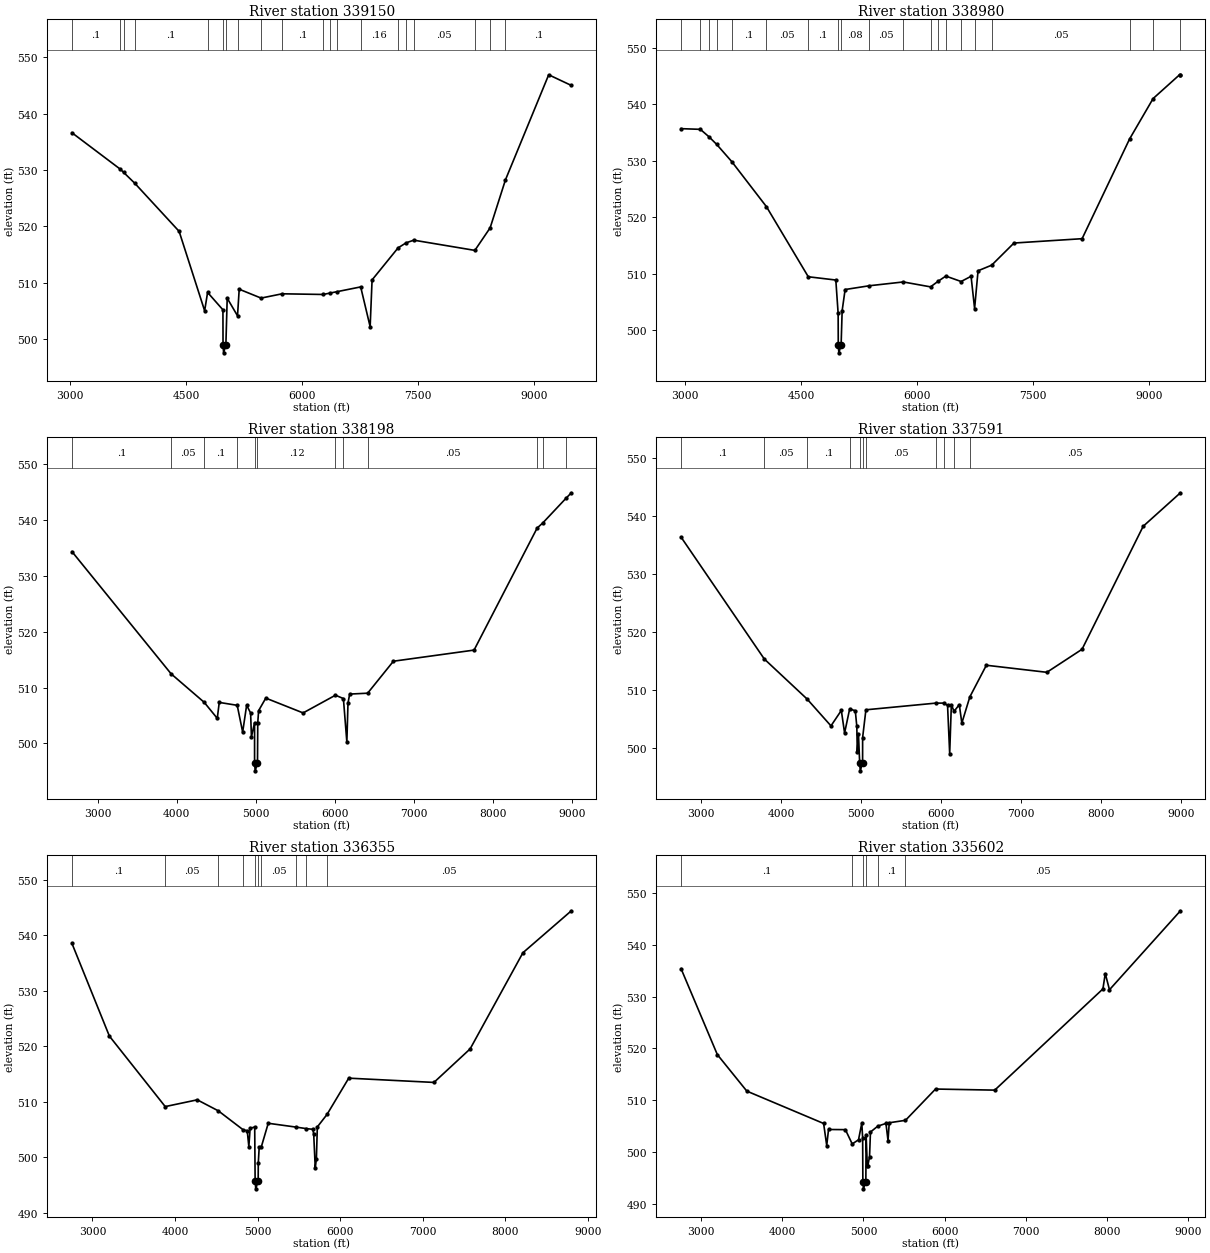
Type RM Length L Ch R = 1 ,339150  ,170,170,170
BEGIN DESCRIPTION:
Mapping XS a472c79b
END DESCRIPTION:
XS GIS Cut Line= 4
      1996669.87     13529164.28       1994700.8     13529314.54
      1991176.87     13529546.22      1990246.34     13529754.55
#Sta/Elev= 30
  3025.2   536.6  3652.9  530.12  3692.6  529.59  3837.3  527.66  4411.6  519.13
  4741.6  505.06  4779.7  508.31  4978.2  505.23  4979.5  499.01  4987.2  497.61
  5016.3  499.01  5033.4  507.29  5166.8  504.17  5188.7  508.88  5471.6  507.31
    5744  508.07  6274.9  507.95  6360.4  508.19  6459.2  508.46    6760  509.29
  6882.4  502.23  6907.4  510.53    7244  516.21    7348   517.1  7446.8  517.57
  8236.8  515.76  8434.3  519.75  8632.8  528.26    9192  546.87  9485.1  544.98
#Mann= 20 ,-1 , 0
  3025.2      .1       0  3652.9     .05       0  3692.6     .08       0
  3837.3      .1       0  4779.7     .12       0  4979.5     .07       0
  5016.3     .12       0  5166.8      .1       0  5471.6     .08       0
    5744      .1       0  6274.9     .16       0  6360.4     .05       0
  6459.2     .08       0    6760     .16       0    7244     .05       0
    7348     .08       0  7446.8     .05       0  8236.8     .08       0
  8434.3     .05       0  8632.8      .1       0
Bank Sta=4979.5,5016.3
XS Rating Curve= 0 ,0
Exp/Cntr=0.3,0.1

Type RM Length L Ch R = 1 ,338980  ,782,782,782
BEGIN DESCRIPTION:
Mapping XS b8ef4c06
END DESCRIPTION:
XS GIS Cut Line= 5
      1996663.01     13529025.38      1994614.16      13529197.9
      1992579.64     13529351.78       1991135.2     13529442.05
      1990239.64     13529643.38
#Sta/Elev= 30
  2943.9  535.66  3193.7  535.54  3303.8  534.24  3402.8  532.91  3600.6  529.82
  4048.8  521.85  4590.1  509.44  4946.5  508.86  4976.6  502.94  4978.3  497.37
    4986  495.97  5015.1  497.37  5028.5  503.44  5066.9  507.18  5381.4  507.85
  5819.3  508.52  6172.2  507.65  6271.1  508.65  6369.9  509.56  6567.6   508.6
  6696.5  509.52  6742.1  503.81  6786.8   510.5    6963  511.49  7251.4  515.41
  8133.1  516.18  8747.3  533.83  9051.8  540.99    9394   545.2  9405.5  545.14
#Mann= 20 ,-1 , 0
  2943.9      .1       0  3193.7     .05       0  3303.8     .08       0
  3402.8     .05       0  3600.6      .1       0  4048.8     .05       0
  4590.1      .1       0  4978.3     .07       0  5015.1     .08       0
  5381.4     .05       0  5819.3     .08       0  6172.2     .05       0
  6271.1     .08       0  6369.9     .05       0  6567.6      .1       0
  6742.1     .08       0    6963     .05       0  8747.3     .08       0
  9051.8     .08       0    9394      .1       0
Bank Sta=4978.3,5015.1
XS Rating Curve= 0 ,0
Exp/Cntr=0.3,0.1

Type RM Length L Ch R = 1 ,338198  ,607,607,607
BEGIN DESCRIPTION:
San Miguel Creek 167.0
END DESCRIPTION:
XS GIS Cut Line= 4
      1996468.53     13528643.44       1994150.8     13528824.54
      1991142.63     13529336.24      1990234.16     13529559.56
#Sta/Elev= 30
  2675.2  534.32  3928.7  512.45  4346.4  507.36  4511.8  504.49  4536.9  507.34
  4763.9  506.82  4832.8  502.03  4882.9  506.83  4933.1  505.45  4943.7  501.17
  4983.2  503.73  4983.4   496.5  4991.1   495.1  5020.2   496.5  5023.6  503.71
  5034.4  505.87  5125.1  508.11  5596.6  505.46  6005.6  508.63  6105.9  508.03
  6149.6  500.25  6163.9  507.21  6185.1  508.83  6412.3  508.99  6737.9  514.71
  7757.3   516.7  8554.7  538.54  8622.9   539.4  8920.8  543.88  8986.9  544.84
#Mann= 12 ,-1 , 0
  2675.2      .1       0  3928.7     .05       0  4346.4      .1       0
  4763.9     .12       0  4983.4     .07       0  5020.2     .12       0
  6005.6     .07       0  6105.9      .1       0  6412.3     .05       0
  8554.7     .08       0  8622.9     .05       0  8920.8     .08       0
Bank Sta=4983.4,5020.2
XS Rating Curve= 0 ,0
Exp/Cntr=0.3,0.1

Type RM Length L Ch R = 1 ,337591  ,1236,1236,1236
BEGIN DESCRIPTION:
San Miguel Creek 166.0
END DESCRIPTION:
XS GIS Cut Line= 3
      1996268.53      13527877.7       1994060.8     13528324.54
      1990247.66     13529523.55
#Sta/Elev= 30
  2747.5  536.38  3789.5  515.31  4325.1  508.39  4623.8  503.75  4753.4  506.42
  4794.2  502.52  4857.5  506.67  4928.1  506.37  4947.2  503.66  4953.4  499.16
  4967.7  502.39  4982.8  497.38  4990.5  495.98  5019.6  497.38    5020  501.74
    5061  506.53    5932  507.68  6036.2  507.69  6082.8  507.28  6109.4  498.96
  6130.3  507.42    6164  506.26  6229.9  507.42  6261.4  504.23  6361.5  508.76
  6568.2  514.23  7325.4  513.01  7765.7  516.99  8530.9  538.25  8997.2  544.04
#Mann= 11 ,-1 , 0
  2747.5      .1       0  3789.5     .05       0  4325.1      .1       0
  4857.5     .12       0  4982.8     .07       0  5019.6     .12       0
    5061     .05       0    5932     .07       0  6036.2     .12       0
    6164      .1       0  6361.5     .05       0
Bank Sta=4982.8,5019.6
XS Rating Curve= 0 ,0
Exp/Cntr=0.3,0.1

Type RM Length L Ch R = 1 ,336355  ,753,753,753
BEGIN DESCRIPTION:
San Miguel Creek 165.0
END DESCRIPTION:
XS GIS Cut Line= 3
      1995574.99       13526775.       1993510.8     13527664.54
      1990160.55      13529459.5
#Sta/Elev= 30
  2752.3  538.56  3205.7  521.84    3882  509.12  4269.8  510.34  4525.6  508.35
  4827.8  504.91  4875.2  504.77  4894.7  501.91  4910.5  505.21  4965.7  505.43
  4970.9  495.68  4978.6  494.28  5007.7  495.68  5009.1  498.96    5020  501.74
  5043.9  501.76  5129.7  506.11  5470.8  505.41  5584.3  505.16  5669.1  505.02
  5680.1  504.19  5699.2  498.05    5713  499.75  5724.1  505.45  5841.5   507.7
  6104.5  514.25  7136.6  513.48  7574.9  519.53  8214.3  536.88  8800.8  544.45
#Mann= 10 ,-1 , 0
  2752.3      .1       0    3882     .05       0  4525.6      .1       0
  4827.8     .12       0  4970.9     .07       0  5007.7     .12       0
  5043.9     .05       0  5470.8     .07       0  5584.3      .1       0
  5841.5     .05       0
Bank Sta=4970.9,5007.7
XS Rating Curve= 0 ,0
Exp/Cntr=0.3,0.1

Type RM Length L Ch R = 1 ,335602  ,109,109,109
BEGIN DESCRIPTION:
Mapping XS 32151fd0
END DESCRIPTION:
XS GIS Cut Line= 6
      1995323.34     13526478.06      1994377.17     13526873.03
      1994035.73     13526860.77      1993310.56     13527124.36
      1993124.27     13527262.03      1989839.69     13529133.79
#Sta/Elev= 30
  2753.3   535.4  3200.4   518.8  3563.6  511.75  4509.6   505.5  4547.8  501.24
    4570  504.34  4777.6  504.31  4861.8  501.55  4939.4  502.35  4979.9  505.58
  4990.4  502.66  4992.9  494.28  5000.6  492.88  5029.7  494.28  5032.9  503.36
  5047.3  497.37  5054.5  497.36  5075.3  499.12  5086.5  503.85  5177.4  504.99
  5277.4  505.51  5302.8  502.21  5317.8  505.64    5518  506.11  5888.2  512.15
  6617.4  511.94  7949.8  531.48  7978.7  534.45  8030.6  531.32  8904.8  546.57
#Mann= 6 ,-1 , 0
  2753.3      .1       0  4861.8     .12       0  4992.9     .07       0
  5029.7     .12       0  5177.4      .1       0    5518     .05       0
Bank Sta=4992.9,5029.7
XS Rating Curve= 0 ,0
Exp/Cntr=0.3,0.1