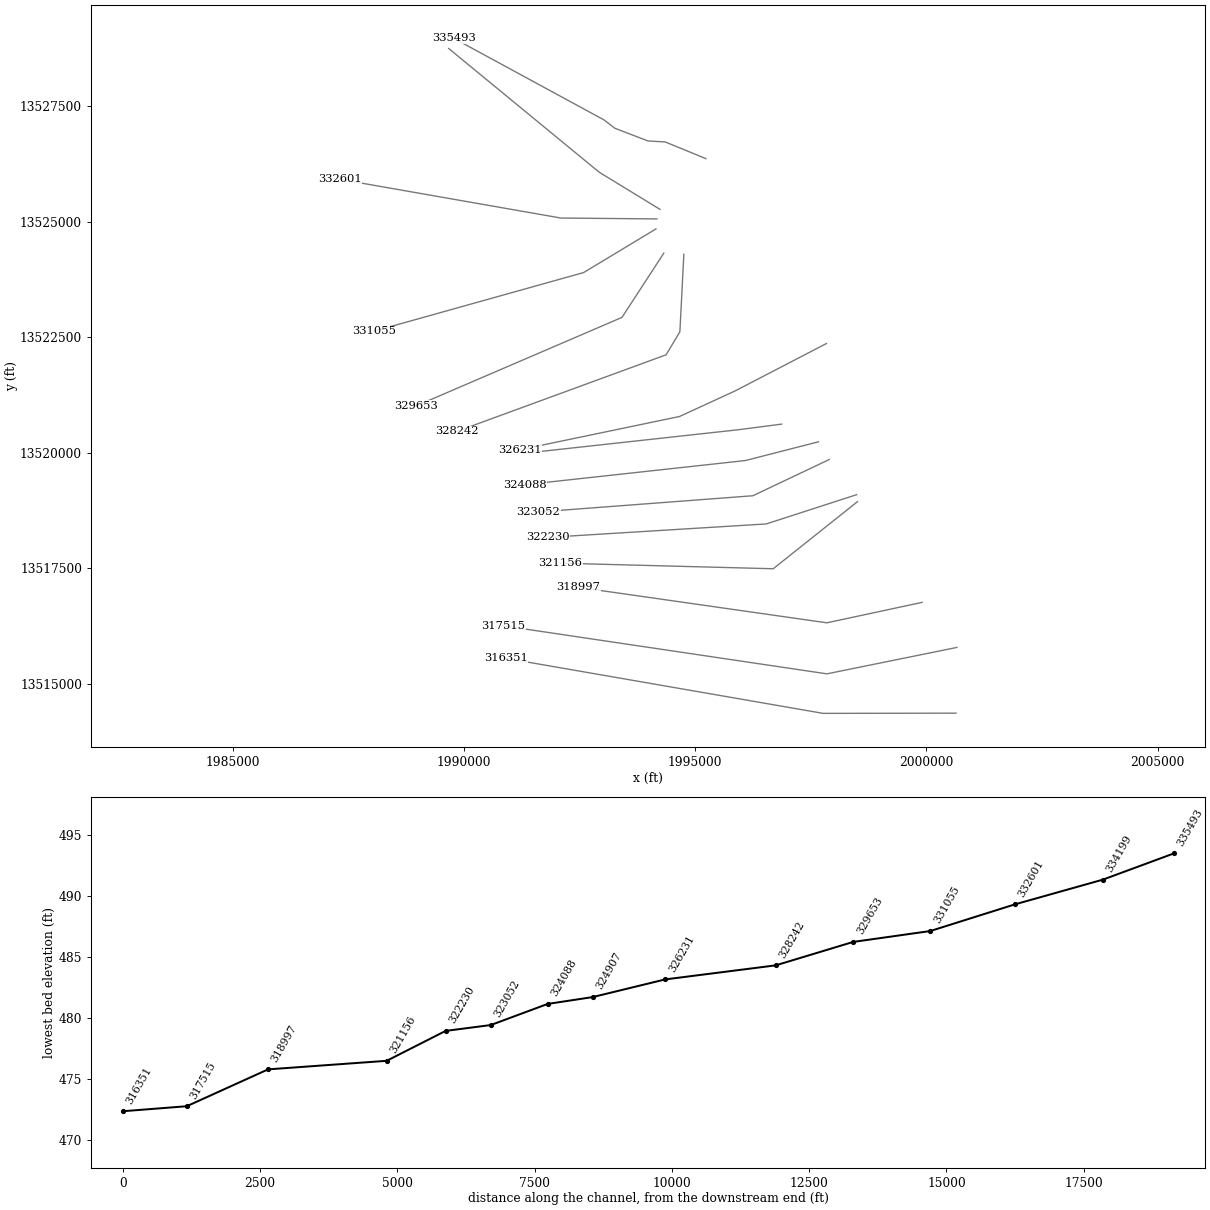
HEC-RAS study San Miguel Creek.prj: San Miguel Creek Base Level Engineering

--- San Miguel Creek.g01 (geometry) --- (continued)

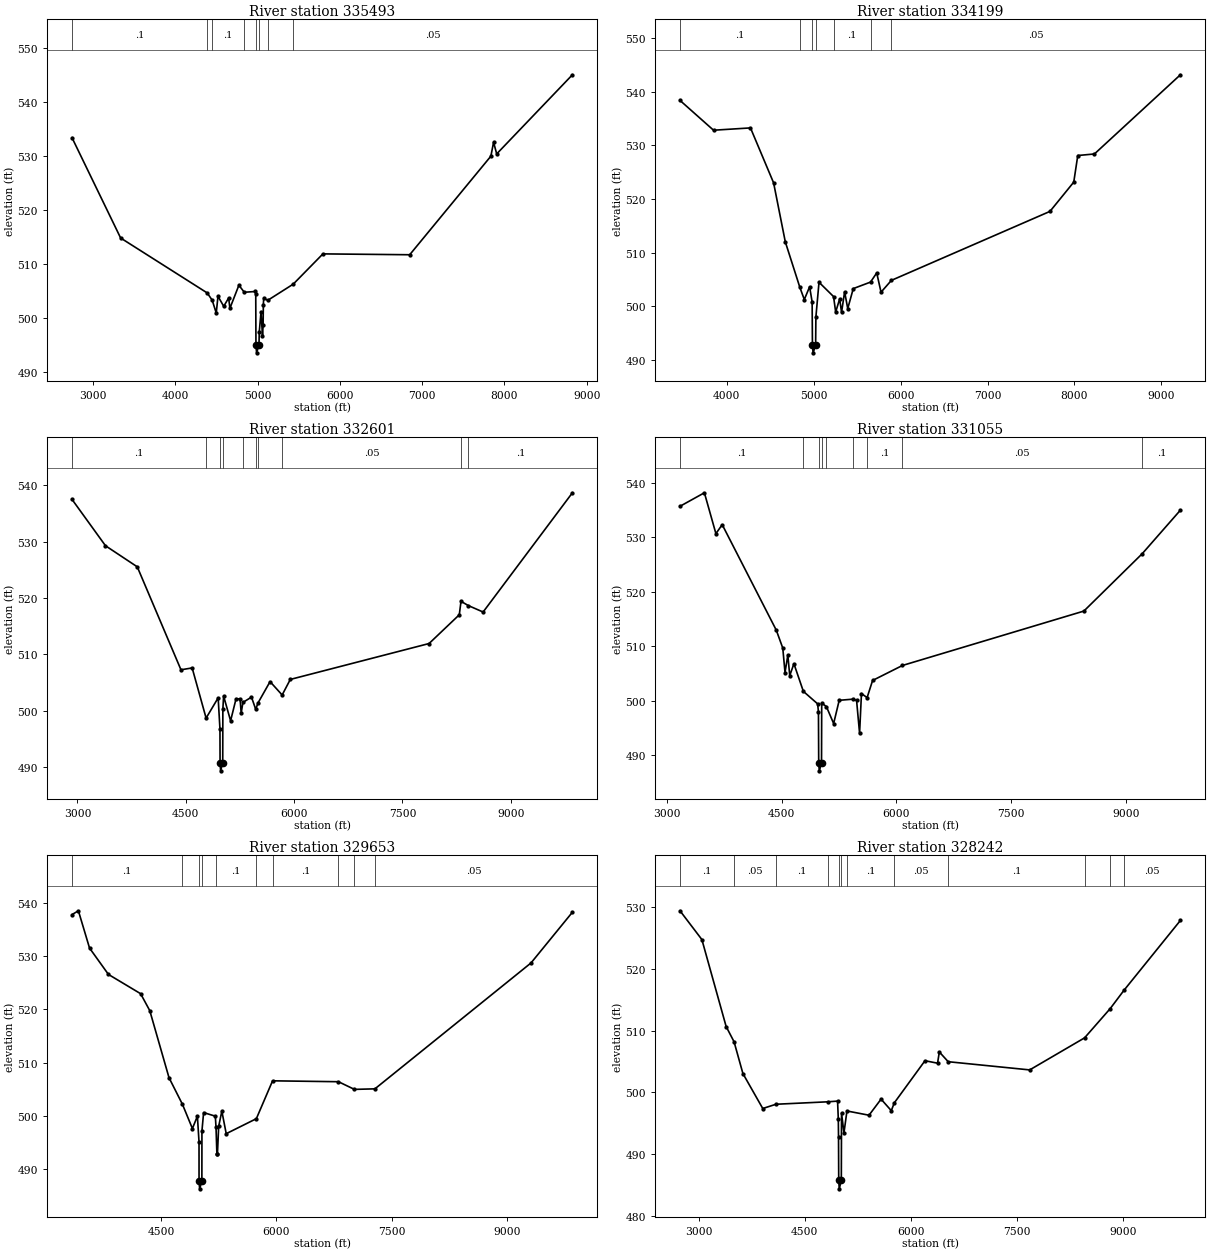
Type RM Length L Ch R = 1 ,335493  ,1294,1294,1294
BEGIN DESCRIPTION:
San Miguel Creek 164.0
END DESCRIPTION:
XS GIS Cut Line= 6
      1995235.84     13526369.88      1994354.74     13526731.87
      1993983.65      13526752.7      1993267.58     13527027.37
       1993030.7     13527209.08      1989784.76     13528973.88
#Sta/Elev= 30
  2741.9  533.32  3333.2  514.76  4385.4   504.6  4446.6  503.25  4495.8  500.87
  4516.9  503.98  4586.6  502.12  4646.7  503.66  4661.8  501.75  4771.1  506.02
  4836.7  504.72    4972  504.86  4976.1  504.32  4978.6  494.91  4986.3  493.51
  5015.4  494.91  5018.7  497.31  5040.5  501.15  5058.1  496.66  5065.4   498.6
  5068.5   502.4  5072.5  503.59  5122.3  503.23  5431.7  506.22  5792.8  511.82
  6847.9  511.66    7835   529.9  7867.8  532.47  7905.8  530.32  8826.3  544.96
#Mann= 8 ,-1 , 0
  2741.9      .1       0  4385.4     .16       0  4446.6      .1       0
  4836.7     .12       0  4978.6     .07       0  5015.4     .12       0
  5122.3      .1       0  5431.7     .05       0
Bank Sta=4978.6,5015.4
XS Rating Curve= 0 ,0
Exp/Cntr=0.3,0.1

Type RM Length L Ch R = 1 ,334199  ,1598,1598,1598
BEGIN DESCRIPTION:
San Miguel Creek 163.0
END DESCRIPTION:
XS GIS Cut Line= 3
      1994242.76     13525272.67       1992930.8     13526074.54
      1989673.36     13528754.84
#Sta/Elev= 30
  3462.4  538.35  3848.4   532.8  4273.3  533.23  4539.3     523  4673.8  512.02
  4841.4  503.54  4892.5  501.28  4953.5  503.66  4982.5  500.83  4985.9  492.76
  4993.6  491.36  5022.7  492.76  5025.6  498.02  5061.5   504.5    5229  501.83
  5253.1  498.96  5299.3  501.41  5320.8  498.89    5356  502.73  5391.9   499.6
  5455.7  503.32  5654.1  504.53  5725.5  506.24    5775  502.65  5894.1  504.85
  7718.1  517.69  7991.8  523.14    8038  528.09  8229.6  528.38  9218.4  543.12
#Mann= 7 ,-1 , 0
  3462.4      .1       0  4841.4     .12       0  4985.9     .07       0
  5022.7     .12       0    5229      .1       0  5654.1     .12       0
  5894.1     .05       0
Bank Sta=4985.9,5022.7
XS Rating Curve= 0 ,0
Exp/Cntr=0.3,0.1

Type RM Length L Ch R = 1 ,332601  ,1546,1546,1546
BEGIN DESCRIPTION:
San Miguel Creek 162.0
END DESCRIPTION:
XS GIS Cut Line= 3
      1994176.41     13525065.63       1992100.8     13525084.54
      1987319.41     13525922.72
#Sta/Elev= 30
  2924.3  537.51  3388.2  529.28  3828.2  525.54  4433.3  507.27  4588.3   507.6
  4781.4   498.7  4948.3  502.29  4973.3  496.77  4974.9  490.74  4982.6  489.34
  5011.7  490.74  5013.5  500.27  5023.7  502.61  5120.6  498.22  5196.2  502.13
  5252.1  502.09  5267.3  499.58  5291.3  501.48    5410  502.42  5468.6  500.25
  5500.8   501.4  5667.2  505.17  5834.6   502.8  5947.5  505.56  7869.2  511.93
  8287.7  517.03  8311.6  519.42    8412  518.67  8617.6  517.52  9854.3  538.68
#Mann= 10 ,-1 , 0
  2924.3      .1       0  4781.4     .12       0  4974.9     .07       0
  5011.7     .12       0  5291.3      .1       0  5468.6     .16       0
  5500.8      .1       0  5834.6     .05       0  8311.6     .08       0
    8412      .1       0
Bank Sta=4974.9,5011.7
XS Rating Curve= 0 ,0
Exp/Cntr=0.3,0.1

Type RM Length L Ch R = 1 ,331055  ,1402,1402,1402
BEGIN DESCRIPTION:
San Miguel Creek 161.0
END DESCRIPTION:
XS GIS Cut Line= 3
      1994154.64     13524848.59       1992590.8     13523904.54
      1988056.56     13522635.07
#Sta/Elev= 30
  3173.3  535.68    3492  538.16  3642.4  530.67  3724.9  532.31  4431.5  512.94
  4515.8  509.67  4544.9  505.19  4581.8  508.38  4606.7  504.62  4661.3   506.8
  4784.6  501.73  4970.9  499.44  4981.6  497.96    4985  488.55  4992.7  487.15
  5021.8  488.55  5024.2  499.58  5085.4  498.94    5180  495.83  5252.7  500.09
  5433.5   500.3  5479.5  500.08  5518.8  494.04  5543.4  501.33    5617  500.58
  5688.8  503.73  6078.7  506.48  8448.1  516.46  9210.6  526.99  9708.6  534.97
#Mann= 9 ,-1 , 0
  3173.3      .1       0  4784.6     .12       0    4985     .07       0
  5021.8     .12       0  5085.4      .1       0  5433.5     .12       0
    5617      .1       0  6078.7     .05       0  9210.6      .1       0
Bank Sta=4985,5021.8
XS Rating Curve= 0 ,0
Exp/Cntr=0.3,0.1

Type RM Length L Ch R = 1 ,329653  ,1411,1411,1411
BEGIN DESCRIPTION:
San Miguel Creek 159.0
END DESCRIPTION:
XS GIS Cut Line= 3
        1994325.       13524325.       1993420.8     13522934.54
      1988968.01     13521018.31
#Sta/Elev= 30
  3341.4  537.82  3424.4  538.54  3569.4  531.53  3815.4  526.57  4233.5  522.95
  4352.8  519.76  4602.8  507.15  4777.1  502.16  4906.9   497.6  4971.8  499.92
  4992.9  495.08  4993.2  487.66  5000.9  486.26    5030  487.66  5030.8  497.14
  5052.6   500.6    5205  499.92  5213.8  497.84  5225.3  492.83  5232.2  492.74
  5248.5  498.01  5289.6  500.87  5346.5  496.63  5738.3  499.45  5949.3  506.57
  6805.8   506.4  7013.3  504.96  7279.9  505.06  9309.3  528.73  9847.6  538.27
#Mann= 10 ,-1 , 0
  3341.4      .1       0  4777.1     .12       0  4993.2     .07       0
    5030     .12       0  5213.8      .1       0  5738.3     .05       0
  5949.3      .1       0  6805.8     .16       0  7013.3      .1       0
  7279.9     .05       0
Bank Sta=4993.2,5030
XS Rating Curve= 0 ,0
Exp/Cntr=0.3,0.1

Type RM Length L Ch R = 1 ,328242  ,2011,2011,2011
BEGIN DESCRIPTION:
San Miguel Creek 158.0
END DESCRIPTION:
XS GIS Cut Line= 4
      1994758.27     13524301.87      1994672.72     13522623.64
        1994375.       13522125.      1989851.69     13520466.91
#Sta/Elev= 30
  2735.2  529.44    3045  524.77  3388.3  510.66  3500.3  508.19  3625.7  503.03
  3906.1  497.37  4093.2  498.06  4832.4  498.46  4964.3  498.57    4975  495.61
  4977.9  492.67  4980.6  485.74  4988.3  484.34  5017.5  485.74  5020.3  496.63
  5054.7  493.41  5097.1  496.97  5409.1  496.28  5579.8  498.89  5724.3  497.02
  5767.1  498.29    6201  505.12  6378.7  504.72  6403.9  506.54  6529.3  504.96
  7682.2  503.63  8458.7  508.83  8821.6  513.58    9015  516.53    9814  527.87
#Mann= 12 ,-1 , 0
  2735.2      .1       0  3500.3     .05       0  4093.2      .1       0
  4832.4     .12       0  4980.6     .07       0  5017.5     .12       0
  5097.1      .1       0  5767.1     .05       0  6529.3      .1       0
  8458.7     .05       0  8821.6      .1       0    9015     .05       0
Bank Sta=4980.6,5017.5
XS Rating Curve= 0 ,0
Exp/Cntr=0.3,0.1

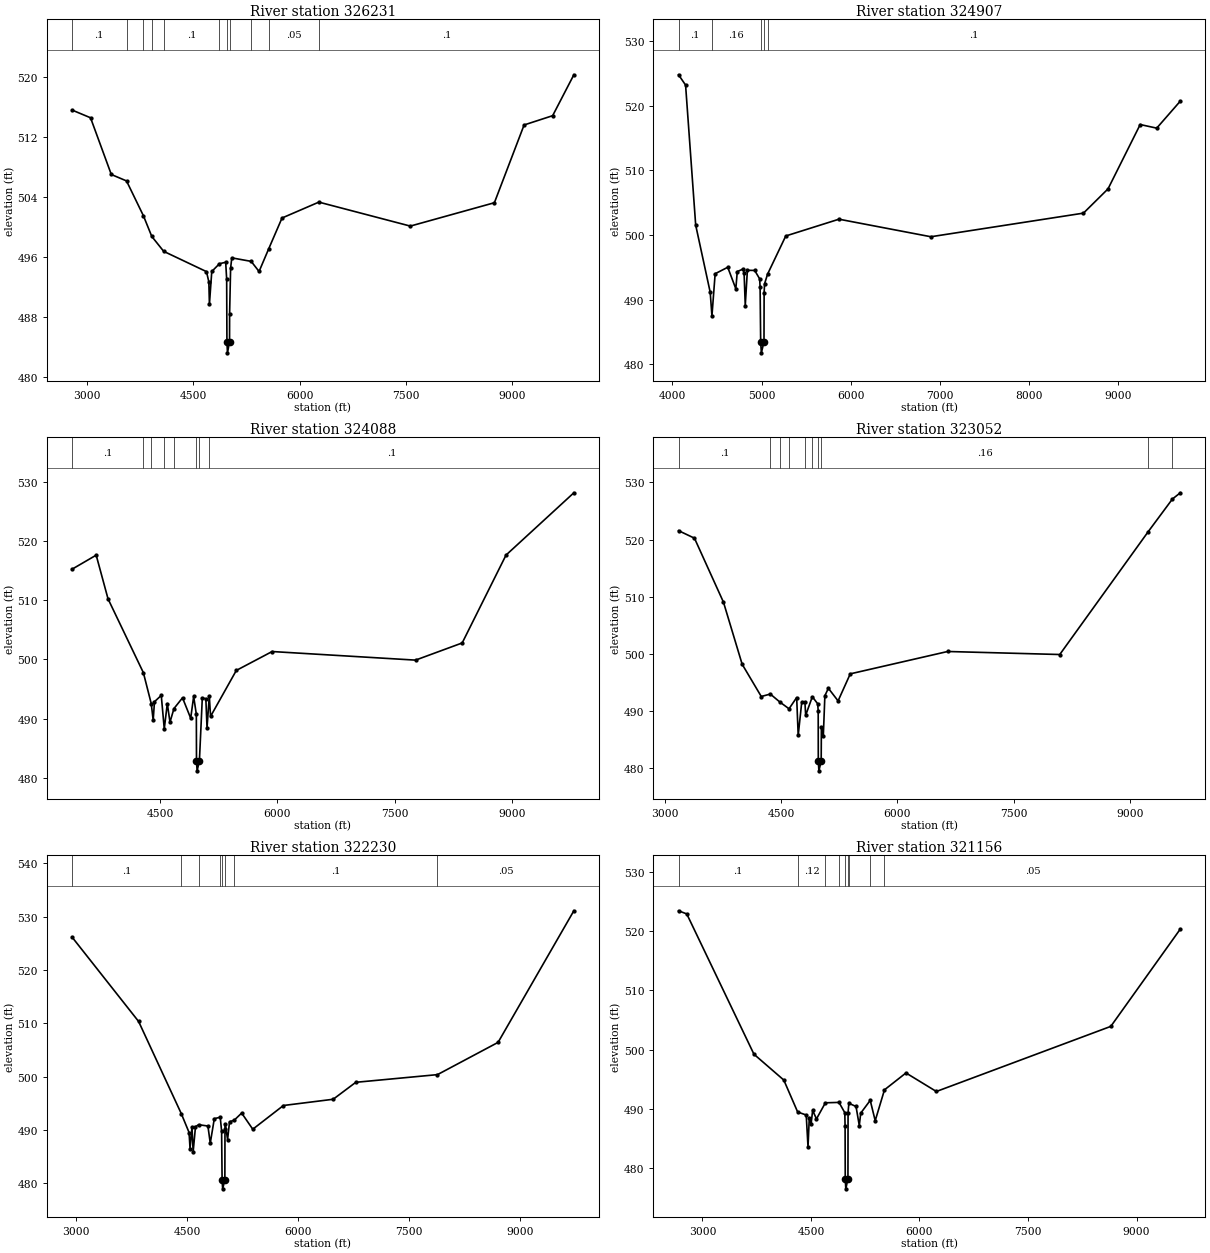
Type RM Length L Ch R = 1 ,326231  ,1324,1324,1324
BEGIN DESCRIPTION:
Mapping XS 2f5ce966
END DESCRIPTION:
XS GIS Cut Line= 4
      1997842.13     13522369.68      1995871.66     13521345.38
      1994665.07     13520789.83      1991210.24     13520069.35
#Sta/Elev= 30
  2789.5   515.6    3050  514.57  3342.9     507  3557.6  506.14  3796.4  501.48
  3913.9  498.73  4081.9  496.74  4685.6  494.03  4718.8  492.66    4727  489.67
  4760.2  494.05  4868.7  495.09  4956.4  495.28  4970.2  493.03    4974  484.69
  4981.7  483.19  5010.9  484.69  5011.7  488.38  5025.9  494.49  5042.4  495.87
    5316   495.4  5427.3  494.05  5562.5  497.06  5751.1  501.19  6270.7  503.31
  7560.9  500.11  8746.9  503.23  9165.8  513.61  9568.7  514.85  9867.8  520.31
#Mann= 11 ,-1 , 0
  2789.5      .1       0  3557.6     .16       0  3796.4      .1       0
  3913.9     .16       0  4081.9      .1       0  4868.7     .12       0
    4974     .07       0  5010.9     .12       0    5316      .1       0
  5562.5     .05       0  6270.7      .1       0
Bank Sta=4974,5010.9
XS Rating Curve= 0 ,0
Exp/Cntr=0.3,0.1

Type RM Length L Ch R = 1 ,324907  ,819,819,819
BEGIN DESCRIPTION:
San Miguel Creek 157.0
END DESCRIPTION:
XS GIS Cut Line= 3
      1996874.98       13520625.       1995950.8     13520504.54
      1991279.82     13519991.23
#Sta/Elev= 30
    4068  524.83    4147  523.24  4260.5  501.53  4423.5  491.12  4442.8  487.46
  4478.9     494  4620.1     495  4710.9  491.67  4727.1  494.33  4791.6  494.73
  4803.6  494.13  4816.8  489.07  4840.6  494.53  4922.7  494.51  4978.1  493.21
  4983.2  491.98  4989.7  483.44  4997.5  481.74    5027  483.44  5028.5  491.03
  5033.5  492.44    5067  493.93  5271.4  499.85  5868.5  502.45  6899.7  499.73
  8612.1  503.39  8887.8  507.15  9248.7  517.12    9434  516.56  9699.1  520.75
#Mann= 5 ,-1 , 0
    4068      .1       0  4442.8     .16       0  4989.7     .07       0
    5027     .16       0    5067      .1       0
Bank Sta=4989.7,5027
XS Rating Curve= 0 ,0
Exp/Cntr=0.3,0.1

Type RM Length L Ch R = 1 ,324088  ,1036,1036,1036
BEGIN DESCRIPTION:
San Miguel Creek 156.0
END DESCRIPTION:
XS GIS Cut Line= 3
       1997668.5      13520241.9      1996089.71     13519836.54
      1991324.04     13519314.24
#Sta/Elev= 30
    3370  515.22  3678.7  517.59  3830.5  510.21  4282.9  497.75  4383.6  492.53
  4408.6  489.73  4424.9  492.85  4511.9  493.91  4550.3  488.28  4589.3  492.53
  4623.5   489.4  4674.3  491.69    4784  493.51  4888.7  490.06  4926.6  493.73
    4961  490.73    4963  482.88  4970.8  481.18  5000.3  482.88  5037.4  493.49
  5082.7  493.35  5097.8  488.44  5126.9  493.82  5143.1  490.37  5472.8  498.13
  5931.2  501.32    7767  499.87  8364.6  502.77  8925.6   517.6  9794.2  528.12
#Mann= 8 ,-1 , 0
    3370      .1       0  4282.9     .16       0  4383.6      .1       0
  4550.3     .12       0  4674.3     .16       0    4963     .07       0
  5000.3     .16       0  5126.9      .1       0
Bank Sta=4963,5000.3
XS Rating Curve= 0 ,0
Exp/Cntr=0.3,0.1

Type RM Length L Ch R = 1 ,323052  ,822,822,822
BEGIN DESCRIPTION:
San Miguel Creek 155.0
END DESCRIPTION:
XS GIS Cut Line= 3
      1997900.84     13519858.23       1996250.8     13519074.54
       1991609.6     13518722.84
#Sta/Elev= 30
  3173.3  521.55    3379  520.23  3753.7  509.01  3995.1  498.13    4242  492.48
  4358.6  492.91  4484.8  491.48  4600.5  490.33  4699.2   492.3  4718.9  485.66
  4764.4  491.46  4805.9  491.43  4815.5  489.19  4901.4  492.44  4970.4  491.21
  4977.2  490.01  4978.5  481.15  4986.3  479.45  5015.8  481.15  5018.4   487.1
  5043.4  485.62  5063.5  492.62  5108.6  493.92    5234  491.71  5391.4  496.45
  6649.4  500.37  8097.2  499.84  9239.5  521.37  9552.6   527.1  9654.5  528.19
#Mann= 10 ,-1 , 0
  3173.3      .1       0  4358.6     .16       0  4484.8      .1       0
  4600.5     .16       0  4805.9     .12       0  4901.4     .16       0
  4978.5     .07       0  5015.8     .16       0  9239.5     .05       0
  9552.6      .1       0
Bank Sta=4978.5,5015.8
XS Rating Curve= 0 ,0
Exp/Cntr=0.3,0.1

Type RM Length L Ch R = 1 ,322230  ,1074,1074,1074
BEGIN DESCRIPTION:
San Miguel Creek 154.0
END DESCRIPTION:
XS GIS Cut Line= 3
      1998494.63     13519097.83       1996540.8     13518464.54
      1991820.07     13518173.33
#Sta/Elev= 30
  2946.1  526.18  3845.8  510.36  4422.1  493.09    4528  489.53  4540.9  486.53
  4567.2  490.54    4583   485.9  4614.5  490.62  4657.1     491  4782.7  490.75
  4814.2  487.53  4869.1  492.13    4949   492.4  4967.7   489.8  4974.3  480.67
  4982.1  478.97  5011.6  480.67  5013.3  490.27  5018.3   491.1  5048.4  488.21
  5074.8  491.54  5138.6  491.85  5238.8  493.18    5389  490.15  5803.4   494.6
  6476.1  495.77  6781.7  498.95  7886.1  500.39  8705.3  506.44  9729.7  531.12
#Mann= 8 ,-1 , 0
  2946.1      .1       0  4422.1     .12       0  4657.1     .16       0
    4949     .12       0  4974.3     .07       0  5011.6     .12       0
  5138.6      .1       0  7886.1     .05       0
Bank Sta=4974.3,5011.6
XS Rating Curve= 0 ,0
Exp/Cntr=0.3,0.1

Type RM Length L Ch R = 1 ,321156  ,2159,2159,2159
BEGIN DESCRIPTION:
San Miguel Creek 153.0
END DESCRIPTION:
XS GIS Cut Line= 3
      1998512.51     13518947.05       1996690.8     13517494.54
      1992086.78     13517615.24
#Sta/Elev= 30
  2670.1  523.45  2783.8  522.92  3712.5  499.24    4125  494.88  4316.5  489.49
  4434.9  488.98  4459.7  483.62  4477.3  488.53  4502.1  487.45  4523.7  489.76
  4576.6  488.32  4699.6  491.04  4887.7  491.11  4968.1  489.37  4972.1  487.12
  4974.3  478.22  4982.1  476.52  5011.6  478.22  5013.3  489.39  5024.3  490.96
  5123.3  490.42  5168.4  487.21  5188.4   489.3  5319.6  491.45  5388.4  488.02
  5516.5  493.23  5813.6  496.08  6233.7  492.95  8644.7  503.94  9605.6  520.37
#Mann= 9 ,-1 , 0
  2670.1      .1       0  4316.5     .12       0  4699.6     .16       0
  4887.7     .12       0  4974.3     .07       0  5011.6     .12       0
  5024.3     .16       0  5319.6      .1       0  5516.5     .05       0
Bank Sta=4974.3,5011.6
XS Rating Curve= 0 ,0
Exp/Cntr=0.3,0.1

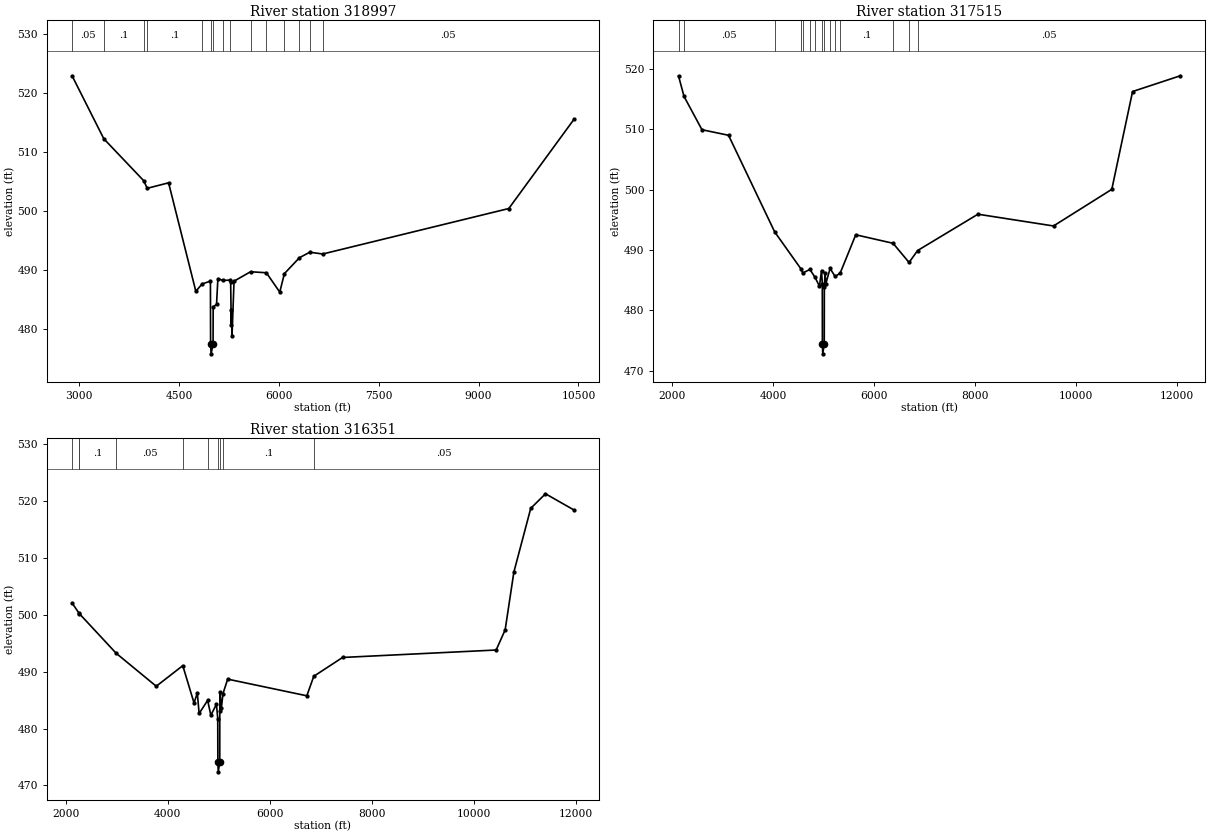
Type RM Length L Ch R = 1 ,318997  ,1482,1482,1482
BEGIN DESCRIPTION:
San Miguel Creek 152.0
END DESCRIPTION:
XS GIS Cut Line= 3
       1999909.7     13516766.95       1997850.8     13516324.54
      1992474.87     13517092.44
#Sta/Elev= 30
  2894.1  522.97  3370.8  512.29  3968.1   505.2  4023.3  503.89  4343.7  504.82
  4752.8  486.43  4847.4  487.67  4972.1  488.15  4974.5  477.52  4982.3  475.82
  5011.8  477.52  5013.4  483.78  5063.9  484.21  5084.1  488.58  5155.6  488.27
  5266.5  488.32  5276.1  487.94  5284.9  480.71  5287.4  483.33  5296.3  478.81
  5326.6  488.14  5574.4  489.74    5812  489.57  6013.5  486.29  6082.9  489.42
  6308.7  492.12  6463.8  493.05  6658.7  492.75    9453  500.46 10430.5  515.56
#Mann= 15 ,-1 , 0
  2894.1     .05       0  3370.8      .1       0  3968.1     .05       0
  4023.3      .1       0  4847.4     .12       0  4974.5     .07       0
  5011.8     .12       0  5155.6     .16       0  5266.5     .12       0
  5574.4      .1       0    5812     .12       0  6082.9      .1       0
  6308.7     .16       0  6463.8      .1       0  6658.7     .05       0
Bank Sta=4974.5,5011.8
XS Rating Curve= 0 ,0
Exp/Cntr=0.3,0.1

Type RM Length L Ch R = 1 ,317515  ,1164,1164,1164
BEGIN DESCRIPTION:
San Miguel Creek 151.0
END DESCRIPTION:
XS GIS Cut Line= 3
      2000662.24     13515791.89       1997850.8     13515220.06
       1990860.2     13516259.12
#Sta/Elev= 30
    2131  518.85  2239.6  515.46    2595  509.94    3121  509.02  4034.7  493.01
  4562.6  486.79  4588.9  486.19  4732.7  486.79  4832.4   485.5  4921.7     484
  4962.5  486.61  4977.9  484.42  4979.2   474.5    4987   472.8  5016.5   474.5
  5018.5  483.94  5032.4  486.19  5048.8  484.44  5131.7  486.95  5231.6  485.62
  5331.5  486.17  5640.3  492.53    6379  491.12  6696.1  487.94    6865  489.92
  8059.7  495.94    9556  493.99 10710.4  500.06 11121.7  516.27 12067.4  518.88
#Mann= 15 ,-1 , 0
    2131      .1       0  2239.6     .05       0  4034.7      .1       0
  4562.6     .16       0  4588.9      .1       0  4732.7     .16       0
  4832.4     .12       0  4979.2     .07       0  5016.5     .12       0
  5131.7      .1       0  5231.6     .12       0  5331.5      .1       0
    6379     .16       0  6696.1      .1       0    6865     .05       0
Bank Sta=4979.2,5016.5
XS Rating Curve= 0 ,0
Exp/Cntr=0.3,0.1

Type RM Length L Ch R = 1 ,316351  ,970,970,970
BEGIN DESCRIPTION:
San Miguel Creek 150.0
END DESCRIPTION:
XS GIS Cut Line= 3
      2000642.59     13514369.15       1997770.8     13514364.54
      1990909.82     13515555.64
#Sta/Elev= 30
  2128.2  502.07  2255.9   500.4  2272.2  500.19  2992.5  493.24  3778.3  487.44
  4298.2  491.06  4518.3  484.51  4583.3  486.24  4618.3  482.65  4785.6  484.95
  4848.3  482.33  4958.3  484.27  4983.3  481.76  4985.6  474.09  4993.4  472.39
    5023  474.09  5023.6   483.1  5028.7  486.34  5054.1  483.57  5086.5  486.15
  5178.3  488.69  6729.3  485.76  6865.8  489.19  7430.3   492.5 10440.4  493.81
 10616.9  497.35 10788.3  507.54 11118.5  518.72 11407.7  521.28 11963.6  518.44
#Mann= 10 ,-1 , 0
  2128.2      .1       0  2255.9     .05       0  2272.2      .1       0
  2992.5     .05       0  4298.2      .1       0  4785.6     .12       0
  4985.6     .07       0    5023     .12       0  5086.5      .1       0
  6865.8     .05       0
Bank Sta=4985.6,5023
XS Rating Curve= 0 ,0
Exp/Cntr=0.3,0.1