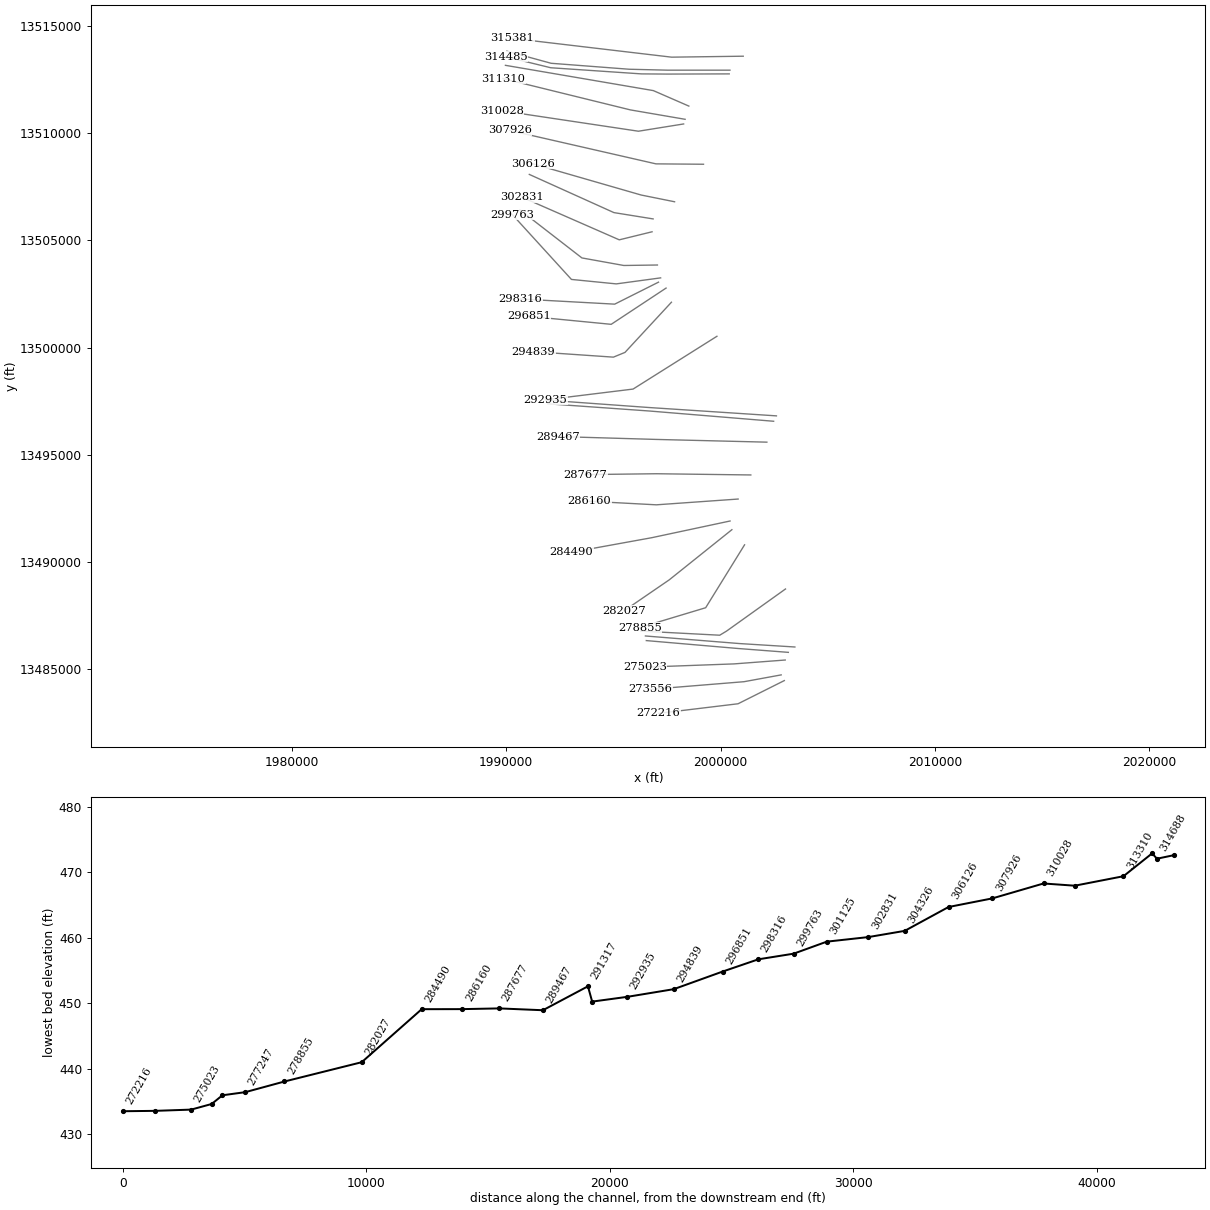
HEC-RAS study San Miguel Creek.prj: San Miguel Creek Base Level Engineering

--- San Miguel Creek.g01 (geometry) --- (continued)

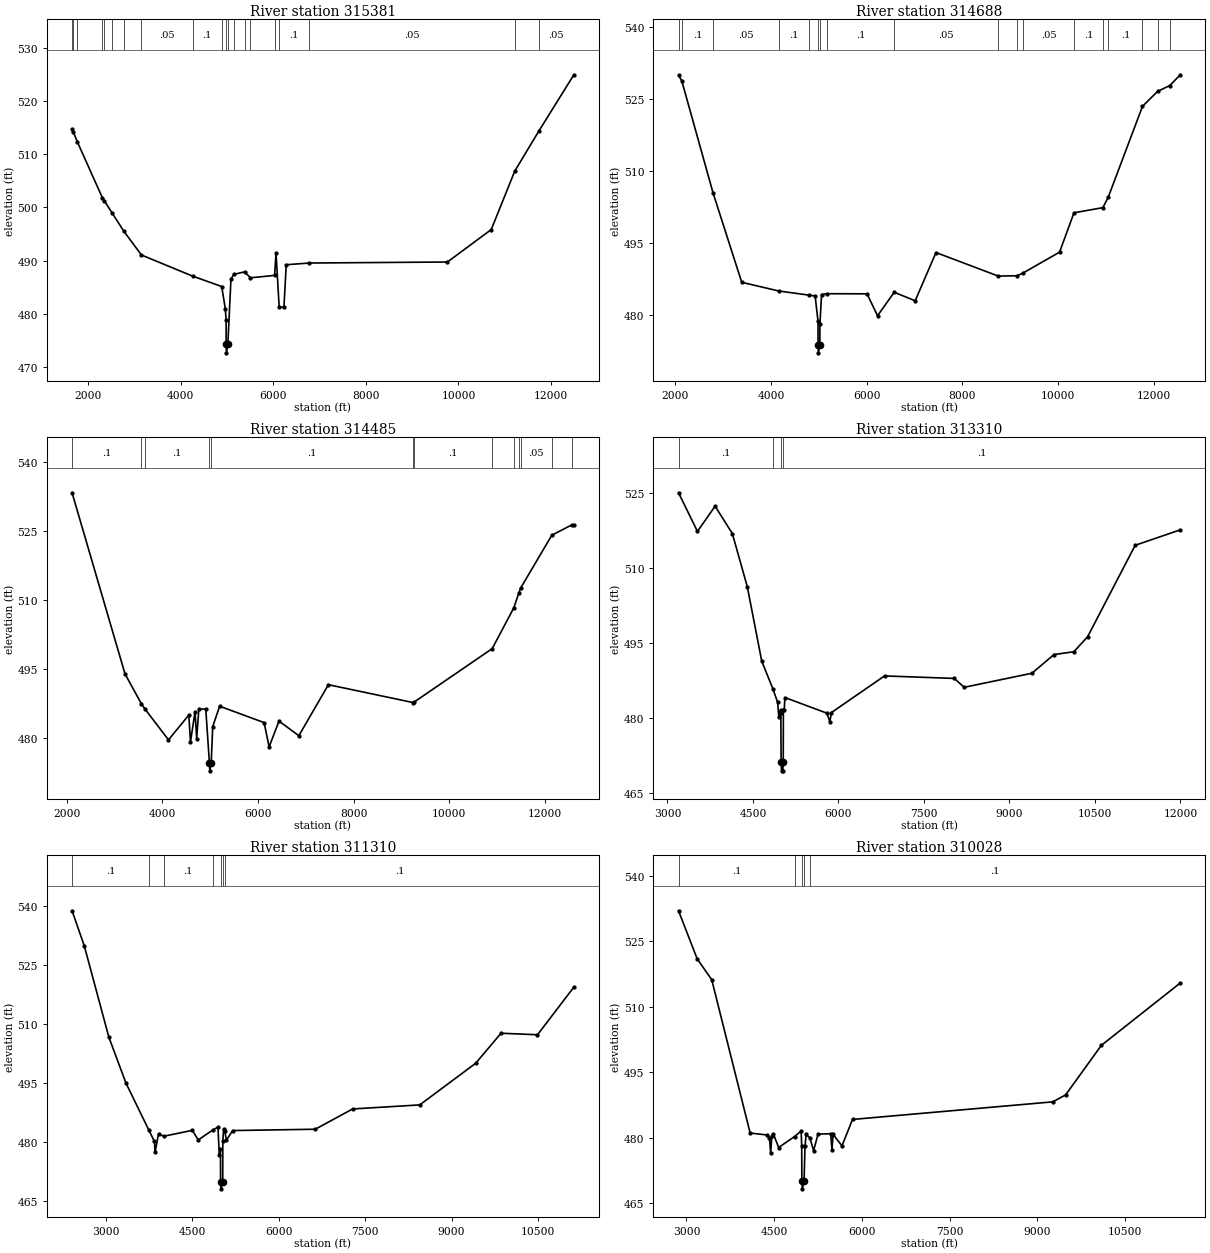
Type RM Length L Ch R = 1 ,315381  ,693,693,693
BEGIN DESCRIPTION:
San Miguel Creek 149.0
END DESCRIPTION:
XS GIS Cut Line= 3
       2001052.9     13513589.53       1997710.8     13513544.54
      1990271.57     13514422.87
#Sta/Elev= 30
  1657.6  514.76  1687.3  514.13  1771.6  512.34  2312.6  501.81  2357.5   501.2
  2524.5  498.93  2774.7  495.52  3155.4  491.05  4261.5  487.07    4888  485.12
  4965.7  480.95  4983.3  478.88  4983.7  474.34  4991.5  472.64  5021.1  474.34
  5087.8   486.5  5151.4  487.41  5382.3  487.88  5509.7  486.76  6029.7  487.21
  6060.6  491.41  6129.1  481.24  6231.8  481.25  6281.4  489.22  6781.1  489.54
  9761.1  489.73 10707.7  495.84 11215.1  506.84 11729.5  514.29 12490.9  524.96
#Mann= 20 ,-1 , 0
  1657.6      .1       0  1687.3     .05       0  1771.6      .1       0
  2312.6     .05       0  2357.5      .1       0  2524.5     .05       0
  2774.7      .1       0  3155.4     .05       0  4261.5      .1       0
    4888     .12       0  4983.7     .07       0  5021.1     .12       0
  5151.4      .1       0  5382.3     .16       0  5509.7      .1       0
  6029.7     .05       0  6129.1      .1       0  6781.1     .05       0
 11215.1      .1       0 11729.5     .05       0
Bank Sta=4983.7,5021.1
XS Rating Curve= 0 ,0
Exp/Cntr=0.3,0.1

Type RM Length L Ch R = 1 ,314688  ,203,203,203
BEGIN DESCRIPTION:
Mapping XS b1ea75a4
END DESCRIPTION:
XS GIS Cut Line= 5
      2000434.09     13512938.14      1997517.43     13512938.14
      1995729.24     13512981.54      1992092.09     13513259.32
      1990026.88     13513824.22
#Sta/Elev= 30
  2066.7  530.01  2134.4  528.86  2786.9  505.53  3388.3  486.82  4159.6  485.01
  4803.2  484.13  4923.3  483.97  4983.4  478.69  4984.6   473.8  4992.4   472.1
    5022   473.8  5023.3  478.03  5057.9  484.27  5175.9  484.44  6008.6  484.41
  6228.7  479.84  6577.3  484.74  7015.7  482.96  7450.8  493.03  8752.1  488.12
  9147.5  488.18  9270.6  488.75 10035.3  493.11 10336.6  501.32 10942.2   502.4
 11056.1  504.65 11769.8  523.54 12086.3  526.66   12338  527.86 12560.9  530.12
#Mann= 18 ,-1 , 0
  2066.7     .05       0  2134.4      .1       0  2786.9     .05       0
  4159.6      .1       0  4803.2     .12       0  4984.6     .07       0
    5022     .12       0  5175.9      .1       0  6577.3     .05       0
  8752.1      .1       0  9147.5     .08       0  9270.6     .05       0
 10336.6      .1       0 10942.2     .05       0 11056.1      .1       0
 11769.8     .05       0 12086.3      .1       0   12338     .05       0
Bank Sta=4984.6,5022
XS Rating Curve= 0 ,0
Exp/Cntr=0.3,0.1

Type RM Length L Ch R = 1 ,314485  ,1175,1175,1175
BEGIN DESCRIPTION:
Mapping XS 4429326d
END DESCRIPTION:
XS GIS Cut Line= 5
      2000399.42     13512764.53      1997517.43     13512755.85
      1996302.16     13512764.53      1992074.72     13513050.99
      1989974.86     13513563.79
#Sta/Elev= 30
    2110  533.37  3216.9     494  3557.6  487.54  3629.7  486.42  4126.9  479.65
  4551.9  485.04  4586.9  479.21  4681.9  485.75  4716.9  479.94  4761.9  486.39
  4906.9   486.3  4983.2  474.61  4991.1  472.91  5020.6  474.61  5051.9  482.52
  5196.9  486.96    6127   483.4    6232  478.11  6438.1  483.73  6853.4  480.55
  7471.9  491.64  9246.1  487.75  9260.5  487.83 10897.6  499.48 11350.8  508.37
 11452.8  511.51 11494.8  512.68 12144.6  524.14 12565.6   526.4   12606  526.34
#Mann= 13 ,-1 , 0
    2110      .1       0  3557.6     .08       0  3629.7      .1       0
  4983.2     .07       0  5020.6      .1       0  9246.1     .16       0
  9260.5      .1       0 10897.6     .08       0 11350.8     .05       0
 11452.8     .08       0 11494.8     .05       0 12144.6      .1       0
 12565.6     .05       0
Bank Sta=4983.2,5020.6
XS Rating Curve= 0 ,0
Exp/Cntr=0.3,0.1

Type RM Length L Ch R = 1 ,313310  ,2000,2000,2000
BEGIN DESCRIPTION:
San Miguel Creek 147.0
END DESCRIPTION:
XS GIS Cut Line= 3
      1998515.66     13511262.81       1996860.8     13511984.54
      1989961.05     13513163.83
#Sta/Elev= 30
  3194.6  525.11  3526.7  517.37  3835.8  522.43  4138.6  516.95  4400.8  506.31
  4654.5   491.4  4848.2   485.9  4932.7  483.16  4954.5  480.21  4986.6  481.64
  4989.3  480.92  4994.8  471.12  5002.6  469.42  5024.3  469.42  5032.2  471.12
  5034.4  481.68    5049  481.64  5061.9   484.1  5799.7  480.96  5850.5   479.2
  5875.8  481.08  6809.2  488.43    8032  487.93  8207.3  486.15  9396.9  488.97
  9782.5  492.71 10131.7  493.27 10373.5  496.29 11207.5  514.59 11999.8  517.69
#Mann= 4 ,-1 , 0
  3194.6      .1       0  4848.2     .12       0  4994.8     .07       0
  5032.2      .1       0
Bank Sta=4994.8,5032.2
XS Rating Curve= 0 ,0
Exp/Cntr=0.3,0.1

Type RM Length L Ch R = 1 ,311310  ,1282,1282,1282
BEGIN DESCRIPTION:
San Miguel Creek 146.0
END DESCRIPTION:
XS GIS Cut Line= 3
      1998342.06     13510646.48       1995790.8     13511084.54
      1989844.39     13512547.38
#Sta/Elev= 30
  2411.4  538.73    2624  529.78  3050.2  506.56  3347.6  494.86  3746.7  482.85
  3841.6  480.02  3852.4  477.28  3912.6  481.98  4000.3  481.34  4499.5  482.86
  4602.6  480.41    4857  482.98  4944.3  483.66  4967.8  476.59  4988.1   478.1
  4989.8  469.67  4997.7  467.97  5027.2  469.67  5029.1  480.21  5042.9   483.2
    5063  482.68  5090.9  480.35  5199.1   482.8  6633.8  483.14  7282.6   488.3
  8448.1  489.33  9418.5  499.92  9859.7  507.57 10492.3  507.18 11123.7   519.3
#Mann= 7 ,-1 , 0
  2411.4      .1       0  3746.7     .12       0  4000.3      .1       0
    4857     .12       0  4989.8     .07       0  5027.2     .12       0
    5063      .1       0
Bank Sta=4989.8,5027.2
XS Rating Curve= 0 ,0
Exp/Cntr=0.3,0.1

Type RM Length L Ch R = 1 ,310028  ,2102,2102,2102
BEGIN DESCRIPTION:
San Miguel Creek 145.0
END DESCRIPTION:
XS GIS Cut Line= 3
      1998272.64     13510429.46       1996164.2     13510090.59
      1989791.79     13511045.77
#Sta/Elev= 30
  2864.5  531.98  3183.7  520.96  3431.8  516.21  4088.8  481.09  4378.8  480.64
  4419.3     480  4439.6  476.47  4459.9  480.39  4485.2  480.92  4576.3  477.77
  4847.2  480.28  4961.2  481.53  4970.5  478.02  4972.9  470.01  4980.7  468.31
  5010.3  470.01    5027  478.15  5047.2  480.77    5111  479.95  5173.6  477.05
  5249.5  480.84  5466.3  480.93  5487.1   477.3  5507.3  480.77    5659  478.15
  5838.9   484.2  9263.8  488.23  9482.9  489.83   10093  501.16 11443.6  515.46
#Mann= 5 ,-1 , 0
  2864.5      .1       0  4847.2     .12       0  4972.9     .07       0
  5010.3     .12       0    5111      .1       0
Bank Sta=4972.9,5010.3
XS Rating Curve= 0 ,0
Exp/Cntr=0.3,0.1

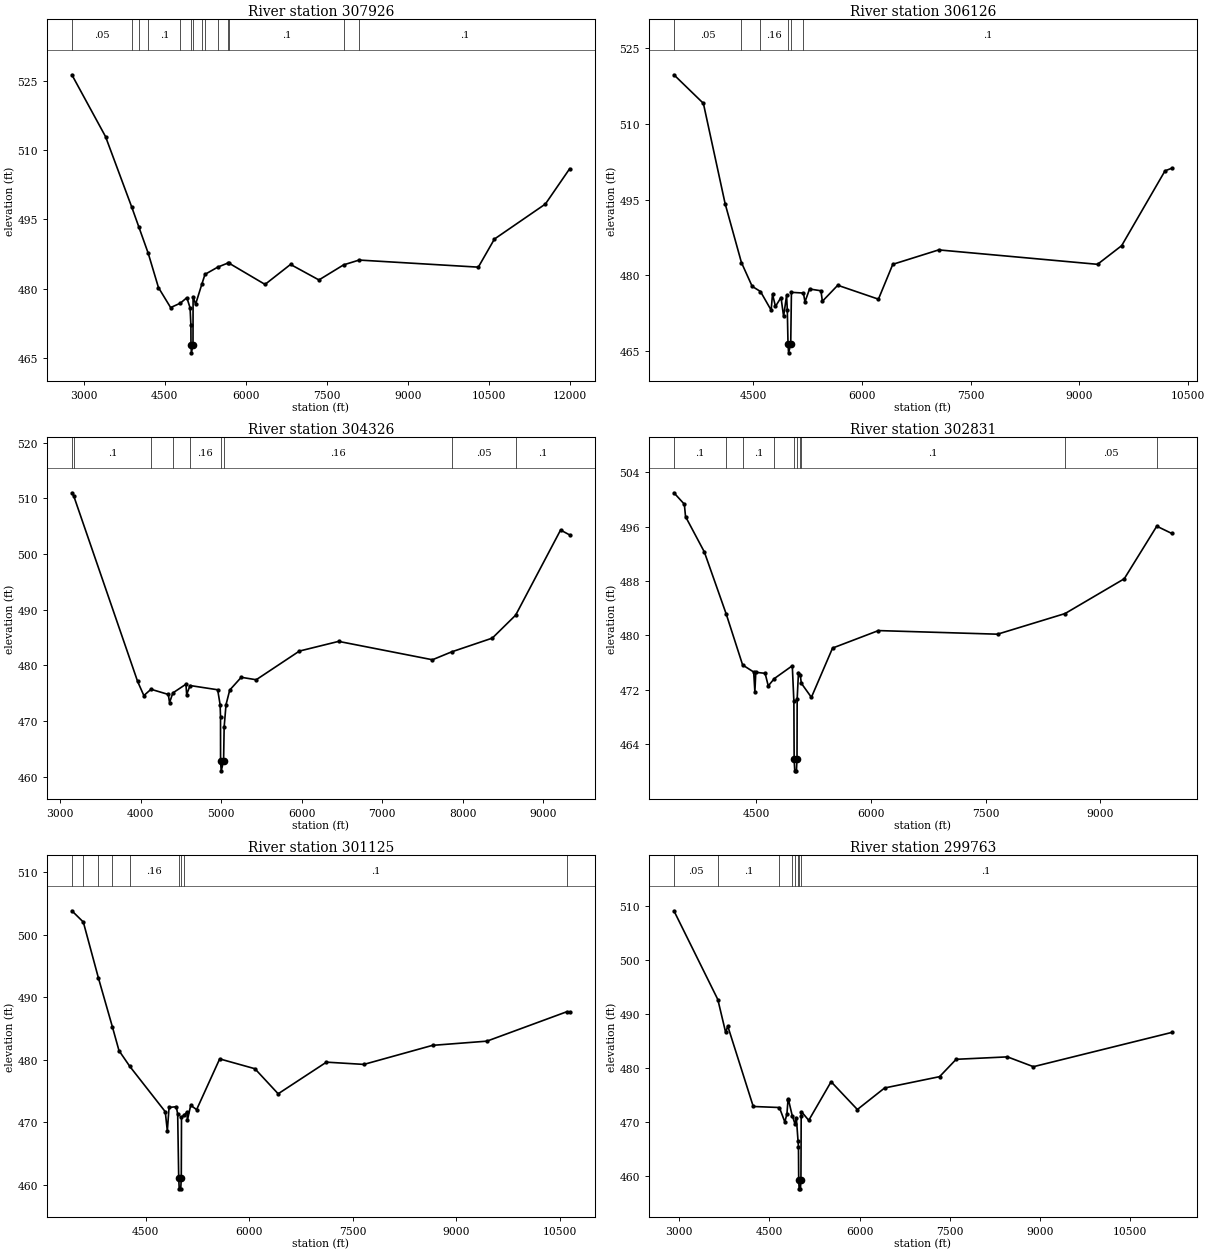
Type RM Length L Ch R = 1 ,307926  ,1800,1800,1800
BEGIN DESCRIPTION:
San Miguel Creek 143.0
END DESCRIPTION:
XS GIS Cut Line= 3
      1999200.03       13508550.       1996980.8     13508567.89
      1990165.04     13510125.63
#Sta/Elev= 30
  2780.7  526.42  3403.5     513    3891  497.61  4019.6  493.38  4194.5  487.62
  4383.3   480.2  4608.3  475.86  4788.2  476.82  4908.3  478.01  4968.3  475.79
  4983.3  472.01  4984.7  467.73  4992.5  466.03  5022.1  467.73  5023.9  478.24
  5070.1  476.59  5184.2  480.88  5243.7  483.07  5479.1  484.64    5678  485.58
  5690.8  485.49  6355.4  480.89    6827  485.23  7352.4  481.86  7809.5  485.14
  8096.8  486.18 10301.6  484.64 10599.5  490.74 11542.8  498.35 11991.5  506.01
#Mann= 14 ,-1 , 0
  2780.7     .05       0    3891      .1       0  4019.6     .05       0
  4194.5      .1       0  4788.2     .12       0  4984.7     .07       0
  5022.1     .12       0  5184.2      .1       0  5243.7     .16       0
  5479.1      .1       0    5678     .16       0  5690.8      .1       0
  7809.5     .16       0  8096.8      .1       0
Bank Sta=4984.7,5022.1
XS Rating Curve= 0 ,0
Exp/Cntr=0.3,0.1

Type RM Length L Ch R = 1 ,306126  ,1800,1800,1800
BEGIN DESCRIPTION:
San Miguel Creek 142.0
END DESCRIPTION:
XS GIS Cut Line= 3
      1997849.99       13506800.       1996290.8     13507114.54
      1991225.02     13508574.99
#Sta/Elev= 30
  3409.4  519.68  3815.7  514.03  4115.3  494.21  4340.3  482.56  4488.2  477.86
  4602.9  476.83  4750.2  473.14  4768.7  476.32  4809.5  473.88    4886  475.65
  4921.8  471.91  4962.6  476.05  4972.8  473.18  4982.5  466.41  4990.4  464.71
  5019.9  466.41  5029.5  476.67    5195  476.53  5216.2  474.78  5279.2  477.33
  5436.4  476.98  5456.2   474.9  5668.2  478.07    6229  475.32  6427.1  482.21
  7060.4  485.06  9249.6  482.21  9582.6   485.9 10180.2  500.69 10272.1   501.2
#Mann= 6 ,-1 , 0
  3409.4     .05       0  4340.3      .1       0  4602.9     .16       0
  4982.5     .07       0  5019.9     .16       0    5195      .1       0
Bank Sta=4982.5,5019.9
XS Rating Curve= 0 ,0
Exp/Cntr=0.3,0.1

Type RM Length L Ch R = 1 ,304326  ,1495,1495,1495
BEGIN DESCRIPTION:
San Miguel Creek 140.0
END DESCRIPTION:
XS GIS Cut Line= 3
      1996850.04     13505999.99       1995020.8     13506294.54
        1991075.       13508075.
#Sta/Elev= 30
  3147.2     511  3169.9  510.45  3963.8  477.11  4041.1  474.58    4130  475.71
    4345  474.78  4360.2  473.31  4401.3  475.05  4563.9  476.62  4572.9  474.77
  4615.1  476.38  4957.8  475.62  4988.1  472.97  4993.2  470.81  4993.9  462.76
  5001.7  461.06  5031.3  462.76  5038.4  468.92  5061.6  472.95  5107.8  475.57
  5250.5  477.86  5436.5  477.42  5972.7  482.57    6460  484.31  7624.9  481.01
  7862.2  482.42  8368.7   484.9  8658.4  489.02  9216.4  504.31  9328.9  503.43
#Mann= 9 ,-1 , 0
  3147.2     .05       0  3169.9      .1       0    4130     .16       0
  4401.3      .1       0  4615.1     .16       0  4993.9     .07       0
  5031.3     .16       0  7862.2     .05       0  8658.4      .1       0
Bank Sta=4993.9,5031.3
XS Rating Curve= 0 ,0
Exp/Cntr=0.3,0.1

Type RM Length L Ch R = 1 ,302831  ,1706,1706,1706
BEGIN DESCRIPTION:
San Miguel Creek 139.0
END DESCRIPTION:
XS GIS Cut Line= 4
      1996799.98       13505400.       1995270.8     13505024.54
       1994092.7     13505540.64      1990754.83      13507002.9
#Sta/Elev= 30
  3425.4  500.97  3561.8  499.29  3577.3  497.47  3822.8  492.28  4109.3  483.14
  4323.3  475.67    4468  474.63  4483.4  471.72  4495.5  474.59  4617.3  474.44
  4658.4  472.59  4737.8  473.67  4972.5  475.55  4993.1  470.31  4996.7  461.81
  5004.6  460.11  5026.3  460.11  5034.1  461.81  5036.1  470.69  5053.2  474.56
  5076.1  474.22  5090.6  472.98    5222  470.91  5498.6  478.15  6097.9  480.72
  7654.5  480.19  8536.7  483.22  9310.2  488.33  9735.4  496.06  9930.3     495
#Mann= 10 ,-1 , 0
  3425.4      .1       0  4109.3     .16       0  4323.3      .1       0
  4737.8     .16       0  4996.7     .07       0  5034.1     .16       0
  5076.1     .12       0  5090.6      .1       0  8536.7     .05       0
  9735.4      .1       0
Bank Sta=4996.7,5034.1
XS Rating Curve= 0 ,0
Exp/Cntr=0.3,0.1

Type RM Length L Ch R = 1 ,301125  ,1362,1362,1362
BEGIN DESCRIPTION:
San Miguel Creek 137.0
END DESCRIPTION:
XS GIS Cut Line= 4
      1997050.03       13503850.      1995482.98     13503827.88
      1993528.14     13504180.17      1990637.54     13506419.73
#Sta/Elev= 30
  3432.8  503.79  3598.7  501.99  3816.5   493.1  4020.4  485.24  4115.4  481.47
  4271.5  478.96  4785.5  471.72  4815.5  468.65  4840.5   472.4  4945.5  472.52
  4965.5  471.33  4980.3  461.11  4988.1  459.41  5009.8  459.41  5017.7  461.11
  5020.8  470.84  5057.2  471.17  5098.1  471.63  5107.2  470.41  5154.2  472.75
  5239.7  472.05  5573.9  480.15  6084.2  478.58    6421  474.58    7120  479.63
  7662.2  479.27  8656.7  482.31  9443.9  482.98 10603.2  487.68   10643  487.66
#Mann= 9 ,-1 , 0
  3432.8     .05       0  3598.7      .1       0  3816.5     .05       0
  4020.4      .1       0  4271.5     .16       0  4980.3     .07       0
  5017.7     .16       0  5057.2      .1       0 10603.2     .05       0
Bank Sta=4980.3,5017.7
XS Rating Curve= 0 ,0
Exp/Cntr=0.3,0.1

Type RM Length L Ch R = 1 ,299763  ,1447,1447,1447
BEGIN DESCRIPTION:
San Miguel Creek 136.0
END DESCRIPTION:
XS GIS Cut Line= 4
      1997199.99       13503250.      1995130.62     13502969.49
      1993039.42     13503177.56       1990285.1     13506198.38
#Sta/Elev= 30
  2911.7  509.13  3642.1  492.67    3772  486.58  3807.4  487.74  4231.1  472.84
  4665.8  472.65  4755.9  469.98  4791.2  471.45  4809.5  474.14  4816.5  474.11
  4878.8  471.16  4926.2  469.58  4947.6  470.78  4975.5  466.49    4983  465.42
  4986.7  459.27  4994.5  457.57  5016.2  457.57  5024.1  459.27  5028.3  471.15
  5033.3  471.87  5153.9  470.27  5525.7  477.43  5962.5  472.28  6415.1  476.27
  7329.4  478.37  7605.4  481.59  8458.4  482.04  8890.1  480.22 11189.5  486.57
#Mann= 8 ,-1 , 0
  2911.7     .05       0  3642.1      .1       0  4665.8     .16       0
  4878.8      .1       0  4926.2     .16       0  4975.5      .1       0
  4986.7     .07       0  5024.1      .1       0
Bank Sta=4986.7,5024.1
XS Rating Curve= 0 ,0
Exp/Cntr=0.3,0.1

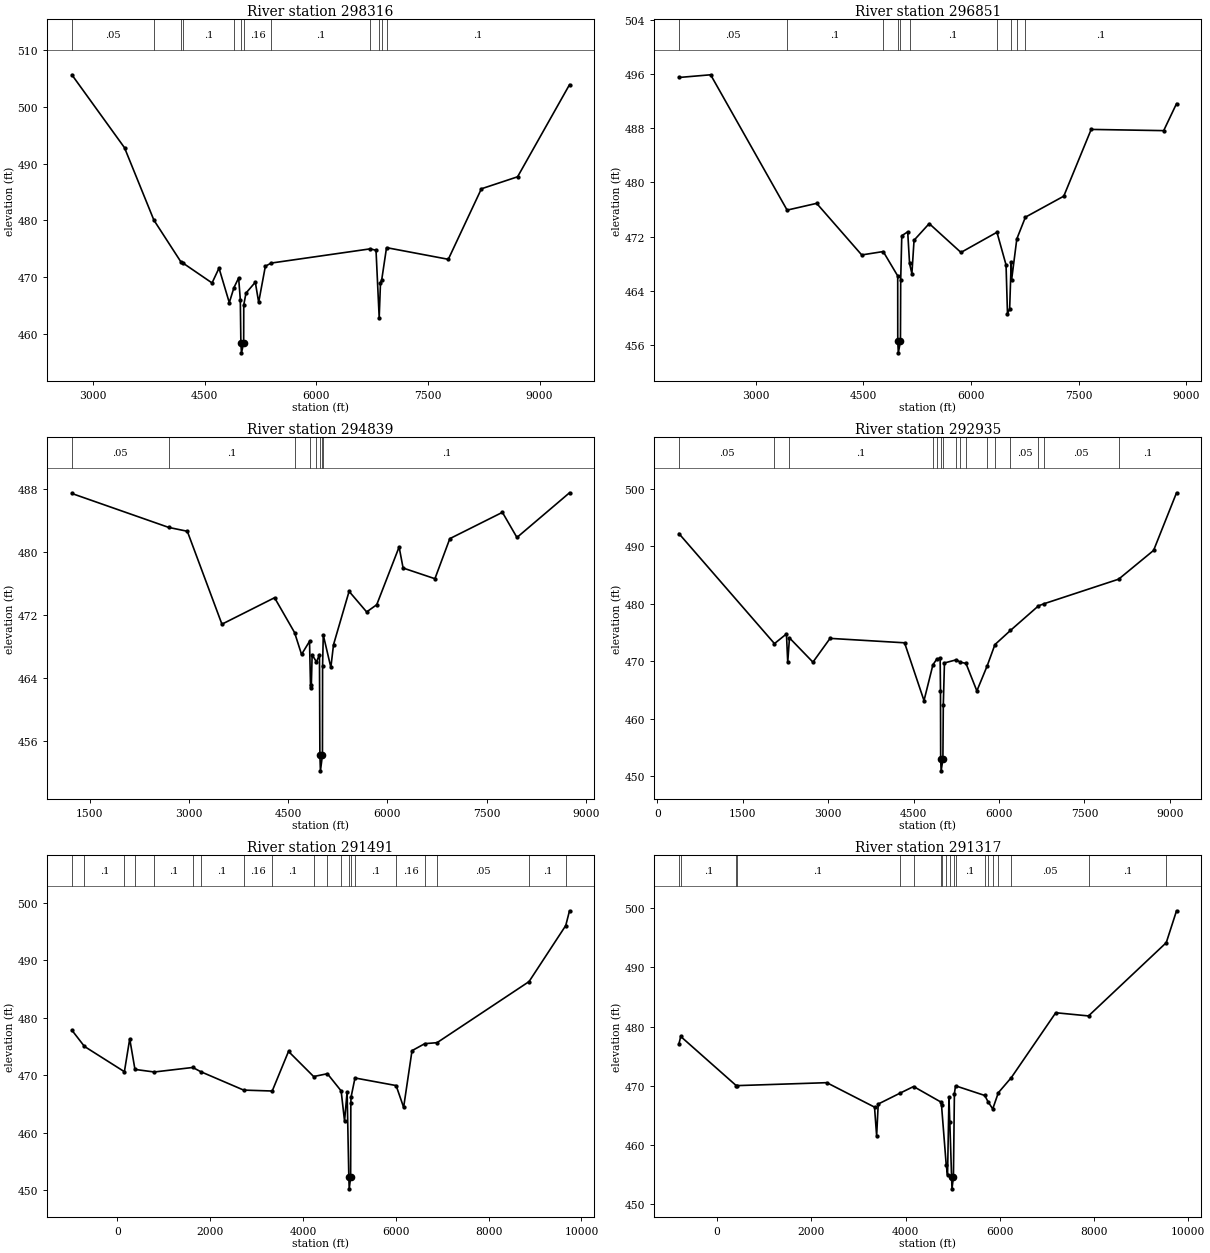
Type RM Length L Ch R = 1 ,298316  ,1465,1465,1465
BEGIN DESCRIPTION:
San Miguel Creek 135.0
END DESCRIPTION:
XS GIS Cut Line= 3
      1997099.96     13503049.98      1995057.33     13502024.49
      1990660.77     13502264.44
#Sta/Elev= 30
  2714.4  505.61  3422.1  492.78  3816.9  480.05  4177.3  472.76  4205.2  472.52
  4598.7     469  4692.1  471.61  4830.4  465.54  4893.7   468.2  4956.1  469.88
  4978.4  466.07  4986.1  458.41    4994  456.71  5023.6  458.41  5024.9  465.15
  5054.9  467.22  5180.1  469.13  5225.2   465.6  5315.3  471.95  5394.8   472.5
  6725.8     475  6802.5  474.74  6845.1  462.91  6862.6  469.04  6878.6  469.51
  6943.7  475.21    7774  473.16  8218.8  485.56  8705.3  487.67  9403.1  503.87
#Mann= 12 ,-1 , 0
  2714.4     .05       0  3816.9      .1       0  4177.3     .16       0
  4205.2      .1       0  4893.7     .16       0  4986.1     .07       0
  5023.6     .16       0  5394.8      .1       0  6725.8     .16       0
  6845.1      .1       0  6878.6     .16       0  6943.7      .1       0
Bank Sta=4986.1,5023.6
XS Rating Curve= 0 ,0
Exp/Cntr=0.3,0.1

Type RM Length L Ch R = 1 ,296851  ,2012,2012,2012
BEGIN DESCRIPTION:
San Miguel Creek 133.0
END DESCRIPTION:
XS GIS Cut Line= 3
      1997453.58     13502773.78      1994894.14     13501083.52
      1991049.34      13501457.1
#Sta/Elev= 30
  1932.8  495.51  2374.8  495.91    3440  475.92  3851.3  476.92  4478.9   469.3
  4778.2   469.8  4980.1   466.2  4980.7  456.54  4988.6  454.84  5018.2  456.54
  5021.7  465.62  5036.8  472.14  5119.2  472.71  5145.1  468.04  5177.5  466.53
  5207.6  471.47  5418.6  473.93  5860.7  469.67  6362.1  472.65  6488.6  467.83
  6508.7  460.61  6538.8  461.31  6560.2   468.2  6566.4  465.64  6638.8  471.67
  6758.4  474.88  7292.5  477.98  7674.2  487.84  8683.8  487.66  8862.9  491.65
#Mann= 10 ,-1 , 0
  1932.8     .05       0    3440      .1       0  4778.2     .16       0
  4980.7     .07       0  5018.2     .16       0  5145.1      .1       0
  6362.1     .12       0  6560.2      .1       0  6638.8     .07       0
  6758.4      .1       0
Bank Sta=4980.7,5018.2
XS Rating Curve= 0 ,0
Exp/Cntr=0.3,0.1

Type RM Length L Ch R = 1 ,294839  ,1904,1904,1904
BEGIN DESCRIPTION:
San Miguel Creek 132.0
END DESCRIPTION:
XS GIS Cut Line= 4
      1997703.56     13502114.04       1995536.9     13499773.77
      1994997.28     13499552.67      1991251.26      13499809.3
#Sta/Elev= 30
  1227.6  487.45  2692.5  483.13  2973.9  482.64  3497.5  470.81  4293.5  474.18
  4596.5  469.74  4701.8  466.96  4822.4  468.63    4838  462.68    4850  463.12
    4862  466.92  4927.3     466  4972.7  466.94  4979.1  454.14  4987.3  452.14
  5017.9  454.14  5019.8  465.45  5030.4  469.43  5145.1  465.31  5185.2   468.2
  5420.8  474.99  5686.4  472.37    5839  473.29  6177.5  480.64  6237.7  477.96
    6719   476.6  6944.3   481.7  7739.7  485.05  7959.7  481.85  8754.8  487.54
#Mann= 8 ,-1 , 0
  1227.6     .05       0  2692.5      .1       0  4596.5     .16       0
  4822.4     .12       0  4927.3     .16       0  4979.1     .07       0
  5017.9     .16       0  5030.4      .1       0
Bank Sta=4979.1,5017.9
XS Rating Curve= 0 ,0
Exp/Cntr=0.3,0.1

Type RM Length L Ch R = 1 ,292935  ,1444,1444,1444
BEGIN DESCRIPTION:
San Miguel Creek 130.0
END DESCRIPTION:
XS GIS Cut Line= 3
        1999825.       13500525.      1995914.09     13498063.42
       1991827.7     13497561.53
#Sta/Elev= 30
   378.9  492.19  2057.1  473.07  2267.5  474.75  2290.1  469.84  2320.7  474.06
  2732.6  469.85  3033.4  473.98  4341.6  473.21  4682.9  463.17  4839.5  469.39
    4904  470.33  4966.2  470.56  4972.3  464.91  4975.5  452.97  4983.8  450.97
  5014.5  452.97  5021.8  462.45  5041.9  469.71  5250.6  470.26  5322.1  469.83
  5419.5  469.64  5611.2  464.85  5793.2  469.23  5928.4   472.9  6199.7  475.35
  6693.1  479.63  6791.8     480  8100.1  484.26  8714.3  489.26  9117.1  499.27
#Mann= 16 ,-1 , 0
   378.9     .05       0  2057.1     .16       0  2320.7      .1       0
  4839.5     .16       0    4904     .12       0  4975.5     .07       0
  5014.5     .12       0  5250.6      .1       0  5322.1     .12       0
  5419.5      .1       0  5793.2     .16       0  5928.4      .1       0
  6199.7     .05       0  6693.1     .08       0  6791.8     .05       0
  8100.1      .1       0
Bank Sta=4975.5,5014.5
XS Rating Curve= 0 ,0
Exp/Cntr=0.3,0.1

Type RM Length L Ch R = 1 ,291491  ,174,174,174
BEGIN DESCRIPTION:
Mapping XS 8ca82f3f
END DESCRIPTION:
XS GIS Cut Line= 4
      2002600.97      13496813.6      1996633.13     13497204.54
      1992205.43     13497524.32      1991901.52      13497520.3
#Sta/Elev= 30
  -980.2  477.85  -709.3  475.02   151.8  470.62   266.7  476.34   379.4  471.02
     795  470.57  1626.6  471.36  1792.4  470.64  2722.1  467.42  3337.3  467.26
  3688.3  474.15    4230  469.78  4526.2  470.27  4822.4  467.28  4895.8  462.04
    4951  467.12  4988.2  452.24  4996.5  450.24  5027.2  452.24  5031.1  465.09
  5036.2   466.2  5120.8  469.53  6007.1  468.21  6169.1  464.42  6349.6  474.28
  6624.6   475.5    6889  475.67  8871.7   486.3  9662.4  496.05  9743.6  498.62
#Mann= 20 ,-1 , 0
  -980.2     .05       0  -709.3      .1       0   151.8      .1       0
   379.4     .16       0     795      .1       0  1626.6     .05       0
  1792.4      .1       0  2722.1     .16       0  3337.3      .1       0
    4230     .16       0  4526.2     .16       0  4822.4     .12       0
  4988.2     .07       0  5027.2      .1       0  5120.8      .1       0
  6007.1     .16       0  6624.6      .1       0    6889     .05       0
  8871.7      .1       0  9662.4     .08       0
Bank Sta=4988.2,5027.2
XS Rating Curve= 0 ,0
Exp/Cntr=0.3,0.1

Type RM Length L Ch R = 1 ,291317  ,1850,1850,1850
BEGIN DESCRIPTION:
Mapping XS d8fa5e2c
END DESCRIPTION:
XS GIS Cut Line= 3
       2002470.8     13496561.86      1996679.97     13497039.86
      1991939.17     13497377.02
#Sta/Elev= 30
  -810.2  477.04  -771.5  478.33   407.8  470.02     413  470.02  2329.5  470.52
  3342.2  466.39  3387.3  461.53  3420.9  466.91  3878.9  468.73  4171.6  469.87
  4746.6  467.27    4765  466.67  4863.9  456.65  4892.4   454.9  4922.5   468.1
  4940.7  463.82  4978.3  454.58  4986.5  452.58  5017.3  454.58  5037.9  468.67
  5061.7  469.99  5681.9  468.36  5753.2  467.28    5852  466.09  5970.3  468.82
  6247.1  471.39  7189.1  482.34  7884.8   481.8  9534.9  494.18  9753.1  499.57
#Mann= 19 ,-1 , 0
  -810.2     .05       0  -771.5      .1       0   407.8     .05       0
     413      .1       0  3878.9     .05       0  4171.6      .1       0
  4746.6     .05       0    4765     .08       0  4863.9     .05       0
  4940.7     .07       0  5037.9     .05       0  5061.7      .1       0
  5681.9     .05       0  5753.2     .08       0    5852     .05       0
  5970.3      .1       0  6247.1     .05       0  7884.8      .1       0
  9534.9     .05       0
Bank Sta=4978.3,5017.3
XS Rating Curve= 0 ,0
Exp/Cntr=0.3,0.1

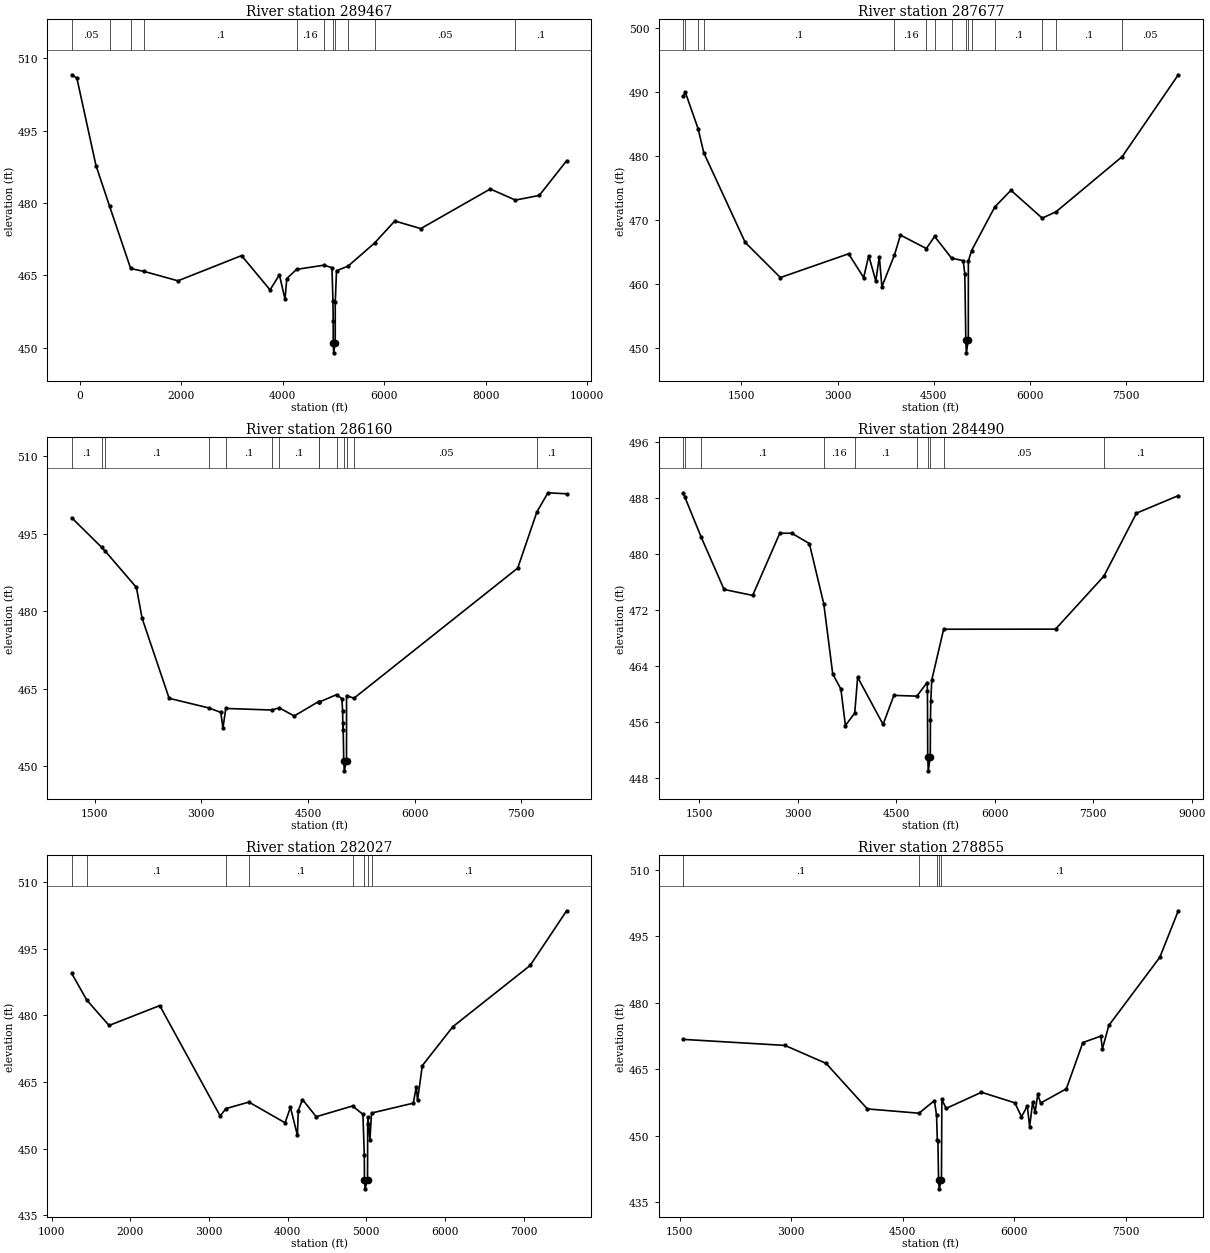
Type RM Length L Ch R = 1 ,289467  ,1790,1790,1790
BEGIN DESCRIPTION:
San Miguel Creek 128.0
END DESCRIPTION:
XS GIS Cut Line= 3
      2002155.43     13495587.47       1997000.8     13495714.54
      1992404.06     13495848.93
#Sta/Elev= 30
  -156.2  506.55   -54.7  505.86   321.9  487.74   588.8  479.35  1005.4   466.4
  1274.3  465.78  1937.4  463.85  3191.5  469.07  3752.9  461.97    3938  465.09
    4048  460.02    4083  464.31  4276.3  466.22  4817.1  467.09  4973.3  466.57
  4993.3  459.57  4997.9  455.62  4998.8  450.92  5007.1  448.92  5037.9  450.92
  5038.3  459.39  5063.3  465.94  5290.6  466.88  5813.6  471.68  6212.4  476.25
    6724  474.67  8093.8  482.88  8590.2  480.58    9060  481.54  9598.7  488.73
#Mann= 11 ,-1 , 0
  -156.2     .05       0   588.8      .1       0  1005.4     .07       0
  1274.3      .1       0  4276.3     .16       0  4817.1     .12       0
  4998.8     .07       0  5037.9     .12       0  5290.6      .1       0
  5813.6     .05       0  8590.2      .1       0
Bank Sta=4998.8,5037.9
XS Rating Curve= 0 ,0
Exp/Cntr=0.3,0.1

Type RM Length L Ch R = 1 ,287677  ,1517,1517,1517
BEGIN DESCRIPTION:
San Miguel Creek 127.0
END DESCRIPTION:
XS GIS Cut Line= 3
      2001406.73     13494057.52       1997000.8     13494114.54
      1993679.35     13494073.85
#Sta/Elev= 30
   593.7  489.33   621.2  489.97   824.2  484.18   911.9  480.44  1559.2  466.44
  2108.1  460.96  3173.1  464.67  3408.2  460.96  3487.9  464.37  3598.2  460.42
  3653.2  464.24  3693.2  459.53  3889.6  464.49  3983.2  467.59  4388.3  465.49
  4516.4  467.38    4781     464  4963.3  463.59  4988.3  461.48  5003.8   451.2
  5012.1   449.2  5042.9   451.2  5043.3  463.53  5093.6  465.17  5455.2  471.97
  5708.4  474.59  6196.6  470.24    6414  471.24  7447.2  479.86  8321.7  492.63
#Mann= 15 ,-1 , 0
   593.7     .05       0   621.2      .1       0   824.2     .05       0
   911.9      .1       0  3889.6     .16       0  4388.3      .1       0
  4516.4     .16       0    4781     .12       0  5003.8     .07       0
  5042.9     .12       0  5093.6     .05       0  5455.2      .1       0
  6196.6     .05       0    6414      .1       0  7447.2     .05       0
Bank Sta=5003.8,5042.9
XS Rating Curve= 0 ,0
Exp/Cntr=0.3,0.1

Type RM Length L Ch R = 1 ,286160  ,1670,1670,1670
BEGIN DESCRIPTION:
San Miguel Creek 126.0
END DESCRIPTION:
XS GIS Cut Line= 3
      2000814.89       13492934.       1997000.8     13492664.54
      1993865.44      13492831.4
#Sta/Elev= 30
  1176.4  498.12    1599  492.37  1648.1  491.65  2086.5  484.62  2166.3  478.67
  2547.2  463.14  3104.3  461.28    3274  460.41  3304.1  457.39  3344.1  461.18
    3989  460.87  4097.1  461.29  4306.6  459.72  4648.9   462.5    4656  462.46
  4661.8  462.43    4903  463.85  4978.2  463.07  4988.3  460.61  4992.1  457.03
  4994.6   458.4  5003.8  451.09  5012.1  449.09  5042.9  451.09  5043.4  463.67
    5147  463.15  7451.8  488.37  7722.3  499.27  7877.4  502.96  8139.8  502.76
#Mann= 15 ,-1 , 0
  1176.4      .1       0    1599     .05       0  1648.1      .1       0
  3104.3     .16       0  3344.1      .1       0    3989     .16       0
  4097.1      .1       0  4648.9     .16       0    4656      .1       0
  4661.8     .16       0    4903     .12       0  5003.8     .07       0
  5042.9     .12       0    5147     .05       0  7722.3      .1       0
Bank Sta=5003.8,5042.9
XS Rating Curve= 0 ,0
Exp/Cntr=0.3,0.1

Type RM Length L Ch R = 1 ,284490  ,2463,2463,2463
BEGIN DESCRIPTION:
San Miguel Creek 124.0
END DESCRIPTION:
XS GIS Cut Line= 3
      2000438.32     13491909.66      1996778.27     13491129.35
       1993042.5     13490451.33
#Sta/Elev= 30
  1257.7   488.8  1281.1  488.15  1527.4  482.49  1877.1  474.99  2312.7  474.14
  2725.8  483.02    2909  483.02  3176.3  481.55  3396.3  472.92  3532.6  462.92
  3656.4  460.77  3725.6  455.55  3867.8  457.34  3911.9  462.45  4299.7  455.71
    4464  459.86    4814  459.75  4970.1  461.69  4975.4  460.52  4979.6  451.08
  4987.9  449.08  5018.7  451.08  5021.1  456.41  5026.6  459.11  5041.4  462.06
  5222.2  469.31  6926.3  469.32  7663.6  476.89  8159.7  485.89  8796.8  488.39
#Mann= 10 ,-1 , 0
  1257.7      .1       0  1281.1     .05       0  1527.4      .1       0
  3396.3     .16       0  3867.8      .1       0    4814     .12       0
  4979.6     .07       0  5018.7     .12       0  5222.2     .05       0
  7663.6      .1       0
Bank Sta=4979.6,5018.7
XS Rating Curve= 0 ,0
Exp/Cntr=0.3,0.1

Type RM Length L Ch R = 1 ,282027  ,3172,3172,3172
BEGIN DESCRIPTION:
San Miguel Creek 123.0
END DESCRIPTION:
XS GIS Cut Line= 3
      2000523.09      13491504.2       1997600.8     13489164.54
      1995499.96     13487725.04
#Sta/Elev= 30
  1256.5  489.42  1447.3  483.43  1731.2  477.71  2375.1  482.18  3143.4  457.35
  3216.2  459.01  3508.2  460.48  3968.5  455.82  4036.6  459.31  4125.4  452.97
  4135.8  458.55  4189.4  461.06  4363.7  457.19  4825.8   459.6  4957.7  457.72
  4975.3  448.63  4977.4  442.97  4985.7  440.97  5016.5  442.97    5018  455.52
  5022.2  457.14  5046.4  451.95  5067.5  458.01  5597.8  460.24  5636.7  463.95
  5651.6  460.88  5712.9  468.68  6101.1  477.44    7083   491.2  7546.7   503.5
#Mann= 8 ,-1 , 0
  1256.5     .05       0  1447.3      .1       0  3216.2     .16       0
  3508.2      .1       0  4825.8     .12       0  4977.4     .07       0
  5016.5     .12       0  5067.5      .1       0
Bank Sta=4977.4,5016.5
XS Rating Curve= 0 ,0
Exp/Cntr=0.3,0.1

Type RM Length L Ch R = 1 ,278855  ,1608,1608,1608
BEGIN DESCRIPTION:
San Miguel Creek 122.0
END DESCRIPTION:
XS GIS Cut Line= 3
       2001114.4     13490798.56       1999300.8     13487864.54
      1996234.45     13486941.01
#Sta/Elev= 30
  1550.7  471.73  2915.7  470.37  3467.9  466.32  4022.9  456.05    4716  455.08
  4924.2  457.91  4953.2  454.61  4963.6  449.01  4971.5  448.92  4980.1  440.02
  4988.4  438.02  5019.3  440.02  5024.3  458.18  5081.8  456.16    5557   459.8
  6006.3  457.42  6094.8  454.26  6173.1  456.72  6204.5  452.06  6245.2  457.56
  6277.6  455.32  6313.8  459.32    6352  457.37  6697.7  460.58  6919.9  471.02
  7160.1  472.46  7183.3  469.62  7268.4  474.87  7953.8  490.24  8202.4  500.74
#Mann= 5 ,-1 , 0
  1550.7      .1       0    4716     .16       0  4963.6      .1       0
  4980.1     .07       0  5019.3      .1       0
Bank Sta=4980.1,5019.3
XS Rating Curve= 0 ,0
Exp/Cntr=0.3,0.1

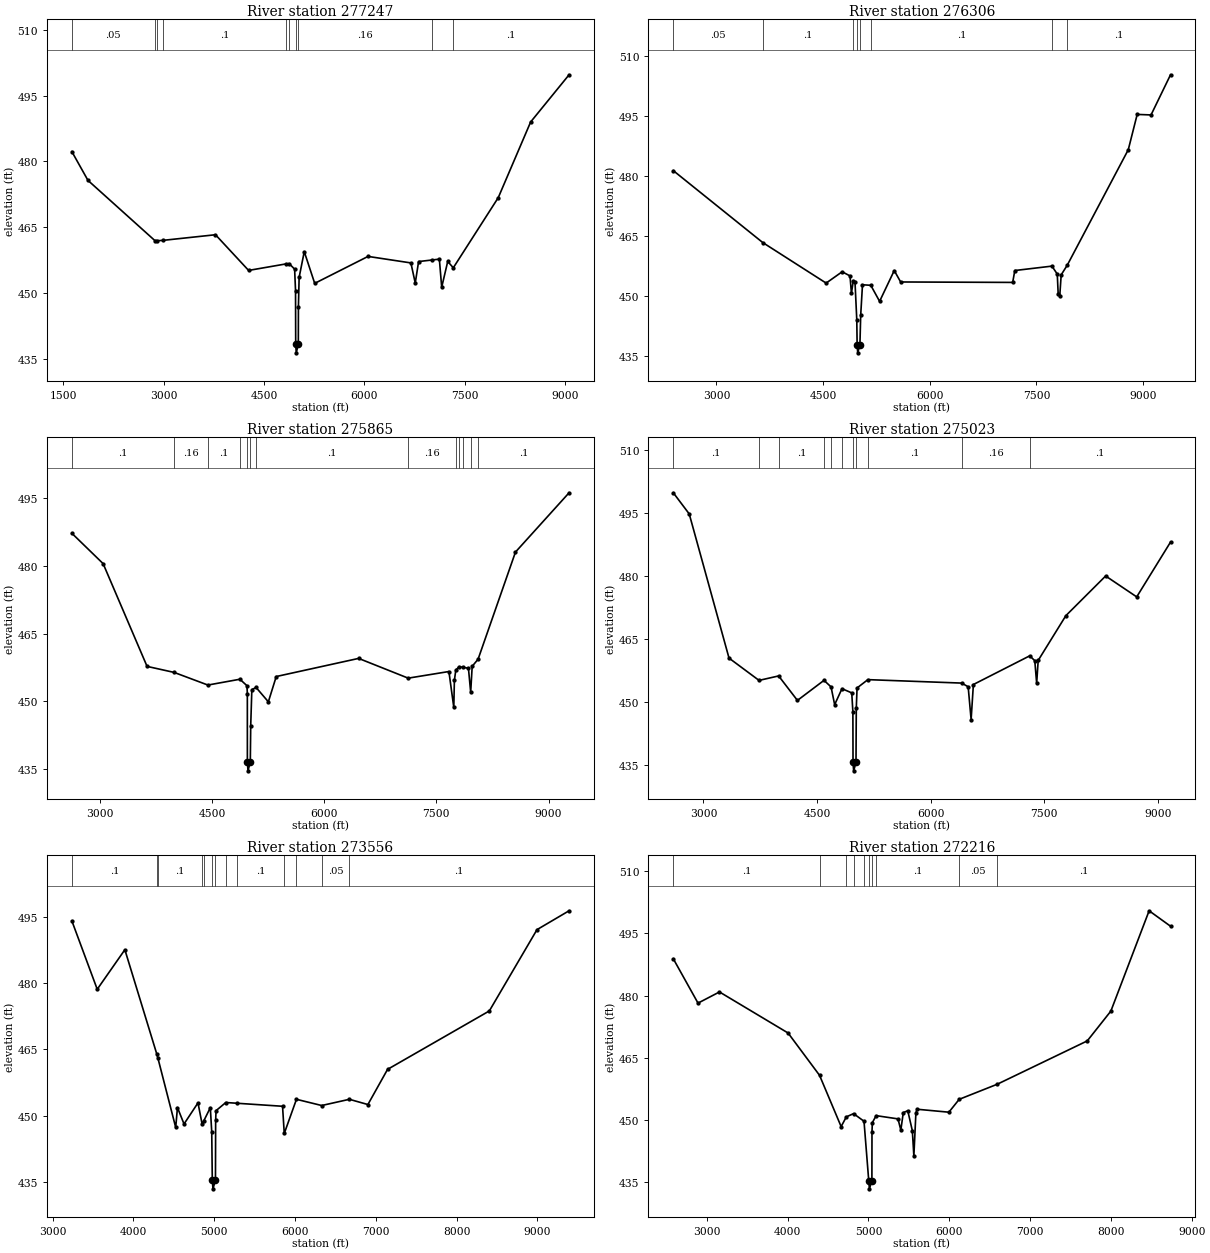
Type RM Length L Ch R = 1 ,277247  ,941,941,941
BEGIN DESCRIPTION:
San Miguel Creek 121.0
END DESCRIPTION:
XS GIS Cut Line= 4
      2003023.78     13488738.65        2000275.       13486775.
      1999956.05     13486582.38      1996275.01       13486775.
#Sta/Elev= 30
  1625.7  482.25  1867.1  475.68  2866.9  461.98  2905.8  461.94  2988.9  462.02
  3774.3   463.3  4269.5  455.17  4835.1  456.67    4876  456.72  4957.7  455.46
  4971.3  450.56  4973.8  438.39  4982.1  436.39    5013  438.39  5014.5  446.88
  5025.2  453.58  5101.8  459.45  5258.1  452.22  6055.9  458.36  6696.8  456.88
  6761.9  452.29  6811.9  457.19  7009.3  457.54  7122.4  457.74  7157.4  451.34
  7247.5  457.21  7330.9  455.77  8003.6  471.76  8487.6  488.99  9062.5  499.75
#Mann= 10 ,-1 , 0
  1625.7     .05       0  2866.9      .1       0  2905.8     .05       0
  2988.9      .1       0  4835.1     .16       0    4876     .07       0
  4973.8     .07       0    5013     .16       0  7009.3     .16       0
  7330.9      .1       0
Bank Sta=4973.8,5013
XS Rating Curve= 0 ,0
Exp/Cntr=0.3,0.1

Type RM Length L Ch R = 1 ,276306  ,441,441,441
BEGIN DESCRIPTION:
Mapping XS 0433c93a
END DESCRIPTION:
XS GIS Cut Line= 3
      2003462.49     13486033.01       2000860.8     13486194.54
      1996490.28     13486546.89
#Sta/Elev= 30
  2393.3  481.42  3650.8  463.46  4542.4  453.33  4767.9  456.16  4878.1  455.12
  4898.1  450.76  4924.7  453.96  4948.2  453.66  4973.2  444.19  4978.3  437.91
  4986.6  435.91  5017.5  437.91  5028.4   445.3  5053.5  452.91  5170.1  452.78
  5294.2  448.77  5499.9  456.46  5590.2  453.61  7165.3   453.5  7195.4  456.47
  7717.1  457.57  7792.3  455.58  7805.3  450.55  7827.4  450.16  7847.5   455.4
  7931.4  457.76  8790.6  486.64    8916  495.46  9110.7  495.33  9384.7  505.36
#Mann= 8 ,-1 , 0
  2393.3     .05       0  3650.8      .1       0  4924.7     .16       0
  4978.3     .07       0  5017.5     .16       0  5170.1      .1       0
  7717.1     .16       0  7931.4      .1       0
Bank Sta=4978.3,5017.5
XS Rating Curve= 0 ,0
Exp/Cntr=0.3,0.1

Type RM Length L Ch R = 1 ,275865  ,842,842,842
BEGIN DESCRIPTION:
San Miguel Creek 120.0
END DESCRIPTION:
XS GIS Cut Line= 3
      2003156.95     13485783.01       2000790.8     13485964.54
      1996531.99     13486331.61
#Sta/Elev= 30
  2626.9  487.28  3045.1  480.54  3632.6  457.75    3995  456.41  4445.9  453.61
    4874   454.9  4968.2  453.46  4973.2   451.7  4973.7  436.58    4982  434.58
  5012.9  436.58  5018.4  444.62  5033.4  452.59  5089.8  453.08  5254.2  449.89
  5359.6   455.5  6461.1  459.52  7123.8  455.14  7668.2  456.61  7733.4  448.66
  7741.4  454.63    7760  456.91  7804.3  457.69  7860.2  457.53  7929.1  457.34
  7959.2  452.02  7979.3  457.77  8058.1  459.34    8558  483.11  9274.6  496.26
#Mann= 13 ,-1 , 0
  2626.9      .1       0    3995     .16       0  4445.9      .1       0
    4874     .16       0  4973.7     .07       0  5012.9     .16       0
  5089.8      .1       0  7123.8     .16       0    7760      .1       0
  7804.3     .07       0  7860.2     .12       0  7959.2     .07       0
  8058.1      .1       0
Bank Sta=4973.7,5012.9
XS Rating Curve= 0 ,0
Exp/Cntr=0.3,0.1

Type RM Length L Ch R = 1 ,275023  ,1467,1467,1467
BEGIN DESCRIPTION:
Mapping XS ba02bcd6
END DESCRIPTION:
XS GIS Cut Line= 3
      2003011.94     13485425.75       2000620.8     13485244.54
      1996456.38     13485092.42
#Sta/Elev= 30
    2602  499.85  2812.5  494.82  3337.9  460.53  3734.2  455.23  3992.9  456.29
  4241.1  450.47  4591.9  455.24  4685.1  453.68  4732.5  449.46  4829.2  453.26
  4958.2  452.26  4973.2  447.76  4975.2  435.72  4983.5  433.72  5014.4  435.72
  5018.3  448.62  5028.3  453.43  5171.3  455.41  6409.2  454.59  6495.4  453.72
  6534.3   445.9  6564.3  454.25  7308.1  461.07  7374.9  459.92  7399.9  454.54
  7419.9  459.98  7785.2  470.62  8310.5  480.06  8720.8  475.09  9167.2  488.12
#Mann= 11 ,-1 , 0
    2602      .1       0  3734.2     .16       0  3992.9      .1       0
  4591.9     .16       0  4685.1      .1       0  4829.2     .16       0
  4975.2     .07       0  5014.4     .16       0  5171.3      .1       0
  6409.2     .16       0  7308.1      .1       0
Bank Sta=4975.2,5014.4
XS Rating Curve= 0 ,0
Exp/Cntr=0.3,0.1

Type RM Length L Ch R = 1 ,273556  ,1340,1340,1340
BEGIN DESCRIPTION:
San Miguel Creek 119.0
END DESCRIPTION:
XS GIS Cut Line= 3
      2002822.78     13484731.79       2001090.8     13484414.54
      1996714.22     13484057.77
#Sta/Elev= 30
  3239.2  494.03  3553.3  478.58  3895.2  487.51  4290.9  463.92  4302.4  463.16
  4524.3  447.39  4545.9  451.88  4627.2  448.17    4800  452.94  4850.6  448.17
    4871  448.85  4952.5  451.86    4970  446.38    4977  435.53  4985.3  433.53
  5016.2  435.53  5018.4  448.99  5023.4  451.18  5144.2  453.02  5282.2  452.85
  5846.1  452.17  5867.3  446.03  6018.2  453.74  6330.4  452.34  6673.1  453.74
  6902.1  452.56  7145.4   460.5  8404.6  473.69  8994.2  492.04  9391.1   496.3
#Mann= 13 ,-1 , 0
  3239.2      .1       0  4290.9     .16       0  4302.4      .1       0
  4850.6     .16       0    4871     .12       0    4977     .07       0
  5016.2     .12       0  5144.2     .16       0  5282.2      .1       0
  5867.3     .16       0  6018.2      .1       0  6330.4     .05       0
  6673.1      .1       0
Bank Sta=4977,5016.2
XS Rating Curve= 0 ,0
Exp/Cntr=0.3,0.1

Type RM Length L Ch R = 1 ,272216  ,1124,1124,1124
BEGIN DESCRIPTION:
San Miguel Creek 118.0
END DESCRIPTION:
XS GIS Cut Line= 3
      2002969.39      13484466.7      2000811.04      13483385.1
      1997099.62     13482936.81
#Sta/Elev= 30
  2585.8  488.88  2891.8   478.2  3157.2  480.89  4006.3     471  4395.5  460.81
  4662.7  448.46    4727  450.81  4816.5  451.58  4945.7  449.75  5004.1  435.47
  5012.4  433.47  5043.3  435.47  5044.4  447.22  5048.9  449.41  5095.6   451.1
  5366.2  450.32  5401.4  447.62  5431.7  451.83  5487.1  452.28  5543.9  447.46
  5562.6  441.36  5587.8  451.77  5602.9  452.64  5995.7  451.93  6123.6  455.03
  6593.8  458.66  7708.1   469.1  8000.2  476.28  8473.6  500.44  8738.4  496.72
#Mann= 10 ,-1 , 0
  2585.8      .1       0  4395.5     .16       0    4727      .1       0
  4816.5     .16       0  4945.7      .1       0  5004.1     .07       0
  5043.3      .1       0  5095.6      .1       0  6123.6     .05       0
  6593.8      .1       0
Bank Sta=5004.1,5043.3
XS Rating Curve= 0 ,0
Exp/Cntr=0.3,0.1