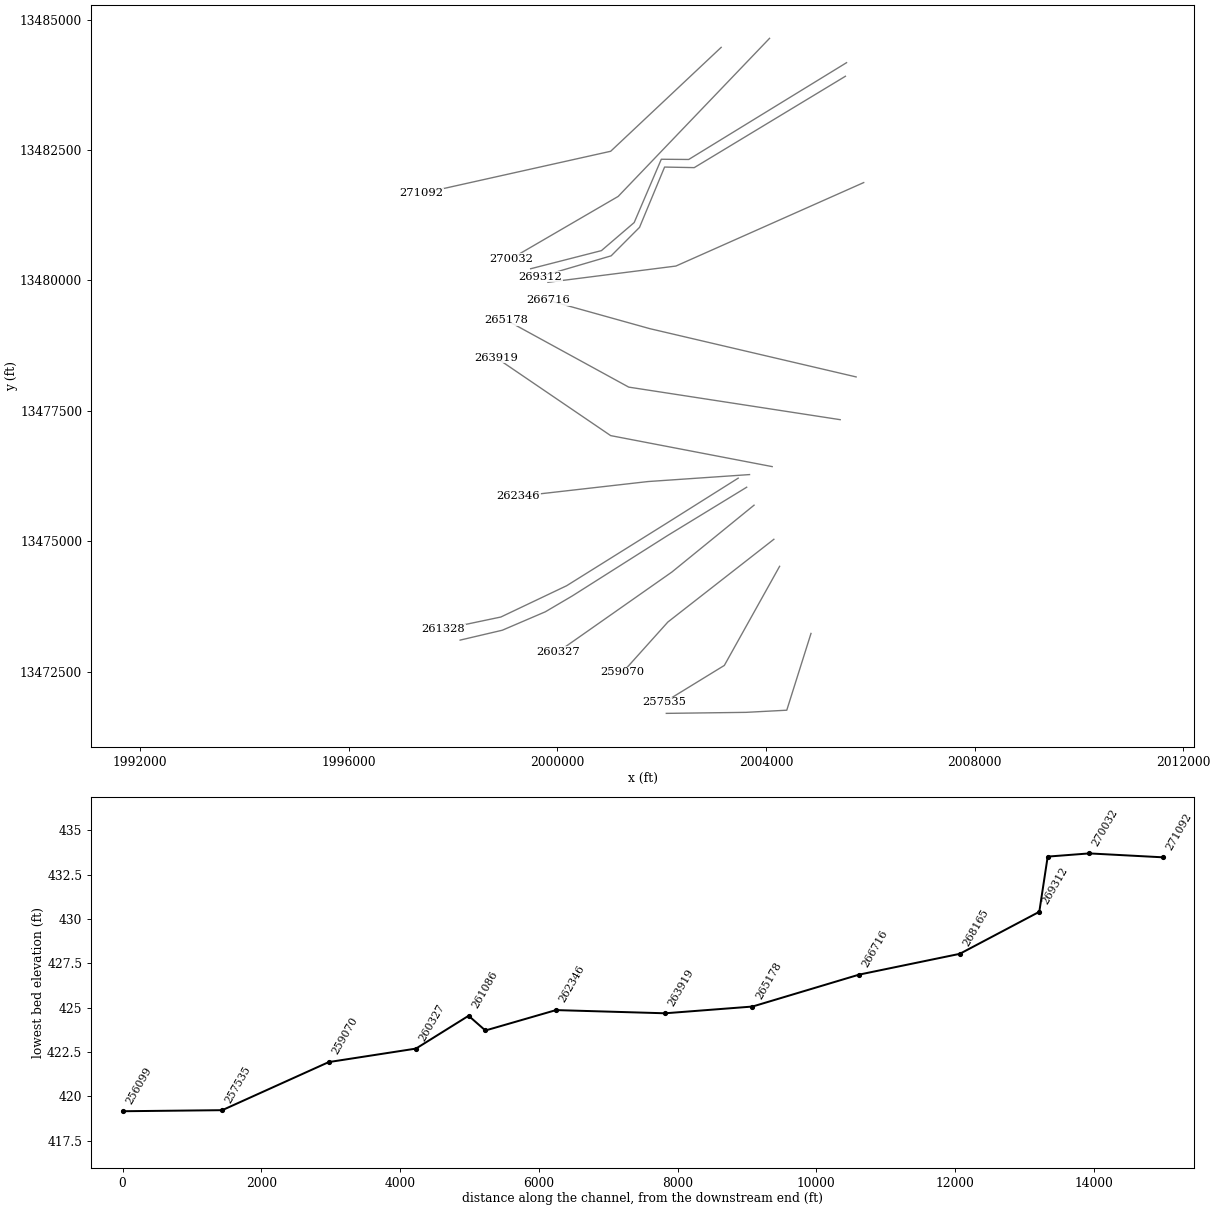
HEC-RAS study San Miguel Creek.prj: San Miguel Creek Base Level Engineering

--- San Miguel Creek.g01 (geometry) --- (continued)

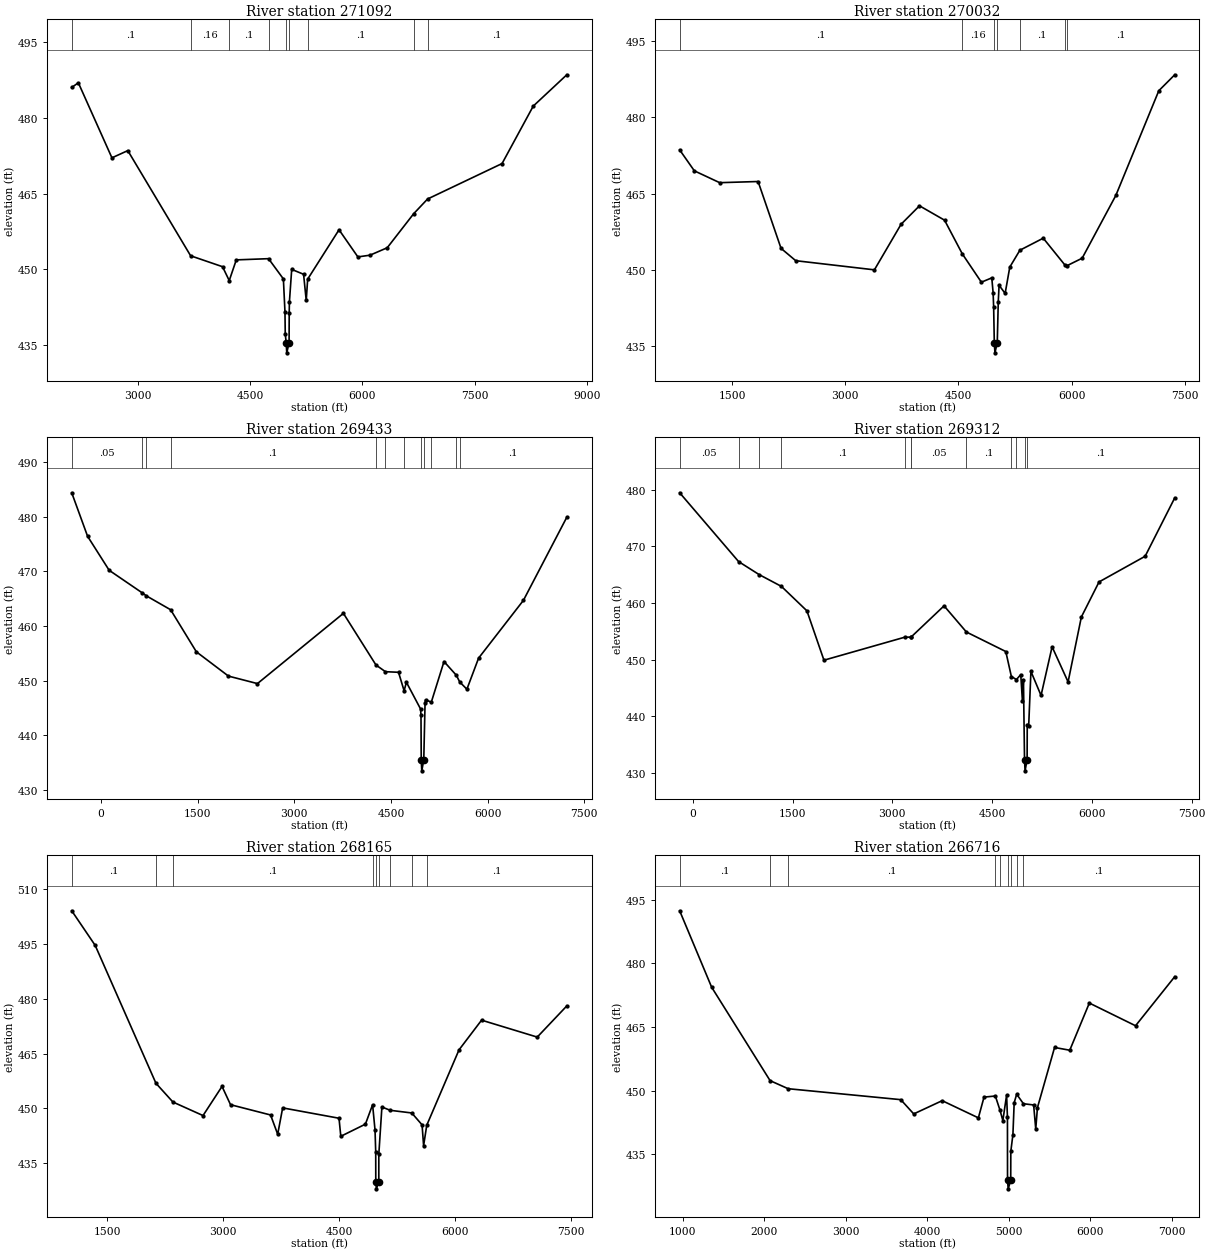
Type RM Length L Ch R = 1 ,271092  ,1060,1060,1060
BEGIN DESCRIPTION:
San Miguel Creek 117.0
END DESCRIPTION:
XS GIS Cut Line= 3
        2003143.      13484466.7        2001025.       13482475.
      1997402.95     13481667.22
#Sta/Elev= 30
  2114.4     486  2202.7  486.93  2651.8  472.07    2864   473.5    3704  452.68
  4130.4  450.52    4220  447.77  4314.3  451.87  4745.5  452.11  4943.9   448.1
  4965.1  441.59  4968.8  437.29  4980.9  435.47  4989.2  433.47  5020.1  435.47
  5021.8  441.31  5024.3  443.51  5055.1  449.99  5213.9  449.02  5249.3  443.85
  5268.6  448.06  5687.8  457.83  5939.7  452.46    6102   452.8  6332.1  454.27
  6686.4  461.02  6871.6  463.92  7867.5  470.94  8284.3  482.31  8732.8  488.51
#Mann= 9 ,-1 , 0
  2114.4      .1       0    3704     .16       0    4220      .1       0
  4745.5     .16       0  4980.9     .07       0  5020.1     .16       0
  5268.6      .1       0  6686.4     .05       0  6871.6      .1       0
Bank Sta=4980.9,5020.1
XS Rating Curve= 0 ,0
Exp/Cntr=0.3,0.1

Type RM Length L Ch R = 1 ,270032  ,599,599,599
BEGIN DESCRIPTION:
San Miguel Creek 116.0
END DESCRIPTION:
XS GIS Cut Line= 3
      2004070.29      13484639.7      2001169.11     13481609.92
      1999122.38      13480418.8
#Sta/Elev= 30
   805.2  473.62   999.7   469.5  1335.6  467.17  1844.9   467.4    2149  454.25
  2343.6  451.82  3386.7  450.02  3740.4  458.99  3984.4  462.62  4316.8  459.79
  4552.1  453.16  4804.8  447.59  4942.7  448.44  4960.5  445.51  4967.5  442.66
  4976.2  435.69  4984.5  433.69  5015.4  435.69  5028.8  443.75  5039.5  446.98
  5119.8  445.38  5181.4  450.56  5315.4  453.88  5624.9  456.25  5909.5  451.02
    5935   450.8  6140.8  452.31    6587  464.65  7156.9  485.26  7368.1   488.4
#Mann= 7 ,-1 , 0
   805.2      .1       0  4552.1     .16       0  4976.2     .07       0
  5015.4     .16       0  5315.4      .1       0  5909.5     .12       0
    5935      .1       0
Bank Sta=4976.2,5015.4
XS Rating Curve= 0 ,0
Exp/Cntr=0.3,0.1

Type RM Length L Ch R = 1 ,269433  ,121,121,121
BEGIN DESCRIPTION:
Mapping XS b2a2119a
END DESCRIPTION:
XS GIS Cut Line= 6
      2005546.03     13484173.16      2002520.56     13482317.76
      2001995.38      13482322.1      2001475.67     13481108.89
      2000847.65     13480570.71      1999491.32     13480223.49
#Sta/Elev= 30
  -454.8  484.41  -208.6  476.44   126.2  470.22   635.6  466.12   705.3  465.53
  1079.8     463  1479.1   455.3  1977.4  450.85  2427.2  449.48    3761  462.34
  4266.6  452.88  4413.1  451.66  4616.5  451.55  4702.8  448.17    4739  449.72
    4958  444.84  4964.9  443.71  4968.9  435.51  4977.2  433.51  5008.1  435.51
    5028  445.87    5035  446.51  5125.3  446.09  5322.1  453.52  5513.3  451.01
  5565.8  449.78  5677.3  448.45  5858.7  454.14  6554.5  464.72  7227.6  479.93
#Mann= 12 ,-1 , 0
  -454.8     .05       0   635.6      .1       0   705.3     .05       0
  1079.8      .1       0  4266.6     .16       0  4413.1      .1       0
  4702.8     .16       0  4968.9     .07       0  5008.1     .16       0
  5125.3      .1       0  5513.3     .07       0  5565.8      .1       0
Bank Sta=4968.9,5008.1
XS Rating Curve= 0 ,0
Exp/Cntr=0.3,0.1

Type RM Length L Ch R = 1 ,269312  ,1147,1147,1147
BEGIN DESCRIPTION:
Mapping XS 575c725f
END DESCRIPTION:
XS GIS Cut Line= 6
      2005524.32     13483912.74      2002626.89     13482161.51
      2002058.32     13482172.36      2001578.04     13481016.44
      2001034.45     13480471.11      1999675.74     13480071.57
#Sta/Elev= 30
  -196.3  479.46   689.6  467.32   997.5  465.03  1333.7  462.94  1716.5  458.63
  1972.6  449.92  3184.5  453.97    3282     454  3282.3     454  3778.1  459.51
  4114.5  454.89  4706.1  451.45    4790  447.04  4866.3  446.51  4931.1  447.38
  4956.4  442.69  4971.7   446.5  4987.6   432.4  4995.9   430.4  5026.8   432.4
  5028.6  438.57  5050.5  438.37  5083.9  447.95    5236   443.7  5402.1  452.29
  5642.6  446.09    5842  457.54  6107.8  463.73    6801  468.26  7245.8  478.56
#Mann= 12 ,-1 , 0
  -196.3     .05       0   689.6      .1       0   997.5     .05       0
  1333.7      .1       0  3184.5     .05       0    3282      .1       0
  3282.3     .05       0  4114.5      .1       0    4790     .16       0
  4866.3      .1       0  4987.6     .07       0  5026.8      .1       0
Bank Sta=4987.6,5026.8
XS Rating Curve= 0 ,0
Exp/Cntr=0.3,0.1

Type RM Length L Ch R = 1 ,268165  ,1449,1449,1449
BEGIN DESCRIPTION:
San Miguel Creek 115.0
END DESCRIPTION:
XS GIS Cut Line= 3
        2005875.       13481875.        2002275.       13480275.
      1999822.72     13479963.67
#Sta/Elev= 30
  1038.4  504.04  1342.1  494.58    2129  456.89  2348.8  451.76  2738.7  448.06
  2984.9  456.03    3095  451.03  3613.5  448.22  3705.8  442.95  3770.1  450.16
  4499.9  447.33  4523.1  442.39  4841.8  445.71  4934.9  451.03  4966.3   444.1
  4975.2  438.16    4976  430.03  4984.3  428.03  5015.2  430.03  5015.4  437.48
  5055.4  450.41  5162.1   449.5    5442  448.77  5575.6  445.52  5595.4  439.83
  5636.3  445.42    6054  466.02  6346.3  474.14  7067.1  469.51  7449.9  478.03
#Mann= 9 ,-1 , 0
  1038.4      .1       0    2129     .05       0  2348.8      .1       0
  4934.9     .12       0    4976     .07       0  5015.2     .12       0
  5162.1      .1       0    5442     .12       0  5636.3      .1       0
Bank Sta=4976,5015.2
XS Rating Curve= 0 ,0
Exp/Cntr=0.3,0.1

Type RM Length L Ch R = 1 ,266716  ,1538,1538,1538
BEGIN DESCRIPTION:
San Miguel Creek 114.0
END DESCRIPTION:
XS GIS Cut Line= 3
      2005729.79     13478149.87        2001775.       13479075.
      1999834.31     13479616.23
#Sta/Elev= 30
   960.3   492.4  1352.9  474.38  2070.2  452.36    2292  450.46  3673.9  447.88
  3833.1  444.52  4182.3  447.64  4626.6  443.59  4695.8  448.48  4834.8  448.74
  4892.3  445.37  4926.9  442.96  4973.1  448.95  4983.3  443.69  4984.3  428.86
  4992.6  426.86  5023.5  428.86  5024.5  435.67  5050.4  439.64    5066  447.17
  5096.6  449.16  5179.4  446.92  5304.8  446.63  5330.7  440.96  5351.5     446
  5561.7  460.18  5748.2  459.53  5988.5  470.65  6555.7   465.3  7036.6  476.87
#Mann= 9 ,-1 , 0
   960.3      .1       0  2070.2     .05       0    2292      .1       0
  4834.8     .16       0  4892.3     .12       0  4984.3     .07       0
  5023.5     .12       0  5096.6     .16       0  5179.4      .1       0
Bank Sta=4984.3,5023.5
XS Rating Curve= 0 ,0
Exp/Cntr=0.3,0.1

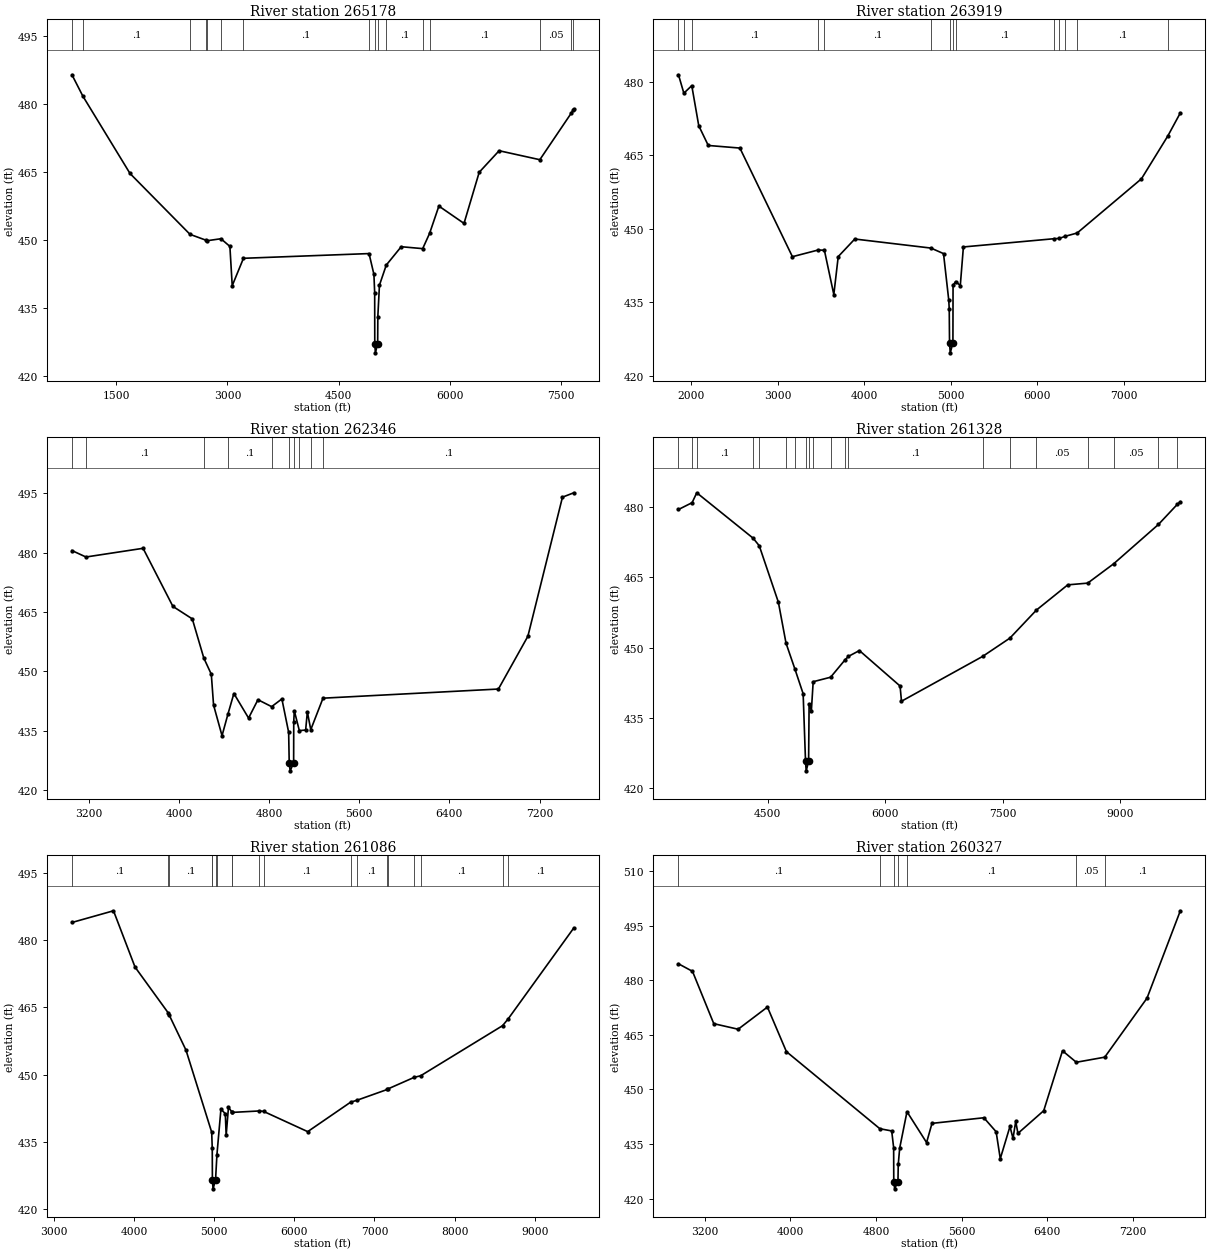
Type RM Length L Ch R = 1 ,265178  ,1259,1259,1259
BEGIN DESCRIPTION:
San Miguel Creek 113.0
END DESCRIPTION:
XS GIS Cut Line= 3
      2005424.23     13477330.43       2001370.8     13477954.54
      1999021.63     13479240.06
#Sta/Elev= 30
   898.8  486.35  1046.6  481.63  1683.4  464.59  2493.5  451.18    2709  449.89
    2727  449.78  2911.3  450.21  3032.3  448.52  3063.9  439.86  3215.6   445.9
  4912.1  446.94    4978  442.35  4988.2  438.27  4989.4  427.06  4997.7  425.06
  5028.6  427.06  5030.8  433.06  5052.6  439.98    5145  444.41  5346.6  448.45
  5636.7  448.03  5729.8  451.38  5855.5  457.41    6195  453.59  6400.2  464.86
  6669.2  469.61    7219  467.63  7644.4  477.91  7669.6  478.57  7677.9  478.75
#Mann= 16 ,-1 , 0
   898.8     .05       0  1046.6      .1       0  2493.5     .07       0
    2709     .12       0    2727      .1       0  2911.3     .16       0
  3215.6      .1       0  4912.1     .12       0  4989.4     .07       0
  5028.6     .12       0    5145      .1       0  5636.7     .05       0
  5729.8      .1       0    7219     .05       0  7644.4      .1       0
  7669.6     .05       0
Bank Sta=4989.4,5028.6
XS Rating Curve= 0 ,0
Exp/Cntr=0.3,0.1

Type RM Length L Ch R = 1 ,263919  ,1573,1573,1573
BEGIN DESCRIPTION:
San Miguel Creek 112.0
END DESCRIPTION:
XS GIS Cut Line= 3
      2004120.66      13476430.9        2001025.       13477025.
       1998835.9     13478514.26
#Sta/Elev= 30
  1853.2  481.48  1915.4  477.72  2006.9  479.26  2087.6  471.07  2197.5  467.04
  2563.1  466.51    3170  444.32  3466.5  445.68  3539.5  445.64  3648.5  436.59
  3699.4  444.34  3890.8  447.93  4770.9  446.08  4916.3  444.95  4976.8  435.45
  4982.4  433.63  4985.7  426.68    4994  424.68  5024.9  426.68  5026.5  438.48
  5056.4  439.25  5110.1  438.43    5146  446.31  6198.5     448  6253.4  448.04
  6317.4  448.46  6461.1  449.16  7203.8  460.23  7507.9  468.96    7653  473.69
#Mann= 14 ,-1 , 0
  1853.2      .1       0  1915.4     .05       0  2006.9      .1       0
  3466.5     .07       0  3539.5      .1       0  4770.9     .12       0
  4985.7     .07       0  5024.9     .12       0  5056.4      .1       0
  6198.5     .16       0  6253.4      .1       0  6317.4     .16       0
  6461.1      .1       0  7507.9     .05       0
Bank Sta=4985.7,5024.9
XS Rating Curve= 0 ,0
Exp/Cntr=0.3,0.1

Type RM Length L Ch R = 1 ,262346  ,1018,1018,1018
BEGIN DESCRIPTION:
San Miguel Creek 111.0
END DESCRIPTION:
XS GIS Cut Line= 3
      2003686.62     13476278.12       2001740.8     13476144.54
      1999252.55     13475861.45
#Sta/Elev= 30
  3049.6  480.52  3173.9  478.89    3681  481.09  3945.8  466.41    4118  463.25
  4220.1  453.36  4286.6  449.27  4306.7  441.48  4381.8  433.74  4435.5  439.32
  4487.1   444.4  4617.4  438.19  4700.7  442.83  4822.2  441.08  4913.1  443.03
  4973.2  434.59  4978.2  426.86  4986.6  424.86  5017.5  426.86  5018.4  437.29
  5023.4  440.04    5068  435.02  5124.1  435.17  5139.2  439.77  5169.5  435.26
  5278.2  443.22  6835.1  445.53  7096.7  458.86  7403.7  494.01  7504.3  495.12
#Mann= 10 ,-1 , 0
  3049.6     .05       0  3173.9      .1       0  4220.1     .16       0
  4435.5      .1       0  4822.2     .12       0  4978.2     .07       0
  5017.5     .12       0    5068      .1       0  5169.5     .12       0
  5278.2      .1       0
Bank Sta=4978.2,5017.5
XS Rating Curve= 0 ,0
Exp/Cntr=0.3,0.1

Type RM Length L Ch R = 1 ,261328  ,242,242,242
BEGIN DESCRIPTION:
Mapping XS 5a40c571
END DESCRIPTION:
XS GIS Cut Line= 5
      2003469.22     13476209.52      2002091.21     13475341.47
      2000181.48      13474147.9      1998920.15     13473547.94
      1997816.02     13473316.18
#Sta/Elev= 30
  3359.1  479.51  3533.2  480.97  3592.5  483.08  4312.2  473.38  4390.1  471.77
  4634.3  459.71  4731.9  450.97  4845.8  445.42  4950.4  440.17  4980.8  425.71
  4989.1  423.71  5020.1  425.71  5026.4     438  5055.3  436.53  5078.5  442.74
  5300.9   443.7  5483.8  447.38  5528.4  448.15  5668.5  449.39  6187.4  441.82
  6205.6  438.57  7241.2  448.14  7589.5  452.05  7928.3  458.04  8327.8  463.42
  8582.4  463.79  8913.9  467.92  9484.9  476.31    9727  480.62  9764.7  481.16
#Mann= 20 ,-1 , 0
  3359.1      .1       0  3533.2     .05       0  3592.5      .1       0
  4312.2     .08       0  4390.1      .1       0  4731.9      .1       0
  4845.8     .12       0  4980.8     .07       0  5020.1     .12       0
  5078.5      .1       0  5300.9      .1       0  5483.8     .05       0
  5528.4      .1       0  7241.2     .05       0  7589.5      .1       0
  7928.3     .05       0  8582.4      .1       0  8913.9     .05       0
  9484.9      .1       0    9727     .05       0
Bank Sta=4980.8,5020.1
XS Rating Curve= 0 ,0
Exp/Cntr=0.3,0.1

Type RM Length L Ch R = 1 ,261086  ,759,759,759
BEGIN DESCRIPTION:
Mapping XS a3dfde03
END DESCRIPTION:
XS GIS Cut Line= 6
      2003631.98      13476035.9      2002117.37     13475110.63
      2000289.99     13473952.59      1999772.69      13473648.1
       1998948.1     13473294.87      1998139.42     13473105.36
#Sta/Elev= 30
  3222.8  483.91  3741.6  486.52  4010.6  473.97  4426.5  463.72  4435.7  463.33
  4646.5  455.47  4967.7  437.16  4974.7  433.58  4976.5  426.54  4984.8  424.54
  5015.8  426.54  5033.1  432.15  5083.1   442.3  5137.8  441.29  5148.4  436.45
  5177.2  442.72  5219.9  441.67  5226.9  441.58  5562.3   441.9  5614.7  441.81
  6166.5  437.29  6703.5  443.87  6777.9  444.26    7160  446.69  7165.9  446.79
    7496  449.39  7576.7  449.74  8599.7  460.91  8671.5  462.47    9489  482.69
#Mann= 19 ,-1 , 0
  3222.8      .1       0  4426.5     .08       0  4435.7      .1       0
  4974.7     .08       0  4976.5     .07       0  5015.8     .08       0
  5033.1      .1       0  5219.9     .08       0  5226.9      .1       0
  5562.3     .08       0  5614.7      .1       0  6703.5     .08       0
  6777.9      .1       0    7160     .08       0  7165.9      .1       0
    7496     .05       0  7576.7      .1       0  8599.7     .05       0
  8671.5      .1       0
Bank Sta=4976.5,5015.8
XS Rating Curve= 0 ,0
Exp/Cntr=0.3,0.1

Type RM Length L Ch R = 1 ,260327  ,1257,1257,1257
BEGIN DESCRIPTION:
Mapping XS 7d642a8c
END DESCRIPTION:
XS GIS Cut Line= 3
      2003773.14     13475691.56      2002199.76     13474411.15
      2000019.38     13472881.63
#Sta/Elev= 30
  2953.1  484.49  3084.2  482.42  3283.1  468.05  3510.8  466.52  3784.8  472.61
  3962.2  460.37  4835.8   439.2  4946.5  438.59  4964.8     434  4965.9  424.69
  4974.2  422.69  5005.2  424.69  5007.8  429.38  5021.3  433.88  5089.5  443.87
  5272.7   435.4  5323.3  440.67  5808.3  442.21  5922.9  438.37  5961.7  430.97
  6052.4  439.83  6080.7  436.52    6106  441.22  6126.9  437.92  6367.9  444.15
  6543.5   460.6  6672.6  457.45  6938.4  458.85  7333.6  475.06    7645  499.05
#Mann= 7 ,-1 , 0
  2953.1      .1       0  4835.8     .16       0  4965.9     .07       0
  5005.2     .16       0  5089.5      .1       0  6672.6     .05       0
  6938.4      .1       0
Bank Sta=4965.9,5005.2
XS Rating Curve= 0 ,0
Exp/Cntr=0.3,0.1

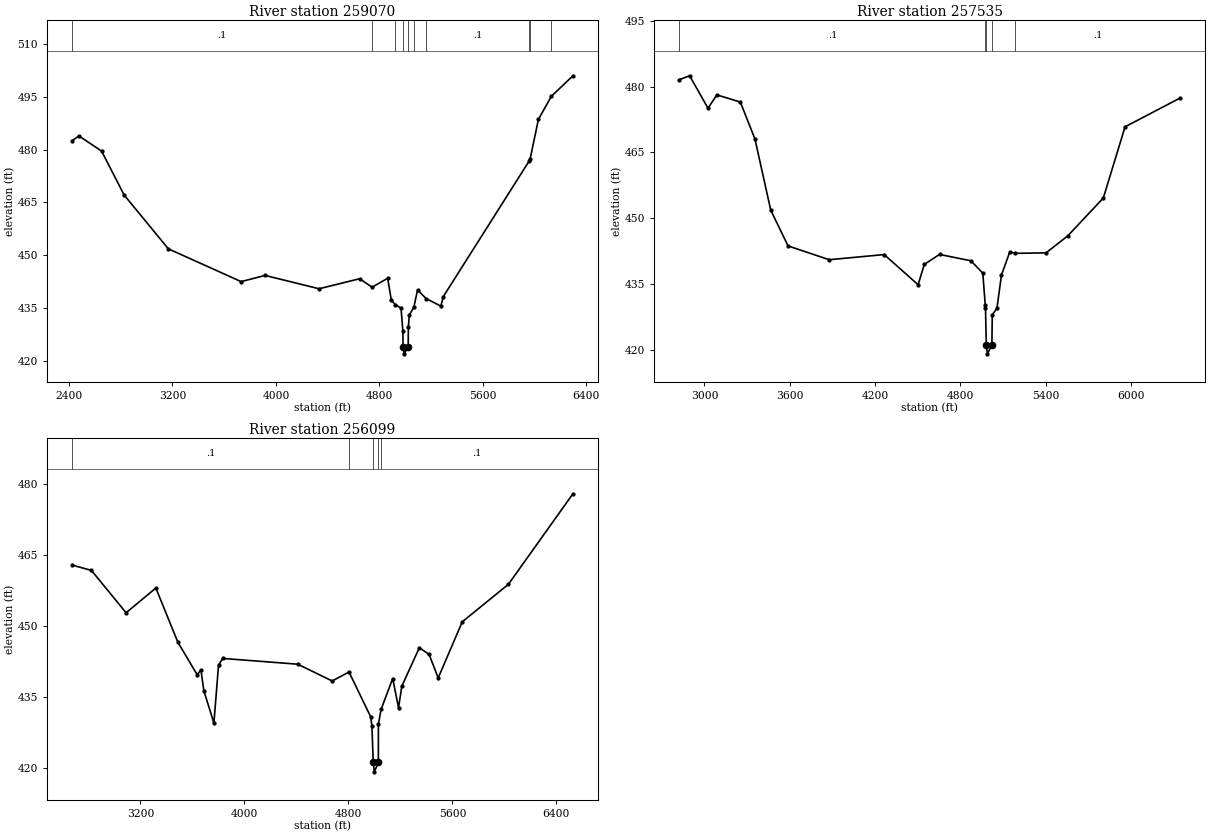
Type RM Length L Ch R = 1 ,259070  ,1535,1535,1535
BEGIN DESCRIPTION:
San Miguel Creek 109.0
END DESCRIPTION:
XS GIS Cut Line= 3
      2004152.86     13475037.67       2002121.8     13473452.37
       2001255.7     13472487.74
#Sta/Elev= 30
  2423.5  482.51  2477.2  483.86  2652.2  479.56  2826.4  467.07  3168.3  451.78
  3730.9  442.46  3916.3  444.22  4333.1  440.43  4646.7  443.27  4743.7  440.89
  4864.2  443.41  4892.3  437.15  4923.9  435.91  4967.4  434.92  4981.4  428.43
  4983.3  423.93  4991.6  421.93  5022.6  423.93  5024.2   429.7  5031.4     433
  5066.1  435.13  5094.9  440.06  5162.7  437.61  5275.4   435.5  5293.4  438.16
  5958.8  476.79  5965.2  477.28  6029.7   488.6  6129.9  495.15  6296.4  500.97
#Mann= 10 ,-1 , 0
  2423.5      .1       0  4743.7     .16       0  4923.9     .12       0
  4983.3     .07       0  5022.6     .12       0  5066.1     .16       0
  5162.7      .1       0  5958.8     .05       0  5965.2      .1       0
  6129.9     .05       0
Bank Sta=4983.3,5022.6
XS Rating Curve= 0 ,0
Exp/Cntr=0.3,0.1

Type RM Length L Ch R = 1 ,257535  ,1436,1436,1436
BEGIN DESCRIPTION:
San Miguel Creek 108.0
END DESCRIPTION:
XS GIS Cut Line= 3
       2004263.1     13474519.86      2003203.62     13472620.12
      2002054.88     13471915.74
#Sta/Elev= 30
  2824.8  481.57  2896.2  482.44  3025.6  475.06  3087.9   478.1    3253  476.46
  3355.9  468.04  3466.7  451.89  3588.4  443.76  3878.1  440.62  4264.5  441.79
  4503.2  434.93  4546.7  439.56  4653.8  441.82  4874.1  440.38  4958.1  437.57
    4975  430.43  4976.9  429.74  4982.6  421.22  4990.9  419.22  5021.9  421.22
  5024.8  428.11  5057.3  429.56  5089.3  437.13  5147.9  442.39  5186.7  442.07
  5402.5  442.18  5555.3  446.03  5805.7  454.65  5958.5  470.84  6347.5  477.41
#Mann= 5 ,-1 , 0
  2824.8      .1       0    4975     .12       0  4982.6     .07       0
  5021.9     .12       0  5186.7      .1       0
Bank Sta=4982.6,5021.9
XS Rating Curve= 0 ,0
Exp/Cntr=0.3,0.1

Type RM Length L Ch R = 1 ,256099  ,1240,1240,1240
BEGIN DESCRIPTION:
San Miguel Creek 107.0
END DESCRIPTION:
XS GIS Cut Line= 4
       2004864.7     13473233.22      2004400.28     13471761.82
      2003618.12      13471720.6      2002091.24     13471701.06
#Sta/Elev= 30
  2673.8   462.9  2823.1  461.77  3089.7  452.81  3318.7  458.04  3488.3  446.56
  3636.5  439.71  3665.5  440.72  3687.6  436.35  3765.1  429.47  3800.8  441.72
  3833.1  443.15  4409.8  441.93  4675.2  438.38  4804.4  440.28  4970.6  430.84
  4980.6  428.87  4990.9  421.16  4999.3  419.16  5030.3  421.16  5030.6  429.23
  5051.1  432.35  5140.6   438.9  5185.6  432.73  5210.6  437.27  5345.6  445.42
  5420.7  443.99  5490.7  439.03  5675.7   450.9  6030.7  458.83    6527  477.98
#Mann= 5 ,-1 , 0
  2673.8      .1       0  4804.4     .12       0  4990.9     .07       0
  5030.3     .12       0  5051.1      .1       0
Bank Sta=4990.9,5030.3
XS Rating Curve= 0 ,0
Exp/Cntr=0.3,0.1