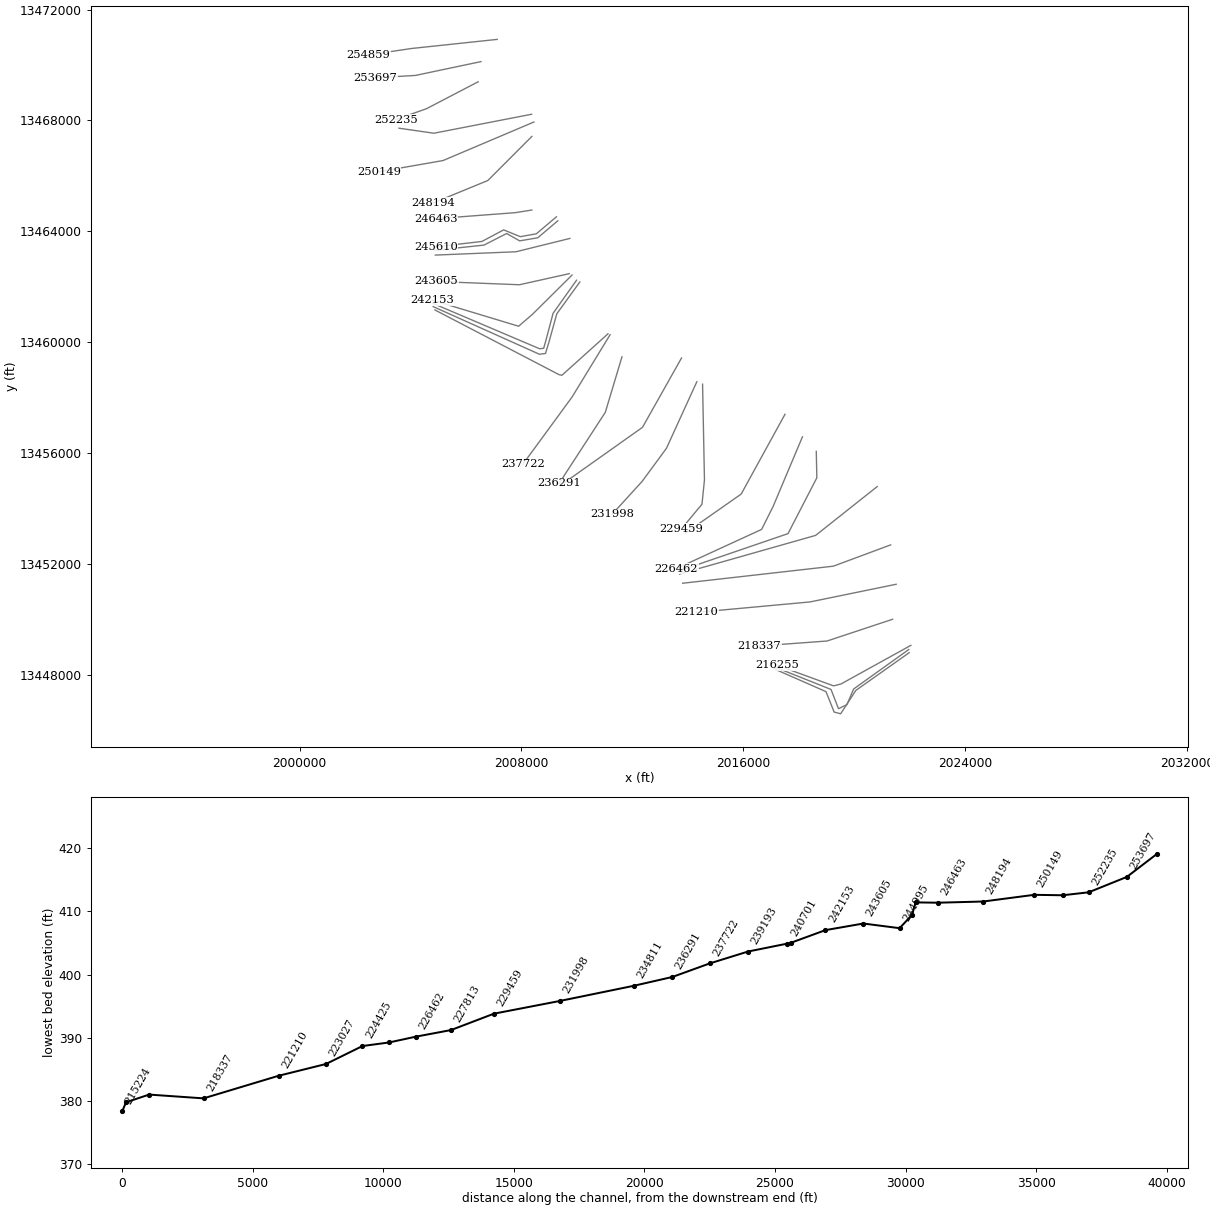
HEC-RAS study San Miguel Creek.prj: San Miguel Creek Base Level Engineering

--- San Miguel Creek.g01 (geometry) --- (continued)

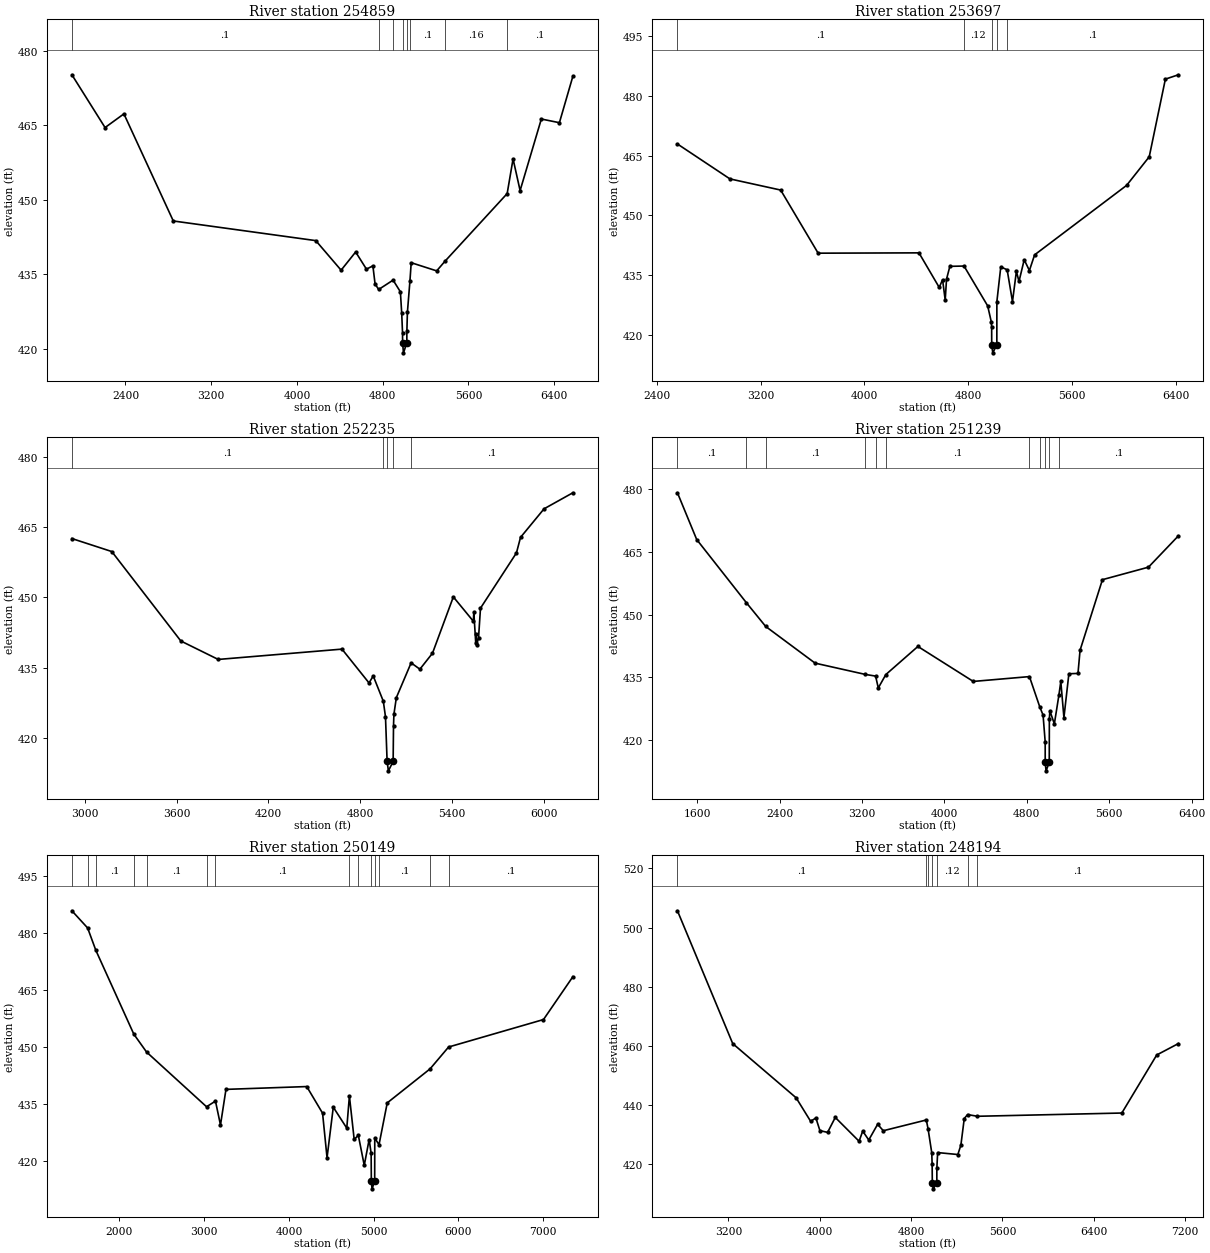
Type RM Length L Ch R = 1 ,254859  ,1162,1162,1162
BEGIN DESCRIPTION:
San Miguel Creek 106.0
END DESCRIPTION:
XS GIS Cut Line= 3
      2007125.04       13470925.      2004042.38     13470597.55
      2002485.71     13470366.62
#Sta/Elev= 30
    1900  475.21  2209.3  464.57  2385.2  467.33    2846  445.74  4175.3  441.78
  4411.6  435.82  4547.3  439.49    4648  436.03  4708.2  436.69  4728.4  433.05
  4762.1  431.93  4896.6  433.82  4964.7  431.46    4977  427.14  4984.8  423.15
  4985.2  421.16  4993.6  419.16  5024.6  421.16  5025.2  423.49  5030.2  427.34
  5053.9  433.68  5065.6  437.33  5303.2  435.68  5378.9  437.58  5960.9  451.26
  6015.9  458.25  6081.6  451.87  6279.7  466.29  6448.2  465.55  6573.7  474.89
#Mann= 8 ,-1 , 0
    1900      .1       0  4762.1     .16       0  4896.6     .12       0
  4985.2     .07       0  5024.6     .12       0  5053.9      .1       0
  5378.9     .16       0  5960.9      .1       0
Bank Sta=4985.2,5024.6
XS Rating Curve= 0 ,0
Exp/Cntr=0.3,0.1

Type RM Length L Ch R = 1 ,253697  ,1462,1462,1462
BEGIN DESCRIPTION:
San Miguel Creek 105.0
END DESCRIPTION:
XS GIS Cut Line= 3
      2006539.55     13470123.56        2004175.       13469625.
      2002737.44     13469541.96
#Sta/Elev= 30
  2560.1  467.89  2964.2  459.13  3354.8  456.33  3643.3  440.49  4419.4  440.57
  4575.5  431.89  4601.1  433.84  4621.5  428.73  4631.7  433.97  4657.3  437.19
  4766.4  437.26  4948.5  427.26  4976.6   423.2  4979.1  421.88  4979.5  417.48
  4987.8  415.48  5018.9  417.48  5019.2  428.33  5049.3  437.05  5098.4  436.32
  5139.4  428.34  5169.5  435.93  5189.5  433.39  5229.6  438.84  5269.6  436.14
  5309.7  440.07  6017.8   457.5  6192.1  464.68  6316.4  484.17  6416.6  485.26
#Mann= 5 ,-1 , 0
  2560.1      .1       0  4766.4     .12       0  4979.5     .07       0
  5018.9     .12       0  5098.4      .1       0
Bank Sta=4979.5,5018.9
XS Rating Curve= 0 ,0
Exp/Cntr=0.3,0.1

Type RM Length L Ch R = 1 ,252235  ,996,996,996
BEGIN DESCRIPTION:
San Miguel Creek 104.0
END DESCRIPTION:
XS GIS Cut Line= 3
      2006438.83     13469396.69        2004575.       13468425.
      2003470.11     13468033.86
#Sta/Elev= 30
  2915.9  462.56  3176.6  459.79  3627.9  440.72  3872.3  436.79    4681  438.99
  4857.8  431.78  4885.3  433.27  4951.2  427.88  4965.4  424.56    4976  415.04
  4984.4  413.04  5015.4  415.04  5017.8  422.63  5020.5  425.11  5036.4  428.65
  5132.9  436.06  5190.2  434.71  5272.5  438.11  5408.8  450.12  5539.9  444.92
  5542.6  446.88  5555.4  440.24    5558  442.17  5561.5  439.97  5573.5  441.39
  5586.3  447.72  5821.4  459.51  5847.9  462.81  6001.7   468.9  6189.9  472.32
#Mann= 5 ,-1 , 0
  2915.9      .1       0  4951.2     .12       0    4976     .07       0
  5015.4     .12       0  5132.9      .1       0
Bank Sta=4976,5015.4
XS Rating Curve= 0 ,0
Exp/Cntr=0.3,0.1

Type RM Length L Ch R = 1 ,251239  ,1090,1090,1090
BEGIN DESCRIPTION:
San Miguel Creek 103.0
END DESCRIPTION:
XS GIS Cut Line= 3
      2008365.96     13468224.84       2004840.8     13467540.38
      2003582.95     13467721.37
#Sta/Elev= 30
    1409  479.19  1595.9  467.99  2079.1  452.82  2265.6  447.16  2745.2  438.37
  3232.6  435.67  3332.2  435.27  3358.2  432.43  3431.7  435.64  3742.8  442.37
  4280.1  433.99  4825.2  435.15  4924.7  427.95  4957.5  425.93  4978.1   419.5
  4978.2  414.57  4986.5  412.57  5017.6  414.57  5018.5  425.02  5023.5  426.95
    5067  423.82  5111.4  430.74  5129.6  433.99  5159.9  425.32    5208  435.83
  5296.3  435.91  5316.5  441.46  5533.7  458.37  5980.6  461.37  6270.8  468.87
#Mann= 11 ,-1 , 0
    1409      .1       0  2079.1     .05       0  2265.6      .1       0
  3232.6     .07       0  3332.2     .12       0  3431.7      .1       0
  4825.2     .16       0  4924.7     .12       0  4978.2     .07       0
  5017.6     .12       0  5111.4      .1       0
Bank Sta=4978.2,5017.6
XS Rating Curve= 0 ,0
Exp/Cntr=0.3,0.1

Type RM Length L Ch R = 1 ,250149  ,1955,1955,1955
BEGIN DESCRIPTION:
San Miguel Creek 102.0
END DESCRIPTION:
XS GIS Cut Line= 3
      2008449.32     13467944.76       2005170.8     13466554.54
      2002854.41     13466150.29
#Sta/Elev= 30
  1438.9  485.91  1624.5  481.38  1721.1  475.51  2169.9  453.39  2320.4  448.68
  3028.1  434.27  3133.4  435.76  3192.6  429.47  3257.3  438.85  4210.7  439.59
  4397.4  432.58  4450.2  420.84  4523.9  434.15  4683.2  428.64  4714.1   437.1
  4770.5  425.66  4819.5  426.75  4889.5  418.83  4947.1  425.64  4970.7     422
    4973  414.64  4981.4  412.64  5012.4  414.64  5013.5  426.01  5063.8  424.28
  5160.7  435.29  5666.2  444.25  5884.8  450.01  7004.9  457.25  7351.4  468.53
#Mann= 14 ,-1 , 0
  1438.9      .1       0  1624.5     .16       0  1721.1      .1       0
  2169.9     .05       0  2320.4      .1       0  3028.1     .12       0
  3133.4      .1       0  4714.1     .16       0  4819.5     .12       0
    4973     .07       0  5012.4     .12       0  5063.8      .1       0
  5666.2     .05       0  5884.8      .1       0
Bank Sta=4973,5012.4
XS Rating Curve= 0 ,0
Exp/Cntr=0.3,0.1

Type RM Length L Ch R = 1 ,248194  ,1731,1731,1731
BEGIN DESCRIPTION:
San Miguel Creek 101.0
END DESCRIPTION:
XS GIS Cut Line= 3
      2008374.97     13467424.97      2006787.39     13465834.97
      2004806.96     13465021.73
#Sta/Elev= 30
  2753.1  505.66  3237.4  460.72  3792.5  442.39  3919.8  434.43  3965.7  435.56
  4001.1  431.28  4068.3  430.68  4135.5  435.74  4344.1  427.68  4375.9  431.11
  4428.9  428.11  4506.7  433.43  4556.2  431.24    4933  434.88  4948.6  431.83
  4980.5  423.82    4984  419.98  4985.6  413.58  4993.9  411.58    5025  413.58
  5025.2   418.5  5032.3  423.85  5209.2  423.19  5235.9  426.39  5265.3  435.35
  5294.3  436.71  5380.7  436.13  6645.5  437.23  6951.1  456.87  7140.9  460.73
#Mann= 7 ,-1 , 0
  2753.1      .1       0    4933     .16       0  4948.6     .12       0
  4985.6     .07       0    5025     .12       0  5294.3     .16       0
  5380.7      .1       0
Bank Sta=4985.6,5025
XS Rating Curve= 0 ,0
Exp/Cntr=0.3,0.1

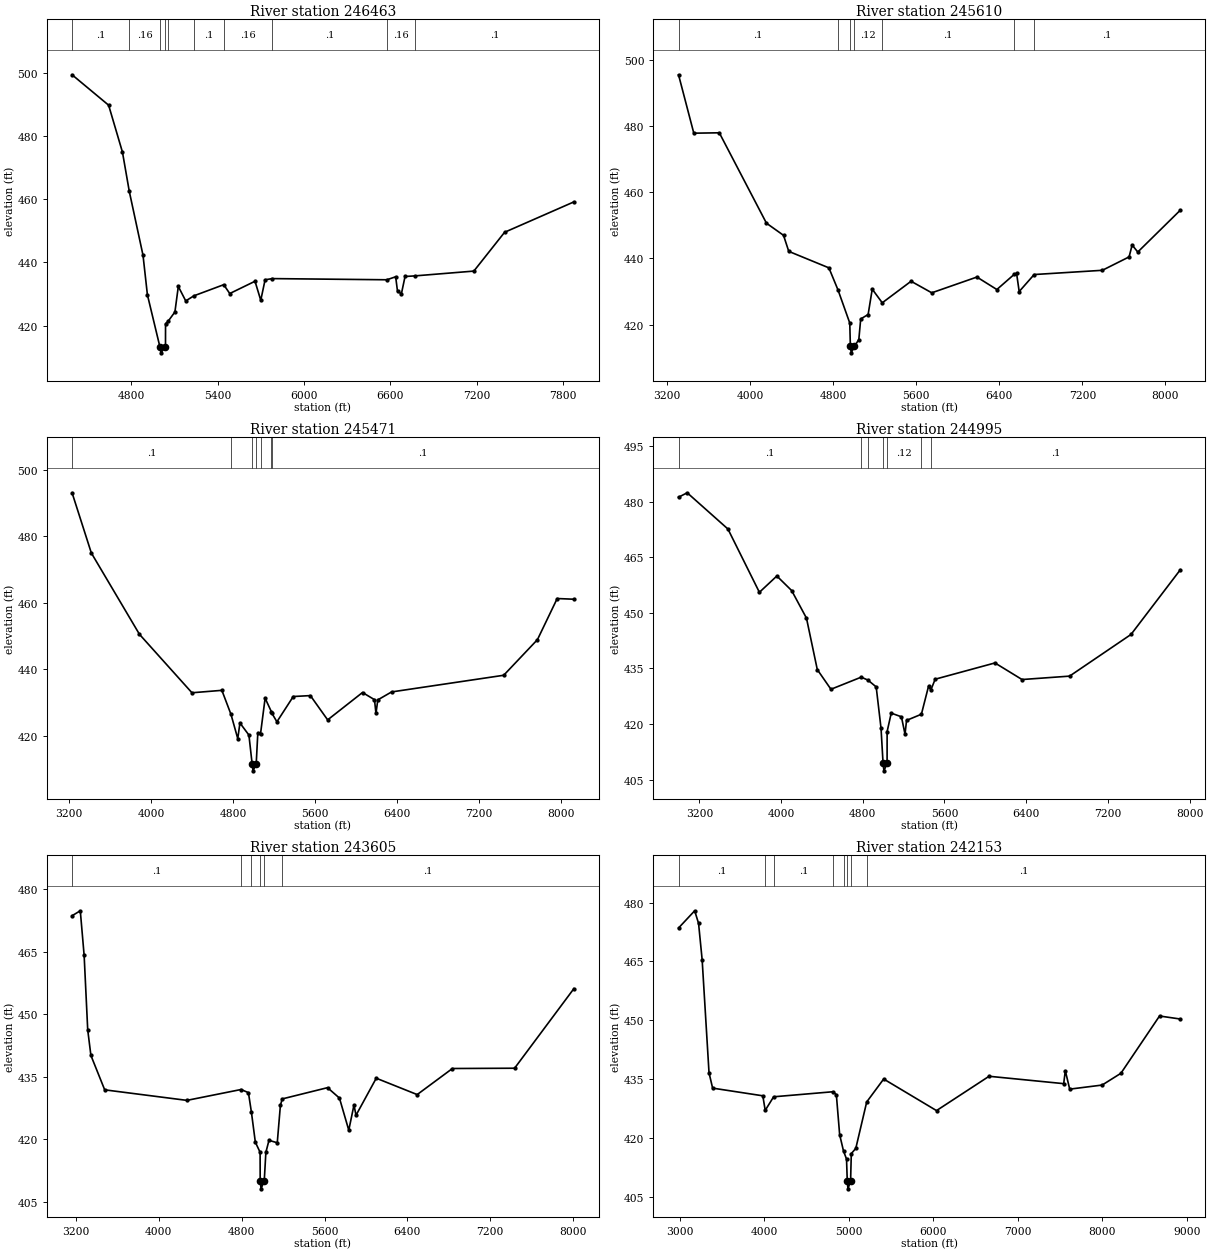
Type RM Length L Ch R = 1 ,246463  ,853,853,853
BEGIN DESCRIPTION:
San Miguel Creek 100.0
END DESCRIPTION:
XS GIS Cut Line= 3
      2008374.61     13464769.97        2007775.       13464675.
      2004902.41     13464457.48
#Sta/Elev= 30
  4388.7  499.45  4642.8  489.82  4738.9  474.96  4786.4  462.53  4881.9  442.27
  4912.3  429.78  4998.7  413.39    5007  411.39  5038.1  413.39  5038.4  420.61
  5056.2  421.38  5103.6  424.34  5127.2  432.41  5178.8  427.83  5235.6  429.45
  5442.8  432.97  5484.7  430.17  5660.3  434.06  5700.3  428.03  5730.4  434.53
  5781.4   434.9  6576.9  434.53    6638  435.48  6650.9  430.83  6678.1  430.14
  6703.2  435.57  6772.2  435.76  7181.5  437.28  7395.1  449.57  7876.6  459.19
#Mann= 10 ,-1 , 0
  4388.7      .1       0  4786.4     .16       0  4998.7     .07       0
  5038.1     .16       0  5056.2     .12       0  5235.6      .1       0
  5442.8     .16       0  5781.4      .1       0  6576.9     .16       0
  6772.2      .1       0
Bank Sta=4998.7,5038.1
XS Rating Curve= 0 ,0
Exp/Cntr=0.3,0.1

Type RM Length L Ch R = 1 ,245610  ,139,139,139
BEGIN DESCRIPTION:
Mapping XS 76c6a970
END DESCRIPTION:
XS GIS Cut Line= 6
        2009261.     13464526.01      2008537.16     13463913.07
      2007958.55     13463808.91      2007358.23     13464053.79
      2006573.51     13463637.12      2004906.85     13463442.68
#Sta/Elev= 30
    3313  495.46    3460  477.81  3705.4  477.93  4159.4  450.61  4323.6  446.95
    4374   442.1  4760.3  437.12  4848.4  430.41  4961.2  420.45    4967  413.44
  4975.4  411.44  5006.4  413.44  5048.4  415.45  5066.5  421.68  5137.9  423.02
  5177.5  430.68  5273.9  426.56  5551.3  433.07  5750.5  429.58    6185  434.34
  6377.1  430.57    6545  435.18  6566.7   435.5  6591.9  429.96  6736.1   435.1
  7392.3  436.38  7649.9  440.43  7679.2  444.03  7733.4   441.9    8143  454.55
#Mann= 7 ,-1 , 0
    3313      .1       0  4848.4     .12       0    4967     .07       0
  5006.4     .12       0  5273.9      .1       0    6545     .16       0
  6736.1      .1       0
Bank Sta=4967,5006.4
XS Rating Curve= 0 ,0
Exp/Cntr=0.3,0.1

Type RM Length L Ch R = 1 ,245471  ,476,476,476
BEGIN DESCRIPTION:
Mapping XS 2eaed3d5
END DESCRIPTION:
XS GIS Cut Line= 6
      2009309.64     13464380.19       2008587.4     13463769.07
      2007934.62     13463657.95      2007465.11     13463923.66
       2006649.9     13463505.18      2004879.57     13463317.73
#Sta/Elev= 30
  3227.8  493.06  3416.1  474.95  3886.1  450.51  4398.7  432.94  4690.9  433.67
  4779.7  426.47  4846.2  419.15  4867.3  423.86  4955.1  420.22  4986.8  411.47
  4995.2  409.47  5026.2  411.47  5042.1  420.95  5068.5   420.6  5113.3  431.32
  5174.3  427.25  5176.5  426.94  5228.5  424.21  5388.1  431.81  5555.3  432.09
  5724.1  424.79  6064.5  433.02  6181.6  430.86    6196  426.71  6213.8   430.8
  6348.5  433.19  7443.5   438.2  7773.1  448.91  7966.1  461.27  8128.8  461.06
#Mann= 7 ,-1 , 0
  3227.8      .1       0  4779.7     .12       0  4986.8     .07       0
  5026.2     .12       0  5068.5     .16       0  5174.3     .12       0
  5176.5      .1       0
Bank Sta=4986.8,5026.2
XS Rating Curve= 0 ,0
Exp/Cntr=0.3,0.1

Type RM Length L Ch R = 1 ,244995  ,1390,1390,1390
BEGIN DESCRIPTION:
San Miguel Creek 99.0
END DESCRIPTION:
XS GIS Cut Line= 3
      2009746.18     13463745.68       2007800.8     13463264.54
      2004894.15     13463145.11
#Sta/Elev= 30
    2996  481.22  3080.9  482.42  3479.6  472.64  3787.7  455.55  3958.6  459.95
  4103.6  456.02  4248.6  448.58  4354.7  434.68  4488.3  429.37  4784.5  432.64
  4849.8  431.86  4931.3  430.01  4978.7  418.84  4998.6  409.35    5007  407.35
    5038  409.35  5038.3  417.94  5078.4  422.93  5178.4  421.94  5213.5  417.24
  5228.5  420.97  5373.9  422.63  5443.7  430.18  5466.5  429.17  5508.7  432.09
  6094.2  436.48  6359.4     432  6824.8  432.92  7426.2  444.17  7909.1  461.64
#Mann= 7 ,-1 , 0
    2996      .1       0  4784.5     .16       0  4849.8     .12       0
  4998.6     .07       0    5038     .12       0  5373.9     .16       0
  5466.5      .1       0
Bank Sta=4998.6,5038
XS Rating Curve= 0 ,0
Exp/Cntr=0.3,0.1

Type RM Length L Ch R = 1 ,243605  ,1452,1452,1452
BEGIN DESCRIPTION:
San Miguel Creek 98.0
END DESCRIPTION:
XS GIS Cut Line= 3
      2009725.03     13462475.01        2007925.       13462075.
      2004925.67     13462193.31
#Sta/Elev= 30
    3162  473.66  3241.4  474.85  3278.6  464.12  3313.1  446.26  3343.9  440.12
    3477  431.86  4270.9  429.33  4794.1  431.94  4865.1  431.18  4894.1  426.46
  4931.7   419.3  4977.8  416.86  4978.6  410.09  4986.9  408.09    5018  410.09
  5033.5  416.85  5063.5  419.74  5143.5  419.15  5173.6  428.11  5191.3  429.68
  5628.9  432.38    5744  429.88  5834.1  422.17  5884.1   428.2  5904.1  425.76
  6099.3  434.65  6494.6  430.72  6834.9  436.98  7435.3  437.05  8007.6  456.15
#Mann= 6 ,-1 , 0
    3162      .1       0  4794.1     .16       0  4894.1     .12       0
  4978.6     .07       0    5018     .12       0  5191.3      .1       0
Bank Sta=4978.6,5018
XS Rating Curve= 0 ,0
Exp/Cntr=0.3,0.1

Type RM Length L Ch R = 1 ,242153  ,1317,1317,1317
BEGIN DESCRIPTION:
San Miguel Creek 97.0
END DESCRIPTION:
XS GIS Cut Line= 4
        2009825.       13462425.      2008396.53     13461008.81
      2007897.01     13460578.91      2004772.05     13461523.34
#Sta/Elev= 30
  2988.5  473.52  3179.4  477.91  3225.4   474.7  3267.8  465.43  3349.1  436.62
  3391.6  432.71  3985.5  430.75  4013.6  427.04  4113.3   430.5  4816.8  431.79
  4855.3     431  4894.2  420.84  4939.9  416.67  4975.5  414.63  4984.2  409.04
  4992.6  407.04  5023.6  409.04  5031.9  416.02  5085.1  417.35  5214.1  429.18
  5414.8  435.03  6039.8  426.98  6661.4  435.73  7544.1  433.85  7563.2  437.15
  7615.2  432.45  7998.6  433.49  8220.7  436.49  8677.6  451.09  8923.6  450.32
#Mann= 8 ,-1 , 0
  2988.5      .1       0  4013.6     .16       0  4113.3      .1       0
  4816.8     .16       0  4939.9     .12       0  4984.2     .07       0
  5023.6     .12       0  5214.1      .1       0
Bank Sta=4984.2,5023.6
XS Rating Curve= 0 ,0
Exp/Cntr=0.3,0.1

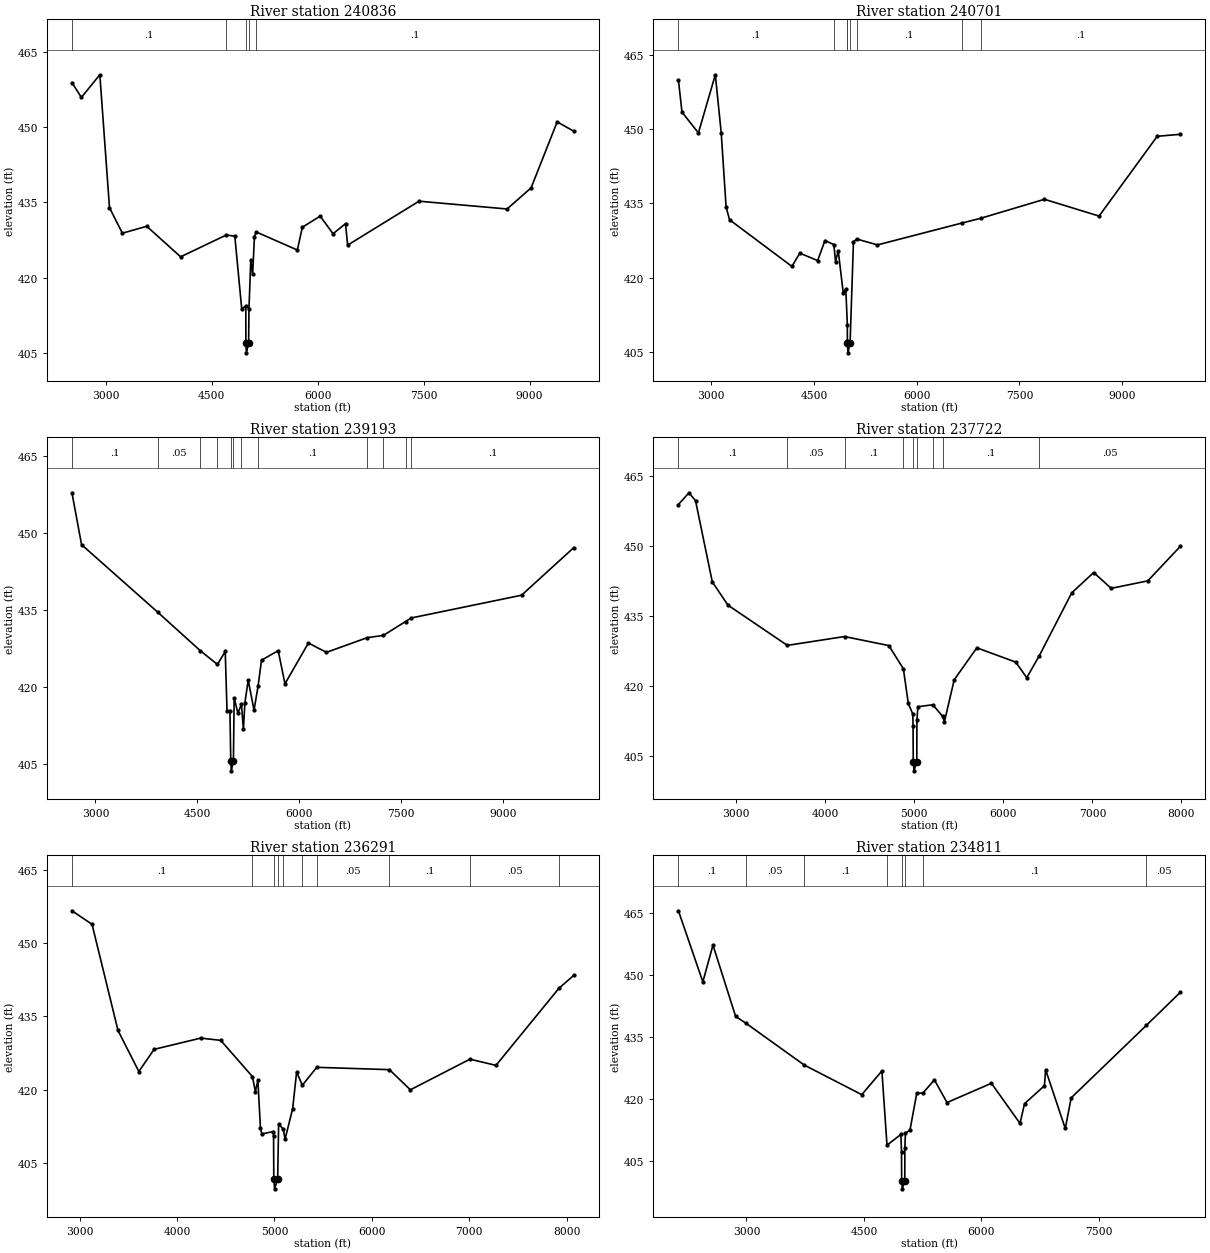
Type RM Length L Ch R = 1 ,240836  ,135,135,135
BEGIN DESCRIPTION:
Mapping XS d3607fdc
END DESCRIPTION:
XS GIS Cut Line= 6
       2009987.3     13462238.65      2009140.07     13461044.19
       2008880.8     13460064.54      2008801.57     13459784.33
      2008653.96     13459766.41      2004800.28     13461405.09
#Sta/Elev= 30
  2522.2  458.82  2655.6  455.88    2917  460.38  3053.6  433.93  3236.3  428.85
  3580.8  430.23  4060.8  424.15  4708.6   428.5    4828  428.25    4926  413.72
  4983.8  414.43  4984.1  407.04  4992.5  405.04  5023.5  407.04  5028.1  413.83
  5054.1  423.47  5080.1  420.71    5106  428.19  5129.8   429.1  5713.1   425.5
  5783.9  430.04  6036.6  432.25  6218.4  428.74  6394.8  430.75  6424.9  426.47
  7435.5  435.22  8682.1  433.67    9022  437.87  9391.5  451.01  9627.5  449.14
#Mann= 5 ,-1 , 0
  2522.2      .1       0  4708.6     .16       0  4984.1     .07       0
  5023.5     .16       0  5129.8      .1       0
Bank Sta=4984.1,5023.5
XS Rating Curve= 0 ,0
Exp/Cntr=0.3,0.1

Type RM Length L Ch R = 1 ,240701  ,1508,1508,1508
BEGIN DESCRIPTION:
Mapping XS cebd56f2
END DESCRIPTION:
XS GIS Cut Line= 6
      2010106.63     13462175.79      2009274.28     13461026.57
       2008990.8     13460004.54       2008867.5     13459596.27
      2008647.01     13459568.49        2004815.     13461286.87
#Sta/Elev= 30
  2520.4  459.88  2572.5   453.4  2812.3  449.21  3059.3  460.92  3145.2  449.26
  3216.3  434.32  3266.6  431.72  4177.1  422.32    4293  424.99  4553.7  423.49
  4659.7  427.53  4789.9  426.72  4814.3  423.28  4853.8  425.49  4927.5   416.9
  4964.4  417.78  4986.7  410.54  4987.5  407.31  4987.6  406.91    4996  404.91
    5027  406.91  5075.9  427.23  5123.2  427.84  5426.5  426.65  6657.8  431.05
  6938.3  432.03  7864.5  435.84    8662  432.46  9511.3  448.53  9848.4  448.93
#Mann= 8 ,-1 , 0
  2520.4      .1       0  4789.9     .16       0  4987.5     .12       0
  4987.6     .07       0    5027     .12       0  5123.2      .1       0
  6657.8     .05       0  6938.3      .1       0
Bank Sta=4987.6,5027
XS Rating Curve= 0 ,0
Exp/Cntr=0.3,0.1

Type RM Length L Ch R = 1 ,239193  ,1471,1471,1471
BEGIN DESCRIPTION:
San Miguel Creek 95.0
END DESCRIPTION:
XS GIS Cut Line= 4
      2011120.06     13460304.78      2009459.31     13458809.36
       2009350.8     13458834.54      2004877.24     13461166.13
#Sta/Elev= 30
  2653.8  457.91  2795.3  447.79  3917.6   434.6  4541.5  427.12  4796.4  424.41
    4911  426.95  4937.5  415.27  4980.1  415.42  4992.3  405.65  5000.6  403.65
  5031.7  405.65  5042.3  417.89  5097.6  414.91  5149.4  416.63  5178.5  411.75
  5201.1  416.98  5249.4  421.35    5335  415.49  5394.7  420.19  5445.4  425.25
  5691.1   427.1  5790.5  420.63  6135.6  428.59    6402  426.77  7001.6  429.64
  7239.5  430.07  7566.6  432.79  7650.3  433.48  9274.5  437.92 10044.7  447.22
#Mann= 12 ,-1 , 0
  2653.8      .1       0  3917.6     .05       0  4541.5      .1       0
  4796.4     .12       0  4992.3     .07       0  5031.7     .12       0
  5149.4     .16       0  5394.7      .1       0  7001.6     .05       0
  7239.5      .1       0  7566.6     .05       0  7650.3      .1       0
Bank Sta=4992.3,5031.7
XS Rating Curve= 0 ,0
Exp/Cntr=0.3,0.1

Type RM Length L Ch R = 1 ,237722  ,1431,1431,1431
BEGIN DESCRIPTION:
San Miguel Creek 94.0
END DESCRIPTION:
XS GIS Cut Line= 3
      2011196.71     13460272.06        2009825.       13458025.
      2008049.97     13455599.96
#Sta/Elev= 30
  2349.7  458.91  2468.7  461.43  2542.2  459.72  2730.1  442.31  2905.7  437.32
  3573.4  428.68  4215.4  430.58  4713.3  428.64  4876.8  423.65    4932  416.22
  4982.4  413.96  4985.5  411.41  4987.6  403.76    4996  401.76  5027.3  403.76
  5028.8  412.65  5039.9  415.52  5206.7  415.94  5318.2  413.45  5336.7  412.22
  5447.5  421.29  5701.5  428.16    6138   425.1  6262.8  421.75  6404.2  426.49
  6767.7  439.95  7014.4  444.32  7210.9  440.92  7622.8  442.53  7987.6  449.94
#Mann= 9 ,-1 , 0
  2349.7      .1       0  3573.4     .05       0  4215.4      .1       0
  4876.8     .12       0  4987.6     .07       0  5027.3     .12       0
  5206.7     .16       0  5318.2      .1       0  6404.2     .05       0
Bank Sta=4987.6,5027.3
XS Rating Curve= 0 ,0
Exp/Cntr=0.3,0.1

Type RM Length L Ch R = 1 ,236291  ,1480,1480,1480
BEGIN DESCRIPTION:
San Miguel Creek 93.0
END DESCRIPTION:
XS GIS Cut Line= 3
        2011625.       13459475.        2011025.       13457475.
      2009356.39     13454907.42
#Sta/Elev= 30
  2921.9   456.7  3128.1  453.92  3394.3  432.13  3608.3   423.7    3765  428.25
  4243.5  430.56  4448.8  430.09  4774.2  422.65  4803.8  419.59  4829.9  421.88
    4856  412.11  4869.9  410.88  4986.5  411.37  4990.8   410.5  4993.1  401.61
  5001.5  399.61  5032.8  401.61  5042.8  412.95  5091.9  411.82  5108.1  409.75
  5186.6  416.08  5227.4  423.61  5285.8  420.87  5433.9  424.56  6179.7  424.08
  6394.4  419.94  7005.7  426.23    7273  424.96  7918.1  440.77  8072.1  443.45
#Mann= 10 ,-1 , 0
  2921.9      .1       0  4774.2     .12       0  4993.1     .07       0
  5032.8     .12       0  5091.9     .16       0  5285.8      .1       0
  5433.9     .05       0  6179.7      .1       0  7005.7     .05       0
  7918.1      .1       0
Bank Sta=4993.1,5032.8
XS Rating Curve= 0 ,0
Exp/Cntr=0.3,0.1

Type RM Length L Ch R = 1 ,234811  ,2813,2813,2813
BEGIN DESCRIPTION:
San Miguel Creek 92.0
END DESCRIPTION:
XS GIS Cut Line= 3
      2013772.78     13459432.17      2012365.38     13456931.97
      2009475.94     13454885.76
#Sta/Elev= 30
  2130.9  465.62  2442.8  448.38  2572.2   457.3  2861.2  440.03  2993.6  438.35
  3738.1  428.22  4472.6  421.04  4729.7   426.8  4794.5  408.79  4971.9  411.39
  4979.9  407.25  4982.1  400.21  4990.5  398.21  5021.8  400.21  5022.8   408.2
  5030.2   411.7  5088.1  412.45  5174.2  421.35  5254.8  421.47    5400  424.62
  5561.1  419.13    6128   423.8  6493.4  414.08  6551.3  418.85  6805.4  423.21
  6820.2  427.09  7071.2  412.84  7146.9  420.27  8108.1  437.86  8540.6  445.85
#Mann= 8 ,-1 , 0
  2130.9      .1       0  2993.6     .05       0  3738.1      .1       0
  4794.5     .12       0  4982.1     .07       0  5021.8     .12       0
  5254.8      .1       0  8108.1     .05       0
Bank Sta=4982.1,5021.8
XS Rating Curve= 0 ,0
Exp/Cntr=0.3,0.1

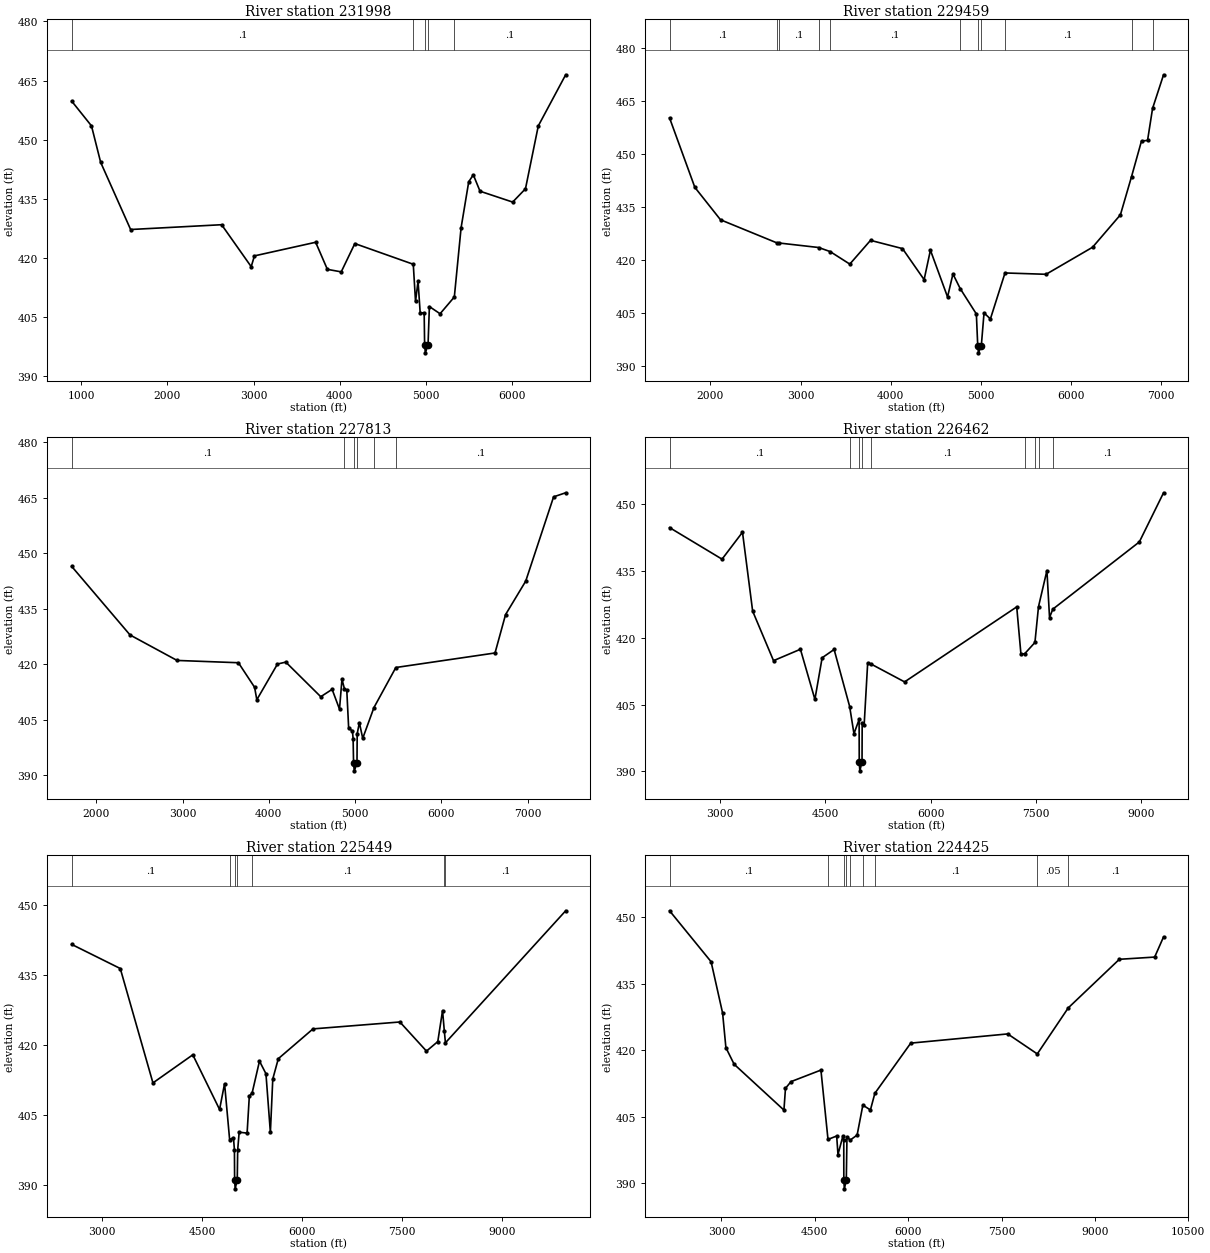
Type RM Length L Ch R = 1 ,231998  ,2539,2539,2539
BEGIN DESCRIPTION:
San Miguel Creek 91.0
END DESCRIPTION:
XS GIS Cut Line= 4
        2014325.       13458575.      2013230.25     13456176.98
      2012358.08     13454989.32      2011266.33     13453789.88
#Sta/Elev= 30
   890.4  459.77  1120.2  453.48  1226.6  444.22  1574.3  427.15    2630  428.37
  2973.4  417.71  3010.7  420.45  3721.2  423.91    3857  417.03  4017.9  416.39
  4175.7  423.58  4853.8  418.32  4879.9  408.87  4909.2  414.03    4934  405.95
  4980.2     406  4985.4  397.82  4993.8  395.82  5025.1  397.82  5040.7  407.58
  5164.7  405.75  5330.1  410.01  5408.6   427.6  5497.1  439.28  5550.2  441.05
  5628.2  436.88  6006.9  434.12  6155.6   437.5  6304.2  453.47  6621.9  466.46
#Mann= 5 ,-1 , 0
   890.4      .1       0  4853.8     .12       0  4985.4     .07       0
  5025.1     .12       0  5330.1      .1       0
Bank Sta=4985.4,5025.1
XS Rating Curve= 0 ,0
Exp/Cntr=0.3,0.1

Type RM Length L Ch R = 1 ,229459  ,1646,1646,1646
BEGIN DESCRIPTION:
San Miguel Creek 90.0
END DESCRIPTION:
XS GIS Cut Line= 4
      2014532.34     13458488.16       2014600.8     13455034.54
      2014510.63     13454158.75      2013774.98     13453274.98
#Sta/Elev= 30
  1545.7  460.15  1826.4  440.54  2111.5  431.38  2733.1   424.9  2758.2  424.83
  3200.7  423.55  3328.6   422.4  3546.8  418.86  3776.8  425.57  4131.9  423.24
  4371.9  414.47  4441.9  422.79    4632  409.58    4692  416.07  4773.2  411.91
    4952  404.77  4967.2  395.79  4975.6  393.79  5006.9  395.79  5037.2  405.07
  5107.8  403.37    5270  416.36  5725.9  415.98    6242  423.62  6551.2  432.78
    6675  443.59  6785.5  453.65  6852.6  453.79  6908.4  462.85  7030.3  472.35
#Mann= 11 ,-1 , 0
  1545.7      .1       0  2733.1     .07       0  2758.2      .1       0
  3200.7     .05       0  3328.6      .1       0  4773.2     .12       0
  4967.2     .07       0  5006.9     .12       0    5270      .1       0
    6675     .05       0  6908.4      .1       0
Bank Sta=4967.2,5006.9
XS Rating Curve= 0 ,0
Exp/Cntr=0.3,0.1

Type RM Length L Ch R = 1 ,227813  ,1351,1351,1351
BEGIN DESCRIPTION:
San Miguel Creek 89.0
END DESCRIPTION:
XS GIS Cut Line= 3
      2017505.43     13457403.12        2015925.       13454525.
        2013925.       13453125.
#Sta/Elev= 30
  1715.7  446.49  2392.1  427.94  2937.1  421.05    3648  420.43  3835.6  413.78
  3861.2  410.42  4100.8  420.08  4197.1   420.6  4602.2  411.24  4733.9  413.23
  4819.5  407.87    4848  415.94    4876  413.45    4904  412.93  4925.8  402.66
  4969.4  402.01  4977.4  399.77  4982.4  393.19  4990.8  391.19  5022.1  393.19
  5024.5  401.23  5049.8  404.22  5088.6  399.98  5218.8  408.31  5472.4  419.14
  6621.8  423.07  6743.9  433.45  6977.5   442.5  7300.6   465.3  7440.5   466.4
#Mann= 6 ,-1 , 0
  1715.7      .1       0    4876     .12       0  4982.4     .07       0
  5022.1     .12       0  5218.8     .16       0  5472.4      .1       0
Bank Sta=4982.4,5022.1
XS Rating Curve= 0 ,0
Exp/Cntr=0.3,0.1

Type RM Length L Ch R = 1 ,226462  ,1013,1013,1013
BEGIN DESCRIPTION:
San Miguel Creek 88.0
END DESCRIPTION:
XS GIS Cut Line= 4
      2018134.78     13456589.33        2017075.       13454075.
       2016662.9      13453250.8      2013589.16     13451837.08
#Sta/Elev= 30
  2281.8   444.7  3028.9  437.62  3320.2  443.66  3464.8  425.96    3762  414.85
  4144.9  417.41  4351.1  406.17  4454.1   415.5  4624.6  417.36  4845.9  404.57
  4907.3  398.46  4980.5  401.66  4982.4  392.14  4990.8  390.14  5022.1  392.14
  5024.3  400.93  5052.3  400.43  5102.6  414.38  5155.9  414.05  5628.1  410.09
  7224.5  426.91  7284.6  416.32  7338.3  416.41  7483.7  418.93  7534.7  426.97
  7654.5  435.06  7691.7  424.53  7738.8  426.41  8970.2  441.48  9315.1  452.51
#Mann= 9 ,-1 , 0
  2281.8      .1       0  4845.9     .12       0  4982.4     .07       0
  5022.1     .12       0  5155.9      .1       0  7338.3     .05       0
  7483.7      .1       0  7534.7     .05       0  7738.8      .1       0
Bank Sta=4982.4,5022.1
XS Rating Curve= 0 ,0
Exp/Cntr=0.3,0.1

Type RM Length L Ch R = 1 ,225449  ,1024,1024,1024
BEGIN DESCRIPTION:
Mapping XS 02197e15
END DESCRIPTION:
XS GIS Cut Line= 5
      2018633.51     13456065.61      2018654.34     13455112.47
      2017964.95     13453777.42      2017614.41     13453098.58
      2013656.89     13451744.69
#Sta/Elev= 30
  2546.3  441.59  3274.6  436.42  3764.1  411.92  4361.3  417.94  4762.6  406.23
  4837.4  411.76  4913.3  399.77  4970.3   400.2  4985.2  397.59  4987.9  391.23
  4996.3  389.23  5027.6  391.23  5033.9  397.54  5056.1  401.36  5175.1  401.17
  5208.3  409.08  5250.8  409.78  5360.6  416.59  5457.4  413.89  5523.9  401.32
  5559.9  412.76  5642.9  417.11  6162.7  423.49  7464.5  424.97  7863.1  418.73
  8032.6  420.77    8104  427.42    8131  422.94  8147.2  420.51  9948.9  448.79
#Mann= 7 ,-1 , 0
  2546.3      .1       0  4913.3     .12       0  4987.9     .07       0
  5027.6     .12       0  5250.8      .1       0    8131     .05       0
  8147.2      .1       0
Bank Sta=4987.9,5027.6
XS Rating Curve= 0 ,0
Exp/Cntr=0.3,0.1

Type RM Length L Ch R = 1 ,224425  ,1398,1398,1398
BEGIN DESCRIPTION:
San Miguel Creek 87.0
END DESCRIPTION:
XS GIS Cut Line= 3
      2020831.65     13454795.52       2018610.8     13453034.54
      2013701.13     13451641.38
#Sta/Elev= 30
  2165.7  451.48    2833  439.97    3018  428.37  3070.9  420.56  3203.1  416.81
  4003.5  406.45  4028.3  411.37  4117.2  412.88  4597.9  415.49  4711.6  399.82
  4851.1   400.6  4871.9  396.41  4950.5  400.56  4964.9   399.7  4965.9  390.66
  4974.3  388.66  5005.6  390.66  5016.5  400.44  5067.3  399.66  5179.5  400.81
  5271.7  407.57  5393.2  406.48  5464.5  410.24  6041.3  421.58  7599.4  423.66
  8074.5  419.14  8572.1  429.54  9393.4  440.52  9960.6  441.02 10103.5  445.58
#Mann= 9 ,-1 , 0
  2165.7      .1       0  4711.6     .12       0  4965.9     .07       0
  5005.6     .12       0  5067.3      .1       0  5271.7     .12       0
  5464.5      .1       0  8074.5     .05       0  8572.1      .1       0
Bank Sta=4965.9,5005.6
XS Rating Curve= 0 ,0
Exp/Cntr=0.3,0.1

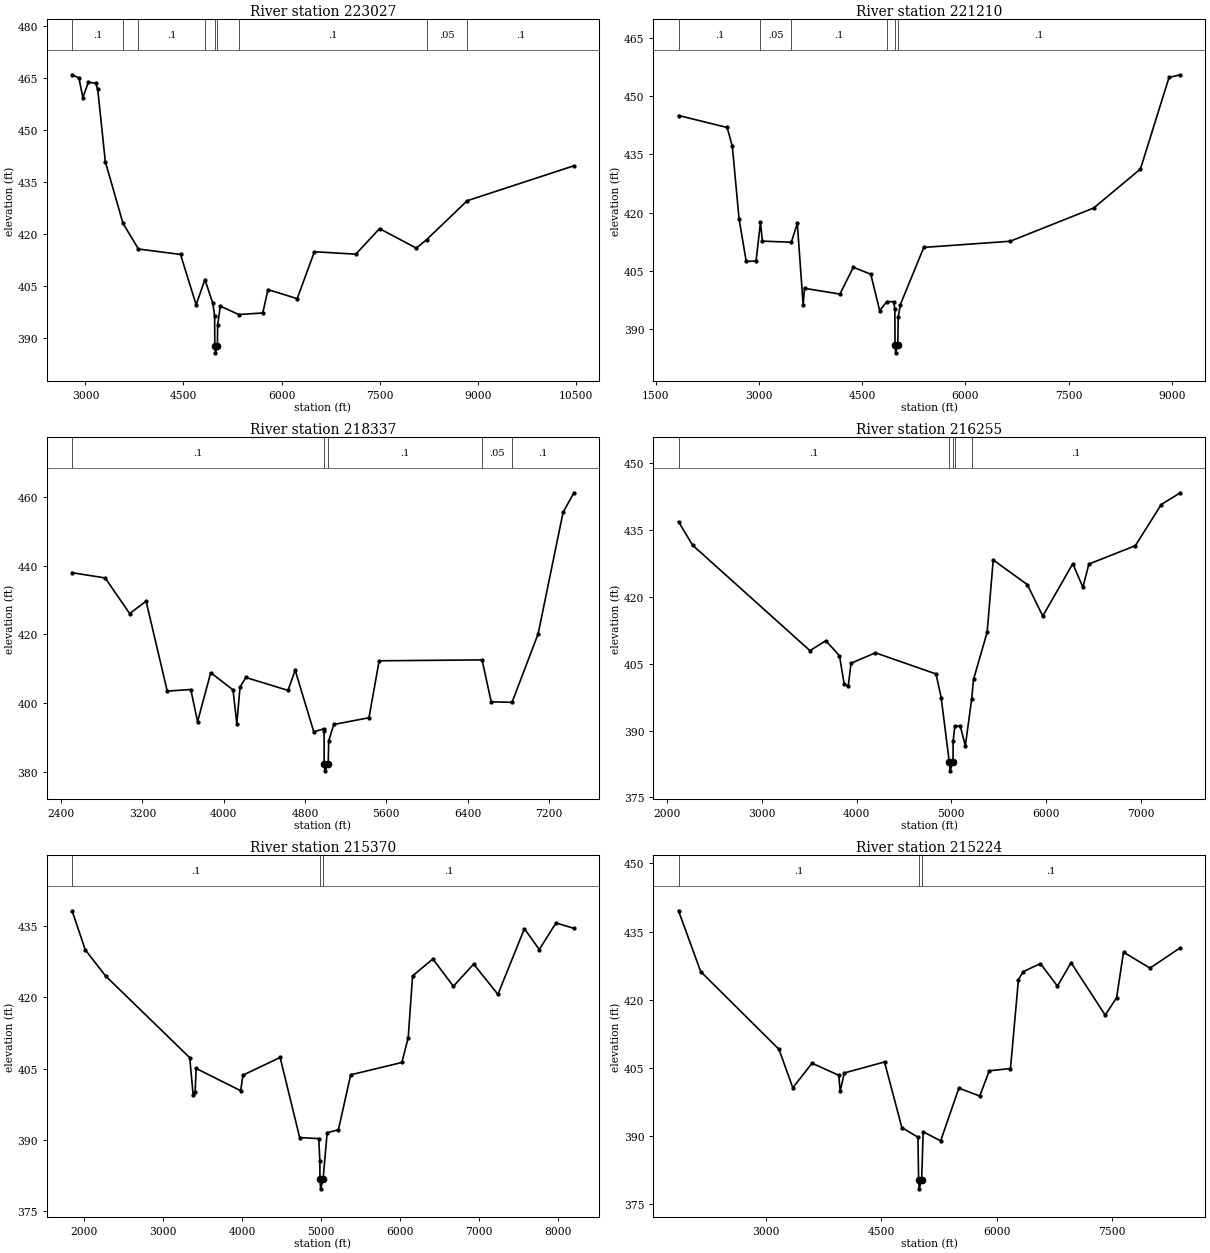
Type RM Length L Ch R = 1 ,223027  ,1817,1817,1817
BEGIN DESCRIPTION:
San Miguel Creek 86.0
END DESCRIPTION:
XS GIS Cut Line= 3
      2021316.51     13452692.07       2019250.8     13451924.54
      2013814.26     13451308.81
#Sta/Elev= 30
  2796.3  465.98    2901  465.08  2961.7  459.38  3044.8  463.81    3158  463.58
  3188.6  461.79  3304.7  440.96  3574.7  423.16  3811.9  415.74    4455  414.18
  4694.1  399.67    4828  406.93  4950.2  400.04  4976.8  396.42  4979.5  387.81
  4987.9  385.81  5019.2  387.81  5023.4  393.94  5063.7  399.26  5347.1  396.85
  5712.8  397.31  5793.2  404.04  6239.3  401.43  6502.8  414.96  7136.9  414.26
  7499.2  421.63  8060.9     416  8217.8  418.42  8840.7  429.67 10471.3  439.74
#Mann= 9 ,-1 , 0
  2796.3      .1       0  3574.7     .05       0  3811.9      .1       0
    4828     .12       0  4979.5     .07       0  5019.2     .12       0
  5347.1      .1       0  8217.8     .05       0  8840.7      .1       0
Bank Sta=4979.5,5019.2
XS Rating Curve= 0 ,0
Exp/Cntr=0.3,0.1

Type RM Length L Ch R = 1 ,221210  ,2873,2873,2873
BEGIN DESCRIPTION:
San Miguel Creek 85.0
END DESCRIPTION:
XS GIS Cut Line= 3
       2021516.6     13451272.27       2018410.8     13450634.54
      2014304.04     13450256.73
#Sta/Elev= 30
  1829.4  444.96  2536.1  441.88  2611.6     437  2709.8   418.3  2813.6  407.44
  2956.5  407.54  3020.4  417.46  3048.4  412.66  3469.3  412.38  3556.1  417.22
  3640.5  396.34  3660.9  400.53  4175.6  399.05  4370.4  405.94    4624  404.15
  4753.3  394.81  4858.7  397.11  4957.4  397.09  4974.1  395.11  4976.9  385.94
  4985.3  383.94  5016.6  385.94  5023.4  393.18  5053.5  396.32    5395  411.05
  6650.2  412.63  7865.3  421.18  8544.2   431.2  8959.9  454.74  9124.1  455.43
#Mann= 6 ,-1 , 0
  1829.4      .1       0  3020.4     .05       0  3469.3      .1       0
  4858.7     .12       0  4976.9     .07       0  5016.6      .1       0
Bank Sta=4976.9,5016.6
XS Rating Curve= 0 ,0
Exp/Cntr=0.3,0.1

Type RM Length L Ch R = 1 ,218337  ,2082,2082,2082
BEGIN DESCRIPTION:
San Miguel Creek 84.0
END DESCRIPTION:
XS GIS Cut Line= 3
      2021386.35     13450009.23       2019020.8     13449224.54
      2016581.65      13449045.7
#Sta/Elev= 30
  2507.7  437.92  2833.1   436.4  3074.9  426.05  3235.9  429.64  3444.5  403.52
    3676  403.99  3742.9  394.65  3872.3  408.89  4091.4  403.88    4129   394.1
  4160.6  404.72  4218.1  407.48  4632.7  403.73  4703.2   409.6  4886.2  391.71
  4983.8  392.54  4987.7  391.96  4988.5  382.36  4996.9  380.36  5028.2  382.36
  5033.4  389.12  5083.5  393.83  5429.4  395.79  5529.7  412.33  6542.3  412.59
  6632.4  400.41  6837.3  400.26  7093.9  420.13  7339.6  455.45  7445.7  461.14
#Mann= 5 ,-1 , 0
  2507.7      .1       0  4988.5     .07       0  5028.2      .1       0
  6542.3     .05       0  6837.3      .1       0
Bank Sta=4988.5,5028.2
XS Rating Curve= 0 ,0
Exp/Cntr=0.3,0.1

Type RM Length L Ch R = 1 ,216255  ,885,885,885
BEGIN DESCRIPTION:
San Miguel Creek 83.0
END DESCRIPTION:
XS GIS Cut Line= 4
      2022043.93      13449067.4        2019525.       13447675.
      2019259.13     13447606.51      2017239.93     13448343.76
#Sta/Elev= 30
  2117.5  436.82    2266  431.57    3506  407.92  3674.3  410.14  3818.1  406.78
  3866.8  400.53  3910.3  399.88  3940.1  405.09  4197.8  407.43  4838.2  402.69
  4892.6   397.4  4978.4  382.96  4986.8  380.96  5018.1  382.96  5018.9  387.57
  5037.2  391.05  5094.8  390.99    5148  386.57  5214.8  397.02  5234.7  401.46
  5378.4  412.05  5442.8  428.25  5803.4  422.73  5966.1  415.67  6283.3  427.41
  6390.4  422.14  6453.6  427.33  6944.2  431.45  7218.4  440.69  7419.8  443.32
#Mann= 5 ,-1 , 0
  2117.5      .1       0  4978.4     .07       0  5018.1      .1       0
  5037.2     .12       0  5214.8      .1       0
Bank Sta=4978.4,5018.1
XS Rating Curve= 0 ,0
Exp/Cntr=0.3,0.1

Type RM Length L Ch R = 1 ,215370  ,146,146,146
BEGIN DESCRIPTION:
Mapping XS 0f9ad8e3
END DESCRIPTION:
XS GIS Cut Line= 6
      2021969.98     13448918.27      2019982.13     13447494.66
      2019739.07     13446930.42      2019435.25     13446782.85
      2019166.16     13447477.29      2017144.32     13448284.28
#Sta/Elev= 30
  1845.6  438.21    2013  429.99    2271  424.49  3335.3  407.32  3378.3  399.49
  3403.5  400.16    3417  405.06  3980.3  400.37  4008.5  403.64  4479.5  407.37
    4727  390.53  4968.5   390.3  4982.7  385.51  4983.5  381.74  4991.9  379.74
  5023.2  381.74  5074.8  391.53  5217.2  392.17  5372.8  403.72  6020.7  406.31
    6101  411.55  6156.3  424.52  6413.2  428.08  6672.8  422.34  6929.7     427
  7236.7  420.63  7571.9  434.44  7760.4  430.06  7972.1  435.66  8198.1  434.51
#Mann= 3 ,-1 , 0
  1845.6      .1       0  4983.5     .07       0  5023.2      .1       0
Bank Sta=4983.5,5023.2
XS Rating Curve= 0 ,0
Exp/Cntr=0.3,0.1

Type RM Length L Ch R = 1 ,215224  ,630,630,630
BEGIN DESCRIPTION:
Mapping XS 543a18d1
END DESCRIPTION:
XS GIS Cut Line= 6
       2021987.3     13448805.39      2020060.25     13447442.57
      2019513.38     13446600.56        2019279.     13446661.32
      2018983.86     13447399.17       2017109.4     13448223.58
#Sta/Elev= 30
  1858.6  439.58  2147.1  426.18  3166.3  409.06  3346.1  400.58  3597.2  405.99
  3944.9  403.33  3962.7  399.76  4016.3  403.84  4540.4  406.27    4766  391.81
  4975.5  389.69  4984.1  380.31  4992.5  378.31  5023.8  380.31  5043.7   390.9
  5270.9  388.87  5508.4  400.51  5779.5  398.76  5904.4  404.32  6180.5  404.82
  6283.5  424.36  6343.1  426.14  6570.7  427.94  6791.8  422.97  6968.8  428.15
  7413.6  416.59  7561.9  420.43  7651.8  430.45  7997.7  426.95  8391.6  431.44
#Mann= 3 ,-1 , 0
  1858.6      .1       0  4984.1     .07       0  5023.8      .1       0
Bank Sta=4984.1,5023.8
XS Rating Curve= 0 ,0
Exp/Cntr=0.3,0.1