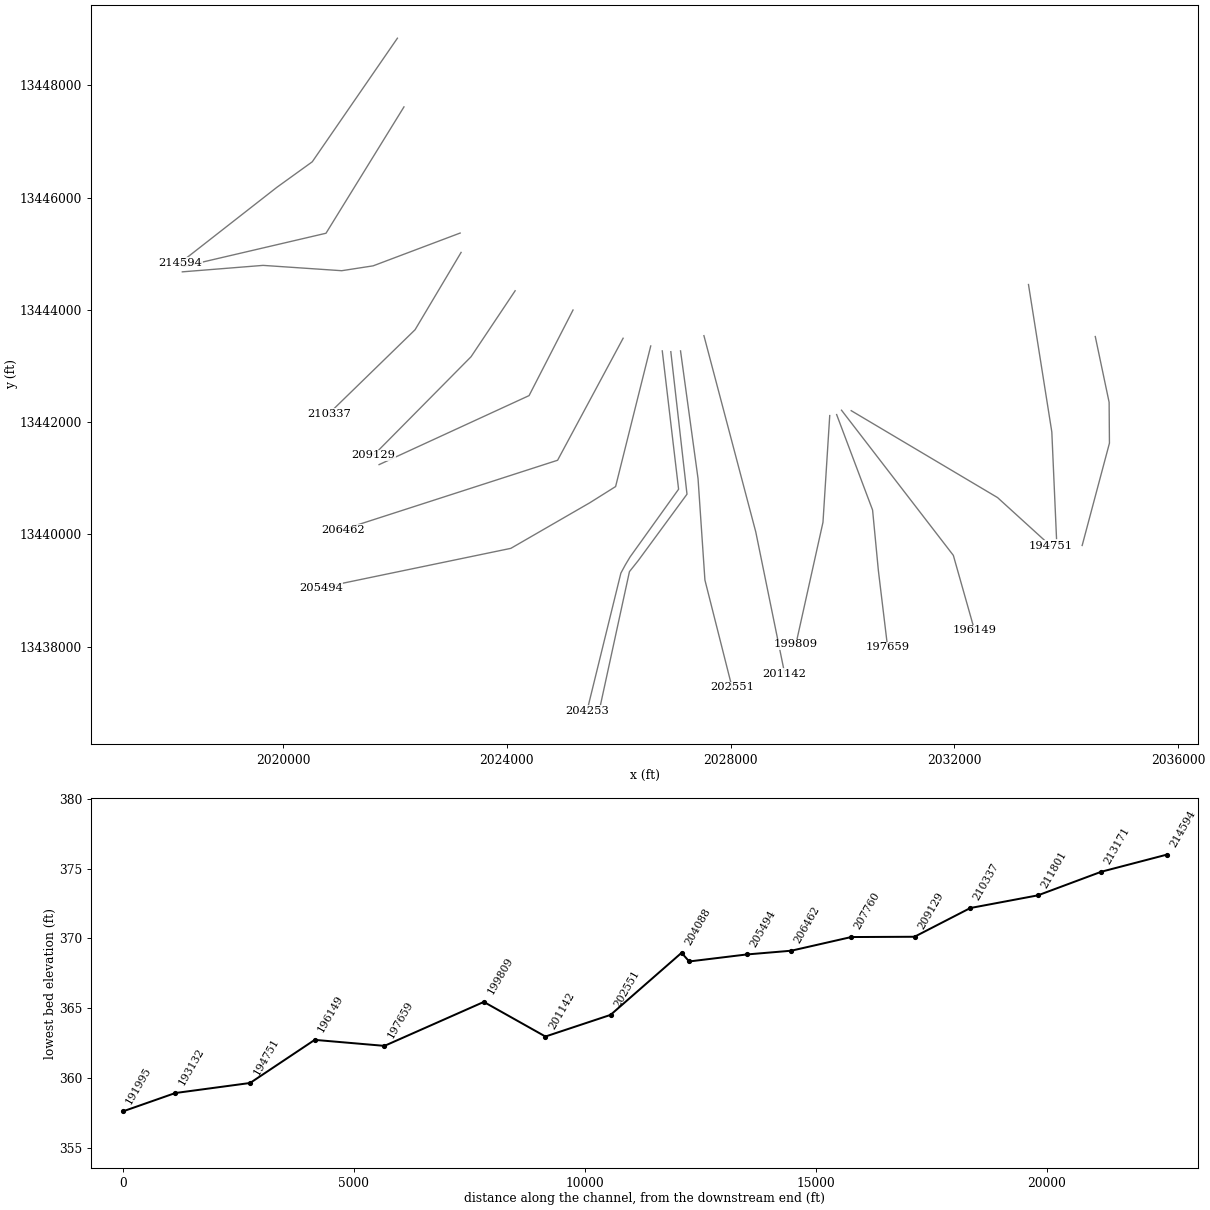
HEC-RAS study San Miguel Creek.prj: San Miguel Creek Base Level Engineering

--- San Miguel Creek.g01 (geometry) --- (continued)

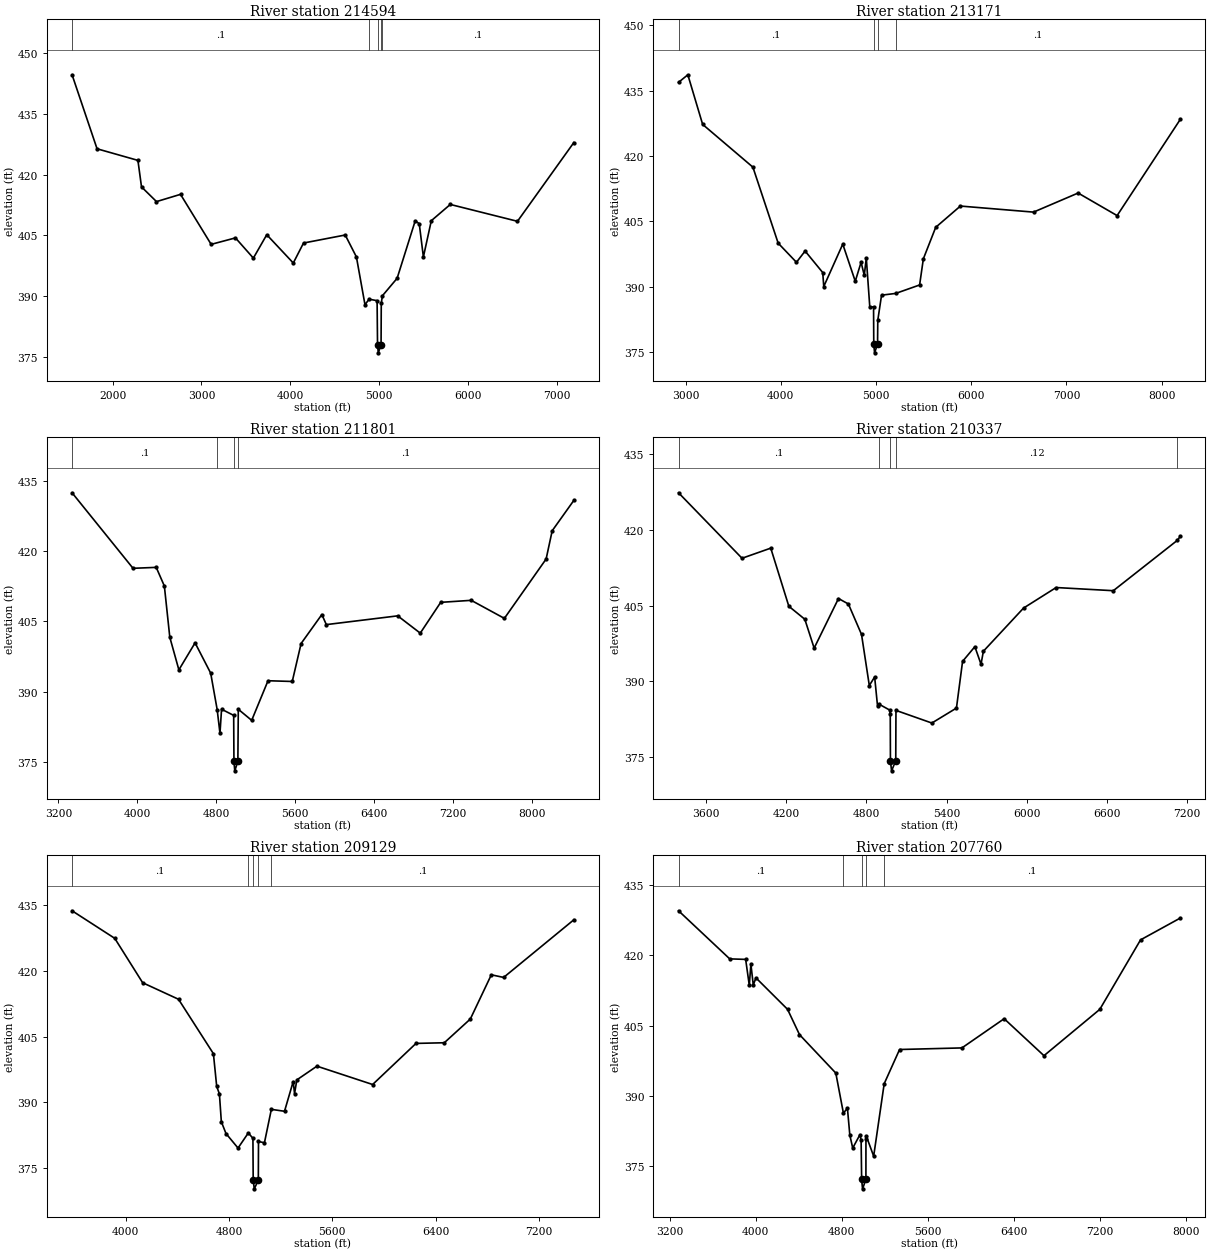
Type RM Length L Ch R = 1 ,214594  ,1423,1423,1423
BEGIN DESCRIPTION:
San Miguel Creek 82.0
END DESCRIPTION:
XS GIS Cut Line= 5
      2022044.55     13448841.47      2020522.65     13446638.76
       2019890.8     13446184.54      2019549.74     13445918.81
      2018165.07     13444839.96
#Sta/Elev= 30
  1544.5  444.61  1825.5  426.35  2285.1  423.49  2325.4  416.95    2494  413.32
  2764.1  415.11  3108.8  402.77  3381.9  404.37  3583.3  399.38    3734  405.15
  4032.4  398.17  4147.4   403.1  4616.5  405.08  4742.3  399.67  4838.7  387.88
  4884.8  389.25  4974.9  388.88  4979.7  378.01  4988.2  376.01  5019.5  378.01
  5021.8  388.24  5034.9   390.1  5200.1   394.4  5403.2  408.56  5448.9  407.88
  5495.5  399.67  5584.6  408.61  5798.1  412.62  6553.5  408.46  7187.7   427.9
#Mann= 5 ,-1 , 0
  1544.5      .1       0  4884.8     .12       0  4979.7     .07       0
  5019.5     .12       0  5034.9      .1       0
Bank Sta=4979.7,5019.5
XS Rating Curve= 0 ,0
Exp/Cntr=0.3,0.1

Type RM Length L Ch R = 1 ,213171  ,1370,1370,1370
BEGIN DESCRIPTION:
San Miguel Creek 81.0
END DESCRIPTION:
XS GIS Cut Line= 4
      2022161.73      13447617.5       2021070.8     13445854.54
      2020768.24     13445365.53      2018216.13     13444771.34
#Sta/Elev= 30
  2926.8  436.88  3024.5  438.62  3179.9  427.23  3707.6  417.41  3972.9  399.96
  4164.9  395.57  4255.7  398.15  4440.9  393.21  4451.5     390  4651.2  399.74
  4782.4  391.21  4843.6  395.58    4877  392.57  4898.2  396.57  4934.9  385.31
  4974.5  385.33  4976.6  376.78  4985.1  374.78  5016.4  376.78  5018.8  382.25
  5058.4  388.02  5206.8  388.42  5457.9  390.36  5497.4  396.37  5627.1   403.6
  5886.2  408.48  6653.9  407.09  7122.2  411.47  7531.7  406.29  8195.4  428.39
#Mann= 4 ,-1 , 0
  2926.8      .1       0  4976.6     .07       0  5016.4      .1       0
  5206.8      .1       0
Bank Sta=4976.6,5016.4
XS Rating Curve= 0 ,0
Exp/Cntr=0.3,0.1

Type RM Length L Ch R = 1 ,211801  ,1464,1464,1464
BEGIN DESCRIPTION:
San Miguel Creek 80.0
END DESCRIPTION:
XS GIS Cut Line= 5
      2023165.88     13445369.05       2021610.8     13444784.54
      2021048.84     13444697.89      2019643.91     13444792.77
      2018200.43     13444677.58
#Sta/Elev= 30
  3338.7   432.4  3956.6  416.29  4191.6  416.49  4274.2  412.51  4329.3  401.59
  4421.3  394.63  4585.4  400.39  4743.7  393.93  4809.4  386.16  4837.9  381.08
  4853.9  386.23  4976.8  384.92  4979.4  375.09  4987.9  373.09  5019.2  375.09
  5023.6  386.22  5159.3  383.86  5324.8  392.31  5570.5  392.15  5660.1  400.25
  5870.6  406.43  5915.7  404.28  6639.3  406.15  6867.9  402.46  7075.2  409.03
  7384.4  409.46  7720.5  405.61  8143.6  418.27  8205.2   424.3  8424.8  430.78
#Mann= 4 ,-1 , 0
  3338.7      .1       0  4809.4     .12       0  4979.4     .07       0
  5019.2      .1       0
Bank Sta=4979.4,5019.2
XS Rating Curve= 0 ,0
Exp/Cntr=0.3,0.1

Type RM Length L Ch R = 1 ,210337  ,1208,1208,1208
BEGIN DESCRIPTION:
San Miguel Creek 79.0
END DESCRIPTION:
XS GIS Cut Line= 3
      2023182.97     13445023.87        2022360.     13443645.34
      2020817.53     13442148.44
#Sta/Elev= 30
  3394.5  427.38  3869.6  414.38  4084.6  416.39  4219.9  404.85  4339.5  402.27
  4409.3  396.54  4591.5  406.39  4665.5   405.3  4763.8  399.26  4822.1  389.11
    4862  390.82  4883.4   385.1  4894.9  385.41  4974.2  384.25  4978.8  383.43
  4980.1  374.18  4988.6  372.18  5019.9  374.18  5021.5  384.18  5290.1  381.67
  5474.1  384.64    5520  393.91  5611.9  396.83    5658  393.34  5675.6  395.92
  5976.2  404.49  6220.1  408.57  6647.9  407.94  7125.7  417.91  7149.4  418.73
#Mann= 5 ,-1 , 0
  3394.5      .1       0  4894.9     .12       0  4980.1     .07       0
  5019.9     .12       0  7125.7     .05       0
Bank Sta=4980.1,5019.9
XS Rating Curve= 0 ,0
Exp/Cntr=0.3,0.1

Type RM Length L Ch R = 1 ,209129  ,1369,1369,1369
BEGIN DESCRIPTION:
San Miguel Creek 78.0
END DESCRIPTION:
XS GIS Cut Line= 3
      2024148.67     13444340.26       2023360.8     13443164.54
      2021620.43     13441410.55
#Sta/Elev= 30
  3584.7  433.79  3915.3  427.48  4131.5  417.31  4409.1  413.53  4679.3  401.07
  4704.8  393.58  4725.8  391.86  4740.8  385.48  4776.8  382.78    4870  379.46
  4949.7  382.92  4985.4  381.69  4987.4  372.12  4995.9  370.12  5027.2  372.12
  5028.5  380.96  5074.5  380.67  5128.1  388.32    5230  387.88  5297.2  394.68
  5307.8  391.93  5325.5  395.07  5481.1  398.21  5912.4  394.01  6248.3  403.42
  6467.5  403.57    6669     409  6831.7  419.13  6927.1  418.53  7470.9  431.73
#Mann= 5 ,-1 , 0
  3584.7      .1       0  4949.7     .12       0  4987.4     .07       0
  5027.2     .12       0  5128.1      .1       0
Bank Sta=4987.4,5027.2
XS Rating Curve= 0 ,0
Exp/Cntr=0.3,0.1

Type RM Length L Ch R = 1 ,207760  ,1298,1298,1298
BEGIN DESCRIPTION:
San Miguel Creek 77.0
END DESCRIPTION:
XS GIS Cut Line= 3
      2025183.39     13443997.38      2024397.75     13442471.78
      2021716.77     13441241.71
#Sta/Elev= 30
    3284  429.53    3760  419.25  3908.1  419.14  3941.9   413.6  3956.8   418.1
  3978.9  413.67  4003.9  415.19  4297.6  408.47  4408.7  403.06  4746.4  394.84
  4816.9  386.29  4854.4  387.32  4876.6   381.6  4903.6  378.81  4970.8  381.68
  4981.8  380.48  4986.5   372.1    4995   370.1  5026.3   372.1  5026.6  380.81
  5029.4  381.41  5098.4  377.08  5196.2  392.57  5339.3  399.88    5919  400.22
  6311.7  406.46  6681.9  398.56    7201  408.46  7579.8  423.31  7949.7  427.98
#Mann= 5 ,-1 , 0
    3284      .1       0  4816.9     .12       0  4986.5     .07       0
  5026.3     .12       0  5196.2      .1       0
Bank Sta=4986.5,5026.3
XS Rating Curve= 0 ,0
Exp/Cntr=0.3,0.1

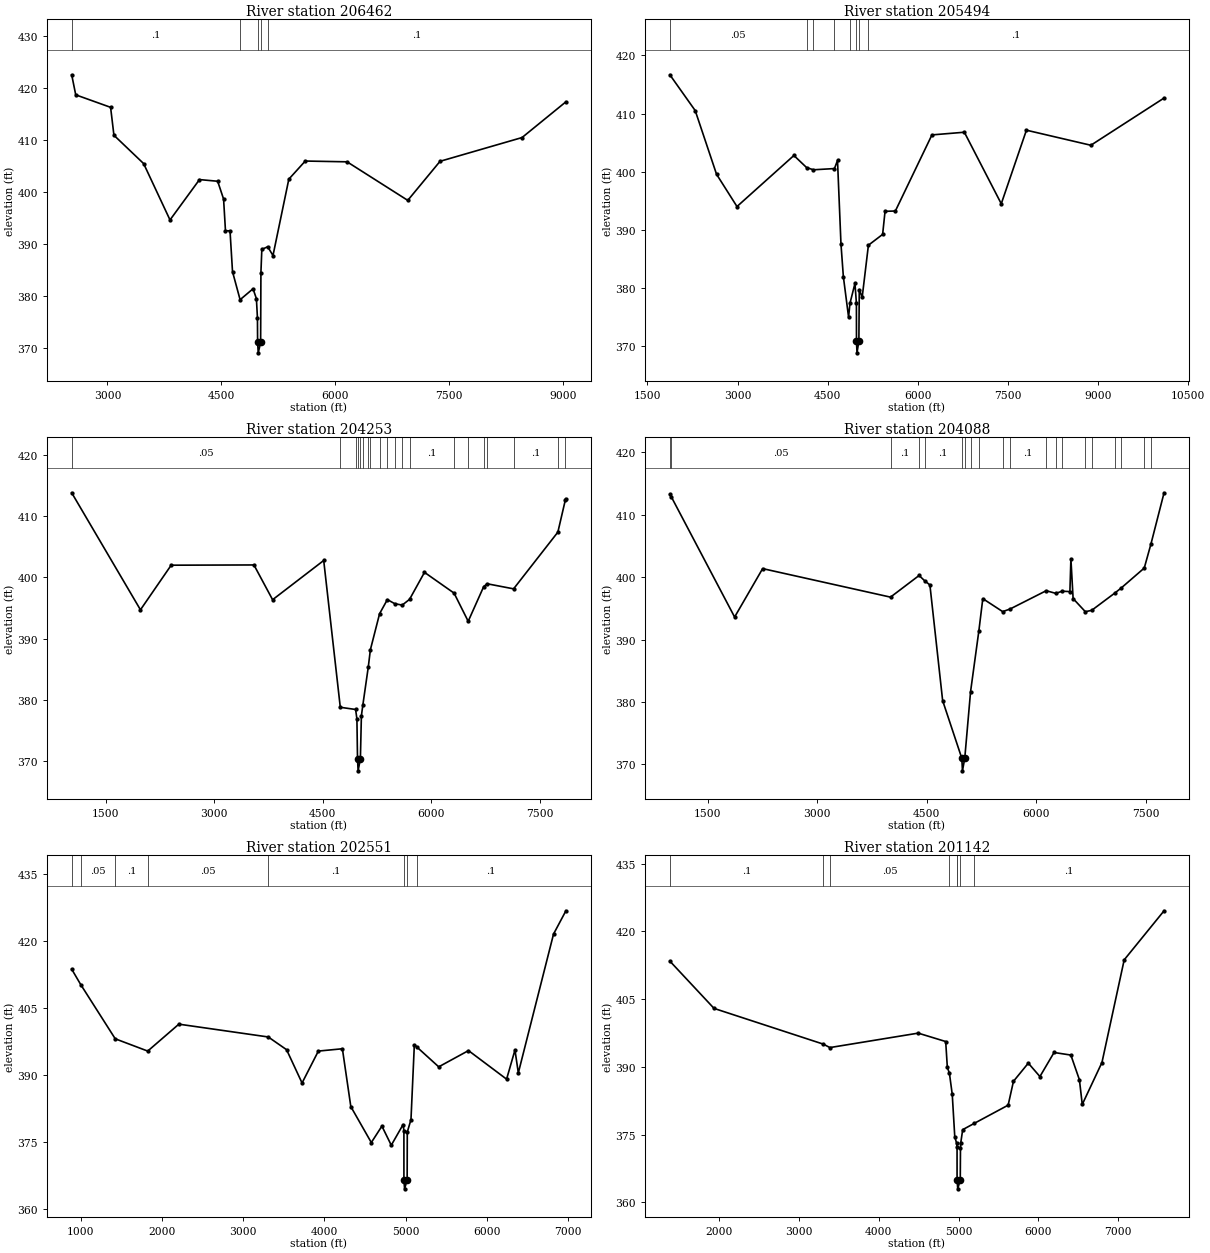
Type RM Length L Ch R = 1 ,206462  ,968,968,968
BEGIN DESCRIPTION:
San Miguel Creek 76.0
END DESCRIPTION:
XS GIS Cut Line= 3
      2026078.78     13443494.32      2024907.47      13441319.7
      2021065.76     13440082.87
#Sta/Elev= 30
    2530   422.5  2583.2  418.65  3042.2  416.25    3086  410.89    3477  405.45
  3824.2  394.63  4212.3  402.38  4451.6  402.06  4529.5  398.64  4554.3  392.57
  4614.3  392.53  4647.1   384.7  4746.9  379.32  4917.3  381.42  4961.5  379.52
  4975.3  375.82  4977.3  371.12  4985.7  369.12  5017.1  371.12    5021  384.53
  5032.9  388.97  5110.3  389.49  5179.8   387.8  5388.3  402.46  5604.7  405.94
  6155.2  405.79    6954  398.39    7379  405.89  8458.4  410.45  9035.9  417.31
#Mann= 5 ,-1 , 0
    2530      .1       0  4746.9     .12       0  4977.3     .07       0
  5017.1     .12       0  5110.3      .1       0
Bank Sta=4977.3,5017.1
XS Rating Curve= 0 ,0
Exp/Cntr=0.3,0.1

Type RM Length L Ch R = 1 ,205494  ,1241,1241,1241
BEGIN DESCRIPTION:
Mapping XS 41099c76
END DESCRIPTION:
XS GIS Cut Line= 5
      2026572.22     13443356.57      2025944.33     13440850.89
      2025483.17     13440562.06      2024072.22     13439749.79
      2020674.44      13439046.8
#Sta/Elev= 30
  1872.7  416.67  2295.1  410.51  2650.1  399.56  2990.2  394.01  3937.5  402.79
  4148.2  400.72  4261.5  400.33  4612.4  400.54  4663.2  401.94  4720.9  387.55
  4760.4  381.97  4847.4     375  4870.5  377.36  4953.6  380.79  4977.9  377.34
    4979  370.85  4987.5  368.85  5018.8  370.85  5025.5  379.73  5073.6  378.39
  5177.4  387.36  5414.1  389.22  5454.4  393.19  5626.1  393.24  6234.7  406.33
  6774.2  406.79  7388.5  394.49  7807.2  407.14  8879.5  404.55 10097.8  412.67
#Mann= 8 ,-1 , 0
  1872.7     .05       0  4148.2      .1       0  4261.5     .05       0
  4612.4      .1       0  4870.5     .12       0    4979     .07       0
  5018.8     .12       0  5177.4      .1       0
Bank Sta=4979,5018.8
XS Rating Curve= 0 ,0
Exp/Cntr=0.3,0.1

Type RM Length L Ch R = 1 ,204253  ,165,165,165
BEGIN DESCRIPTION:
Mapping XS bfd0a33a
END DESCRIPTION:
XS GIS Cut Line= 6
      2026778.46     13443268.71      2027070.12     13440803.46
      2026202.07     13439595.13      2026118.73     13439456.24
      2026038.51     13439307.73      2025434.21     13436855.71
#Sta/Elev= 30
    1032  413.85  1981.8   394.7  2406.1     402  3549.2  402.04    3807  396.35
    4513  402.77    4742  378.75  4953.5  378.39  4971.6  376.85  4979.8  370.35
  4988.2  368.35  5019.7  370.35  5033.5  377.36  5053.8  379.14    5129  385.37
  5157.5  388.16  5284.9  394.07  5392.2  396.37  5494.6   395.7    5597  395.47
  5698.6  396.41  5904.9  400.83  6313.7  397.43  6508.6  392.82  6723.3  398.51
  6770.9  398.96  7135.6  398.13  7747.2  407.41  7849.6  412.63  7858.4  412.87
#Mann= 20 ,-1 , 0
    1032     .05       0    4742      .1       0  4953.5     .12       0
  4979.8     .07       0  5019.7     .12       0  5053.8     .05       0
    5129     .12       0  5157.5      .1       0  5284.9     .08       0
  5392.2      .1       0  5494.6     .15       0    5597     .05       0
  5698.6      .1       0  6313.7     .08       0  6508.6      .1       0
  6723.3     .05       0  6770.9      .1       0  7135.6      .1       0
  7747.2     .08       0  7849.6     .05       0
Bank Sta=4979.8,5019.7
XS Rating Curve= 0 ,0
Exp/Cntr=0.3,0.1

Type RM Length L Ch R = 1 ,204088  ,1537,1537,1537
BEGIN DESCRIPTION:
Mapping XS 6762e883
END DESCRIPTION:
XS GIS Cut Line= 5
      2026931.24     13443254.81       2027220.3     13440714.92
       2026347.9     13439530.02      2026191.65     13439334.71
      2025660.06     13436894.67
#Sta/Elev= 30
   977.6  413.26   999.2  412.84  1865.6  393.61  2249.8  401.37  4002.7   396.8
  4394.7  400.27  4470.3  399.43  4542.8  398.75  4717.4  380.22  4980.5  370.97
  4988.9  368.97  5020.4  370.97  5100.3  381.67  5214.5  391.45  5267.9  396.56
  5540.4  394.48    5642   394.9  6137.3  397.83  6269.3   397.4  6353.6  397.75
    6462  397.69  6475.6  402.96  6505.9  396.57  6673.3  394.47  6760.2  394.68
  7077.3  397.45  7166.8  398.28  7481.3  401.46  7573.5  405.34  7752.7  413.52
#Mann= 20 ,-1 , 0
   977.6      .1       0   999.2     .05       0  4002.7      .1       0
  4394.7     .08       0  4470.3      .1       0  4980.5     .07       0
  5020.4      .1       0  5100.3      .1       0  5214.5     .08       0
  5540.4     .05       0    5642      .1       0  6137.3      .1       0
  6269.3     .05       0  6353.6      .1       0  6673.3     .05       0
  6760.2      .1       0  7077.3     .05       0  7166.8      .1       0
  7481.3     .05       0  7573.5      .1       0
Bank Sta=4980.5,5020.4
XS Rating Curve= 0 ,0
Exp/Cntr=0.3,0.1

Type RM Length L Ch R = 1 ,202551  ,1409,1409,1409
BEGIN DESCRIPTION:
San Miguel Creek 75.0
END DESCRIPTION:
XS GIS Cut Line= 4
      2027104.84     13443268.75      2027417.93     13440991.22
       2027540.8     13439184.54      2028025.01     13437274.97
#Sta/Elev= 30
   890.2  413.73  1000.8  410.29    1426  398.13  1825.6  395.38  2208.7  401.41
  3308.2  398.54  3533.7  395.69  3724.1  388.23  3924.6  395.38  4220.2   395.9
    4324  382.94  4576.1  374.89  4706.4  378.57  4821.6  374.29    4967  378.92
    4977  377.57  4977.1  366.52  4985.5  364.52    5017  366.52  5018.6  377.24
    5064  380.03  5105.3  396.77  5133.4  396.34  5405.3  391.85  5771.5  395.49
  6240.2  389.09  6343.2  395.62  6384.5  390.49  6817.8   421.6    6970  426.81
#Mann= 8 ,-1 , 0
   890.2      .1       0  1000.8     .05       0    1426      .1       0
  1825.6     .05       0  3308.2      .1       0  4977.1     .07       0
    5017      .1       0  5133.4      .1       0
Bank Sta=4977.1,5017
XS Rating Curve= 0 ,0
Exp/Cntr=0.3,0.1

Type RM Length L Ch R = 1 ,201142  ,1333,1333,1333
BEGIN DESCRIPTION:
San Miguel Creek 74.0
END DESCRIPTION:
XS GIS Cut Line= 3
      2027523.04     13443540.06      2028449.84     13440041.23
      2028966.18     13437517.91
#Sta/Elev= 30
  1380.5  413.43  1934.5  402.95  3304.6  395.03    3387  394.27  4493.7  397.47
  4838.3  395.61    4859  389.89  4885.1  388.56  4920.5  383.91  4952.1  374.53
    4975  373.09  4980.8  372.21  4981.1  364.97  4989.5  362.97    5021  364.97
  5023.7  371.99  5026.3  373.05  5051.5  376.08  5193.8  377.45  5621.3  381.51
  5687.7  386.79  5873.9  390.82  6019.4  387.85  6196.7  393.18  6407.3  392.61
  6514.5  387.14  6550.2  381.67  6797.1  390.96  7075.9  413.71  7575.6  424.58
#Mann= 8 ,-1 , 0
  1380.5      .1       0  3304.6     .08       0    3387     .05       0
  4885.1      .1       0    4975     .12       0  4981.1     .07       0
    5021     .12       0  5193.8      .1       0
Bank Sta=4981.1,5021
XS Rating Curve= 0 ,0
Exp/Cntr=0.3,0.1

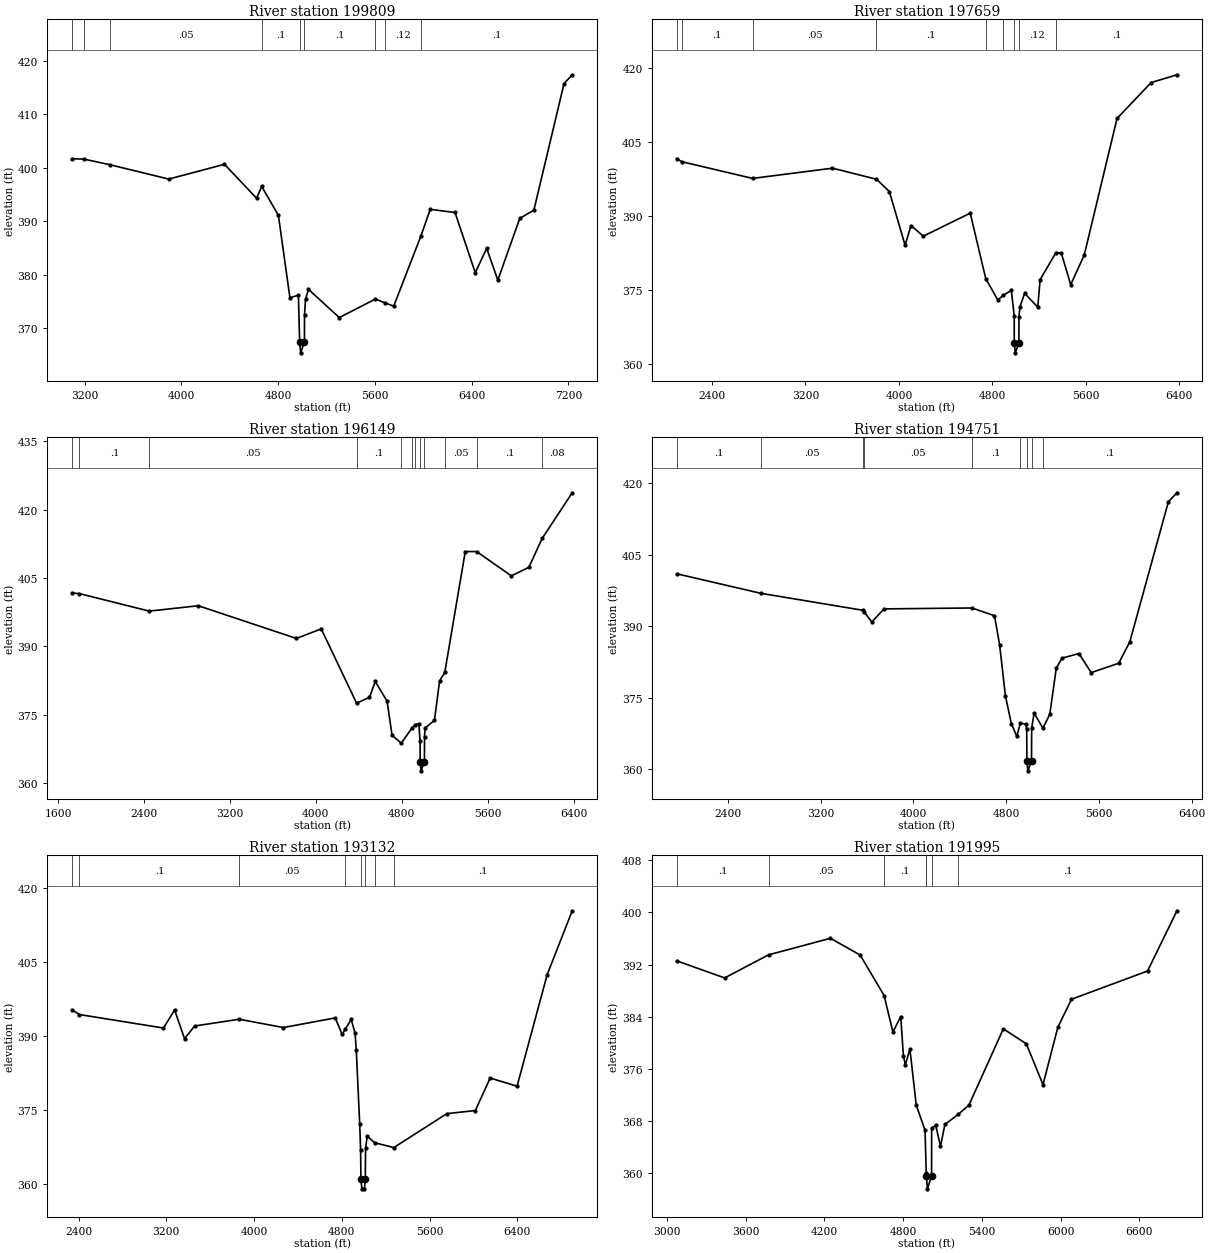
Type RM Length L Ch R = 1 ,199809  ,2150,2150,2150
BEGIN DESCRIPTION:
San Miguel Creek 73.0
END DESCRIPTION:
XS GIS Cut Line= 3
      2029771.51     13442116.01       2029650.8     13440214.54
      2029165.82     13438036.58
#Sta/Elev= 30
  3094.7   401.7  3193.8  401.63  3408.4  400.58  3894.8   397.9  4355.7  400.66
  4621.3  394.32  4663.8  396.52  4801.6  391.12  4896.8  375.73    4967  376.21
  4977.1  367.45  4985.5  365.45    5017  367.45  5017.5  372.56  5025.9  375.46
  5050.2  377.31  5304.8  372.04  5603.8  375.49  5679.5  374.82  5755.1  374.16
  5979.4  387.23  6057.3  392.25  6262.2  391.66  6429.3  380.42    6524  384.96
  6616.1  379.03  6797.8  390.57  6914.2   392.1  7163.6  415.74  7231.3  417.38
#Mann= 9 ,-1 , 0
  3094.7     .05       0  3193.8      .1       0  3408.4     .05       0
  4663.8      .1       0  4977.1     .07       0    5017      .1       0
  5603.8      .1       0  5679.5     .12       0  5979.4      .1       0
Bank Sta=4977.1,5017
XS Rating Curve= 0 ,0
Exp/Cntr=0.3,0.1

Type RM Length L Ch R = 1 ,197659  ,1510,1510,1510
BEGIN DESCRIPTION:
San Miguel Creek 72.0
END DESCRIPTION:
XS GIS Cut Line= 4
      2029894.98     13442133.86      2030537.35     13440432.44
       2030640.8     13439354.54      2030806.43     13437984.71
#Sta/Elev= 30
  2098.5   401.6    2140  400.97  2747.2  397.58  3431.3  399.65  3808.1  397.41
  3918.4  394.92  4052.7  384.06  4103.7  388.04  4208.7   385.9  4610.3  390.55
  4743.3   377.3  4846.3     373  4892.1  373.92  4961.9  374.94    4987  369.78
  4987.1   364.3  4995.6   362.3    5027   364.3  5027.2  369.49  5034.9  371.55
  5075.9  374.34  5188.4  371.55  5208.5  377.09  5343.4  382.57  5389.9  382.48
  5470.4  376.08  5586.3  382.09  5866.9  409.71  6158.8  416.97  6379.8  418.54
#Mann= 9 ,-1 , 0
  2098.5     .05       0    2140      .1       0  2747.2     .05       0
  3808.1      .1       0  4743.3     .16       0  4892.1     .12       0
  4987.1     .07       0    5027     .12       0  5343.4      .1       0
Bank Sta=4987.1,5027
XS Rating Curve= 0 ,0
Exp/Cntr=0.3,0.1

Type RM Length L Ch R = 1 ,196149  ,1398,1398,1398
BEGIN DESCRIPTION:
San Miguel Creek 71.0
END DESCRIPTION:
XS GIS Cut Line= 3
      2029981.78     13442211.98       2031980.8     13439624.54
      2032359.91     13438289.63
#Sta/Elev= 30
  1730.3  401.71  1799.9  401.57    2449  397.74  2906.5  398.91  3819.5  391.75
  4050.8  393.84  4379.8  377.57    4500  378.82  4553.9  382.31    4664  377.99
  4710.6  370.49  4796.8   368.8  4896.8  372.16  4926.9  372.86  4959.7  373.07
    4971  369.26  4971.9  364.73  4980.3  362.73  5011.8  364.73  5012.5  370.22
  5017.8   372.1  5105.2  373.81  5152.9  382.44    5201   384.3  5391.9  410.79
  5498.4  410.78  5820.7  405.46  5983.6  407.32  6108.3  413.68  6387.7  423.67
#Mann= 12 ,-1 , 0
  1730.3     .05       0  1799.9      .1       0    2449     .05       0
  4379.8      .1       0  4796.8     .12       0  4896.8      .1       0
  4926.9     .12       0  4971.9     .07       0  5011.8     .12       0
    5201     .05       0  5498.4      .1       0  6108.3     .08       0
Bank Sta=4971.9,5011.8
XS Rating Curve= 0 ,0
Exp/Cntr=0.3,0.1

Type RM Length L Ch R = 1 ,194751  ,1619,1619,1619
BEGIN DESCRIPTION:
San Miguel Creek 70.0
END DESCRIPTION:
XS GIS Cut Line= 3
      2030155.45     13442203.25       2032770.8     13440654.54
      2033713.77     13439799.36
#Sta/Elev= 30
  1960.5  400.96  2685.2  396.87  3570.1  393.29  3578.2  392.92  3642.1  390.85
  3746.8   393.6  4505.2  393.79  4699.8  392.17  4743.7  386.11  4794.4  375.31
  4845.1  369.52  4892.8  366.85  4921.8  369.61  4969.8  369.46  4977.6  368.33
  4979.1  361.64  4987.6  359.64    5019  361.64  5020.4   368.6  5041.7  371.74
  5116.9  368.58  5176.2  371.47  5232.6  381.18  5282.3  383.28  5427.5  384.24
  5533.7  380.24  5770.9   382.2  5866.3  386.68    6199  416.08    6273  417.95
#Mann= 9 ,-1 , 0
  1960.5      .1       0  2685.2     .05       0  3570.1      .1       0
  3578.2     .05       0  4505.2      .1       0  4921.8     .12       0
  4979.1     .07       0    5019     .12       0  5116.9      .1       0
Bank Sta=4979.1,5019
XS Rating Curve= 0 ,0
Exp/Cntr=0.3,0.1

Type RM Length L Ch R = 1 ,193132  ,1137,1137,1137
BEGIN DESCRIPTION:
San Miguel Creek 69.0
END DESCRIPTION:
XS GIS Cut Line= 3
      2033323.81     13444451.55       2033740.8     13441824.54
        2033825.       13439925.
#Sta/Elev= 30
  2340.1  395.29  2408.2  394.34  3174.4   391.6  3275.7  395.28  3366.3  389.43
    3458  392.01  3864.7  393.39    4268   391.7  4740.5  393.66  4802.8  390.31
  4831.7  391.35  4885.6  393.34  4921.1   390.6  4932.4  387.13  4963.6  372.09
  4971.7   366.9  4974.7  360.92  4983.2  358.92  5006.2  358.92  5014.6  360.92
  5017.1  367.15  5032.1  369.62  5100.7  368.28  5274.6  367.31  5757.8   374.2
    6018  374.83  6153.2  381.44  6398.4  379.78  6673.4  402.48  6901.4  415.43
#Mann= 8 ,-1 , 0
  2340.1     .05       0  2408.2      .1       0  3864.7     .05       0
  4831.7      .1       0  4974.7     .07       0  5014.6      .1       0
  5100.7     .12       0  5274.6      .1       0
Bank Sta=4974.7,5014.6
XS Rating Curve= 0 ,0
Exp/Cntr=0.3,0.1

Type RM Length L Ch R = 1 ,191995  ,875,875,875
BEGIN DESCRIPTION:
Mapping XS ff27b672
END DESCRIPTION:
XS GIS Cut Line= 4
      2034517.56     13443524.58      2034764.96     13442352.71
       2034770.8     13441624.54      2034283.18     13439800.59
#Sta/Elev= 30
  3074.1  392.57  3439.1  389.95  3773.8  393.49  4245.9  396.03    4472  393.47
  4655.2  387.25    4722  381.65    4782  384.02    4802  378.05    4817  376.61
    4852  379.02    4900  370.45    4967  366.59  4976.5  360.02  4977.1   359.6
  4985.5   357.6    5017   359.6  5017.6  366.89  5048.7  367.33  5084.9  364.13
  5118.9  367.48  5220.6  369.03  5302.3  370.46  5564.1  382.14  5739.2  379.85
  5866.4  373.58  5980.3  382.42  6083.8  386.68  6663.5  391.01    6888  400.25
#Mann= 7 ,-1 , 0
  3074.1      .1       0  3773.8     .05       0  4655.2      .1       0
  4976.5     .12       0  4977.1     .07       0    5017     .12       0
  5220.6      .1       0
Bank Sta=4977.1,5017
XS Rating Curve= 0 ,0
Exp/Cntr=0.3,0.1