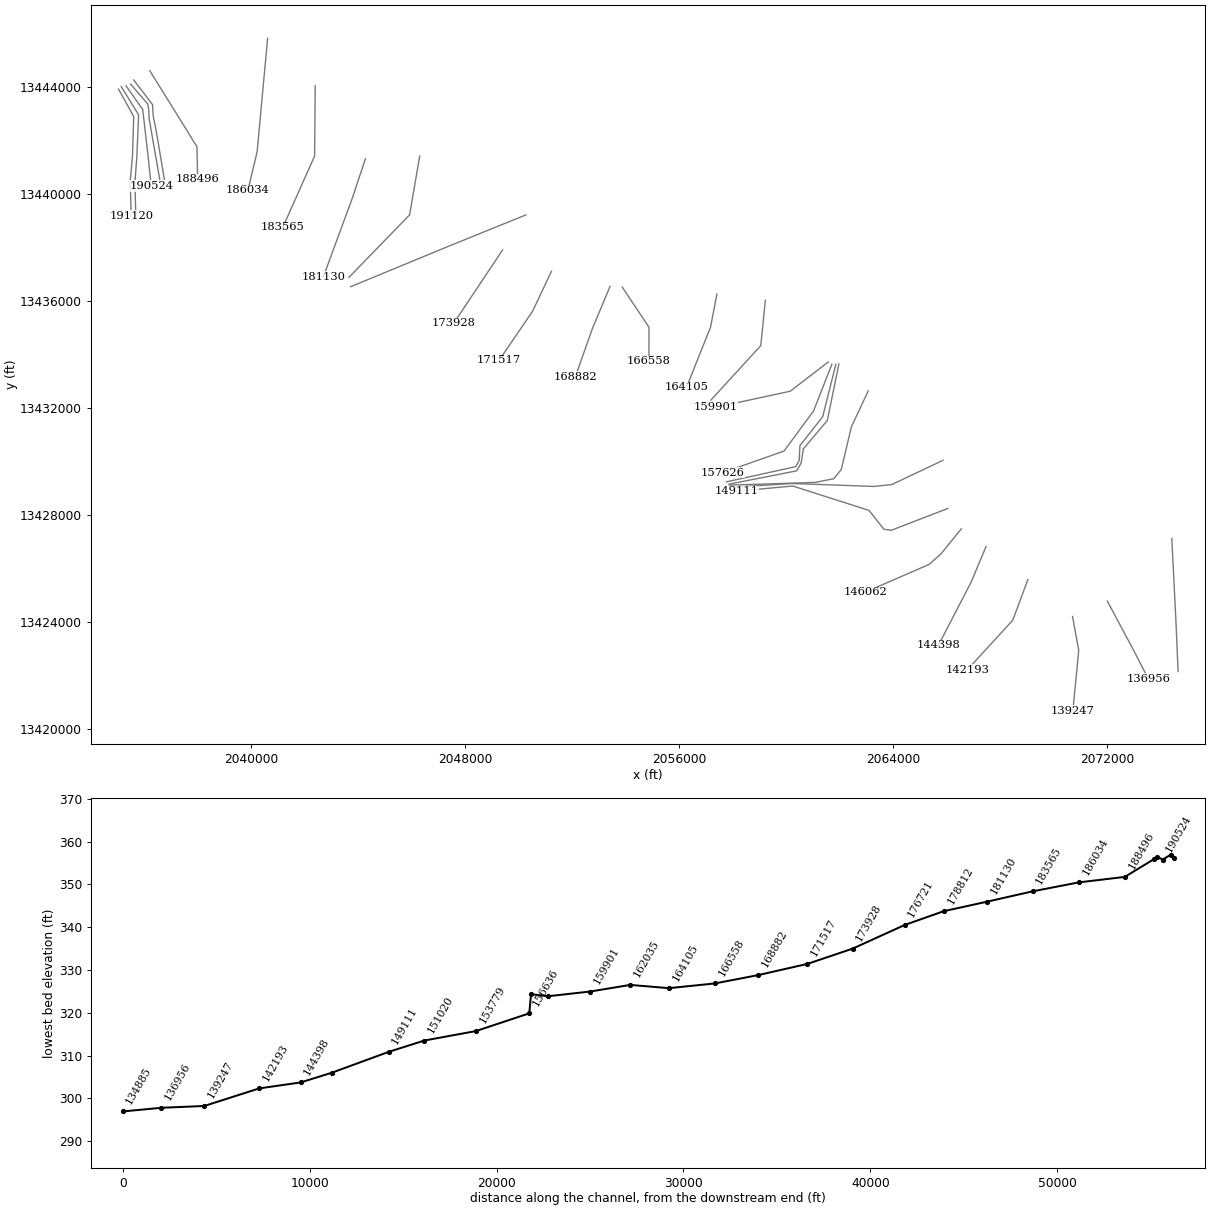
HEC-RAS study San Miguel Creek.prj: San Miguel Creek Base Level Engineering

--- San Miguel Creek.g01 (geometry) --- (continued)

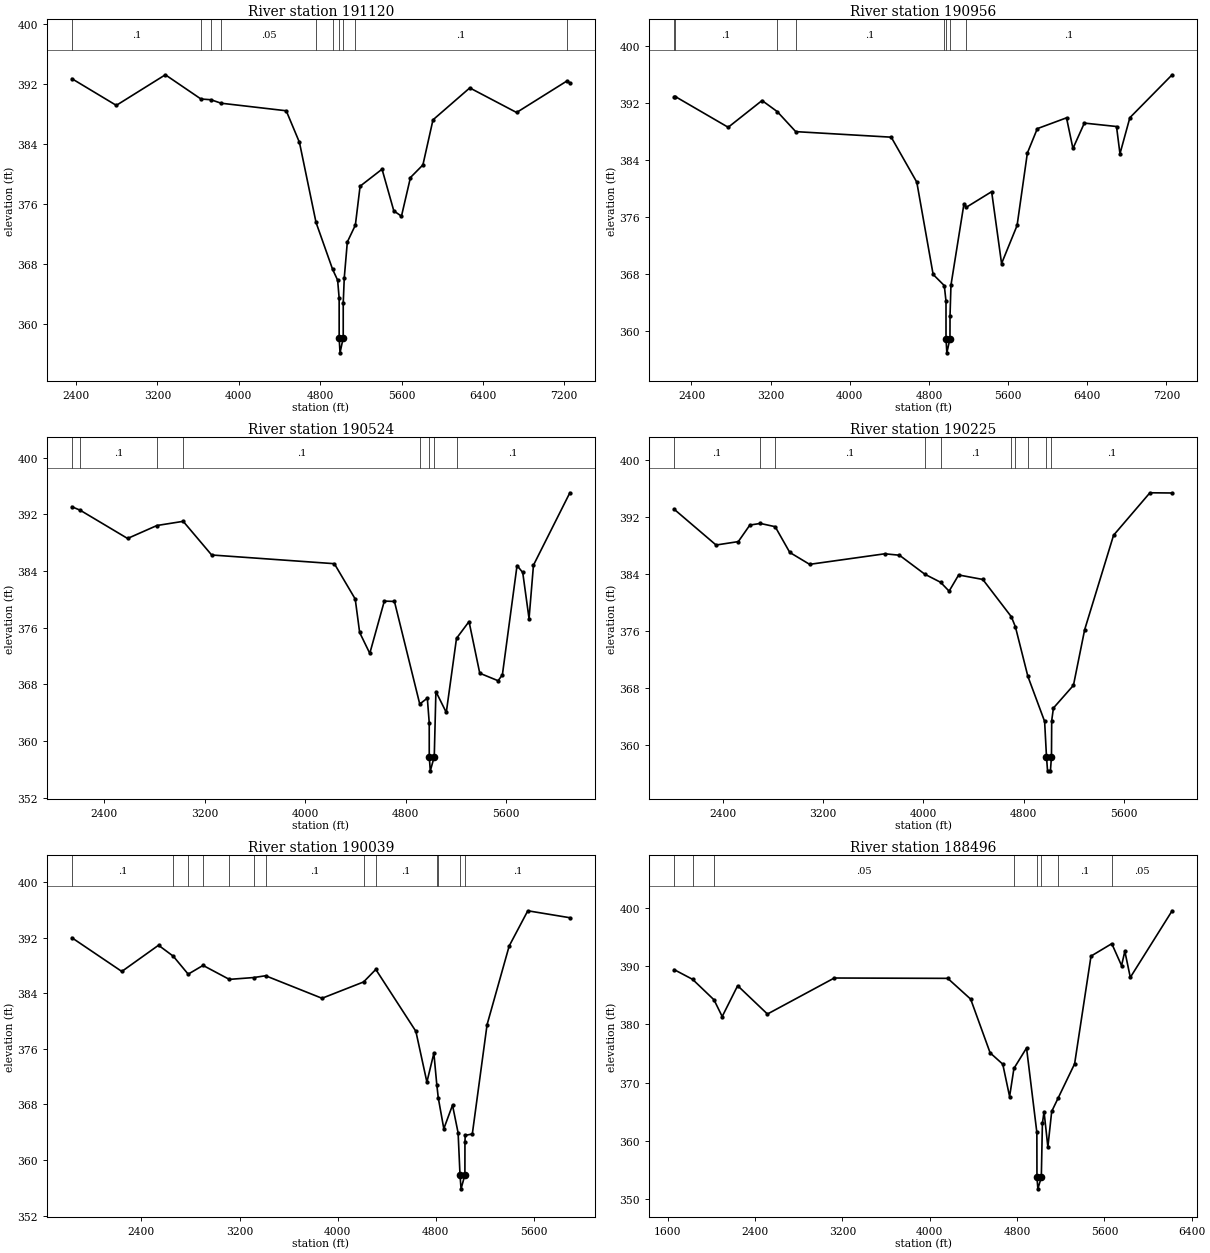
Type RM Length L Ch R = 1 ,191120  ,164,164,164
BEGIN DESCRIPTION:
San Miguel Creek 68.0
END DESCRIPTION:
XS GIS Cut Line= 5
      2035042.73      13443926.5      2035612.18     13442902.19
      2035567.04     13441434.54      2035480.23      13440475.1
      2035518.41     13439184.22
#Sta/Elev= 30
  2359.7  392.69  2796.4  389.13  3278.5  393.21  3628.4  389.98  3727.1  389.88
  3825.9  389.42  4466.8  388.41  4596.8  384.19  4759.7  373.52  4922.5  367.27
    4972  365.82    4987  363.42  4987.1  358.13  4995.6  356.13    5027  358.13
  5027.1  362.77  5037.2  366.12  5067.3  370.91  5146.3  373.16  5192.8  378.35
  5408.6  380.62  5524.4  375.06  5599.5  374.35  5687.9  379.51  5810.3  381.19
  5909.4   387.2  6271.1  391.46  6731.3  388.18  7222.3  392.35  7254.8  392.14
#Mann= 10 ,-1 , 0
  2359.7      .1       0  3628.4     .05       0  3727.1     .08       0
  3825.9     .05       0  4759.7      .1       0  4922.5     .12       0
  4987.1     .07       0    5027     .12       0  5146.3      .1       0
  7222.3     .05       0
Bank Sta=4987.1,5027
XS Rating Curve= 0 ,0
Exp/Cntr=0.3,0.1

Type RM Length L Ch R = 1 ,190956  ,432,432,432
BEGIN DESCRIPTION:
San Miguel Creek 67.0
END DESCRIPTION:
XS GIS Cut Line= 5
      2035143.43      13444024.3      2035794.47     13442965.27
       2035730.8     13441434.54      2035657.32     13440440.38
       2035690.3     13439180.58
#Sta/Elev= 30
  2224.8  392.94  2236.4  392.95  2770.9  388.63    3113  392.39  3266.3  390.84
  3453.4  388.02  4418.4  387.24  4676.8  380.92  4841.9  367.95  4954.8  366.38
    4972  364.18  4972.1  358.93  4980.5  356.93    5012  358.93  5012.7  362.17
  5022.1  366.44  5152.5  377.79  5178.6   377.4  5433.2  379.58  5533.5  369.48
  5690.3  374.83  5794.2  385.01  5894.8  388.44  6189.8  389.96  6254.8  385.65
  6369.9  389.22    6695  388.74    6730  384.91    6830  389.98  7257.1  396.01
#Mann= 8 ,-1 , 0
  2224.8     .05       0  2236.4      .1       0  3266.3     .05       0
  3453.4      .1       0  4954.8     .12       0  4972.1     .07       0
    5012     .12       0  5178.6      .1       0
Bank Sta=4972.1,5012
XS Rating Curve= 0 ,0
Exp/Cntr=0.3,0.1

Type RM Length L Ch R = 1 ,190524  ,299,299,299
BEGIN DESCRIPTION:
Mapping XS a436087f
END DESCRIPTION:
XS GIS Cut Line= 4
      2035322.88     13444050.49       2035947.9     13443168.51
       2036150.8     13441404.54      2036265.55     13440304.51
#Sta/Elev= 30
  2143.4  393.08  2210.2  392.58  2586.7   388.6  2820.4  390.43  3029.1  391.02
  3255.6  386.27    4232  385.04  4398.1  380.05  4433.3  375.33    4514  372.38
  4629.6  379.76  4710.1  379.71  4911.5  365.23  4971.9  366.06    4987  362.58
  4987.1   357.8  4995.6   355.8    5027   357.8  5040.1  366.99  5122.7  364.04
    5204   374.5  5303.7  376.87  5389.1  369.58  5534.9  368.52  5569.1  369.35
  5685.7  384.78    5731   383.8  5781.3  377.29  5816.4  384.83    6106  395.05
#Mann= 8 ,-1 , 0
  2143.4     .05       0  2210.2      .1       0  2820.4     .05       0
  3029.1      .1       0  4911.5     .12       0  4987.1     .07       0
    5027     .12       0    5204      .1       0
Bank Sta=4987.1,5027
XS Rating Curve= 0 ,0
Exp/Cntr=0.3,0.1

Type RM Length L Ch R = 1 ,190225  ,186,186,186
BEGIN DESCRIPTION:
Mapping XS ef023e6a
END DESCRIPTION:
XS GIS Cut Line= 6
      2035499.32     13444111.11      2036141.69     13443364.57
      2036176.42     13443112.84       2036185.1     13442843.74
      2036332.67     13441993.04      2036610.23     13440414.18
#Sta/Elev= 30
  2010.3  393.12  2344.9   388.1  2522.3  388.58  2614.5   390.9  2698.5  391.13
  2816.8  390.67  2933.2  387.06  3091.6  385.39  3691.6  386.87  3808.5  386.67
  4011.5     384  4136.4  382.88  4204.9  381.63    4281   383.9  4473.9  383.27
  4701.9  378.03  4734.1  376.62  4833.7  369.67  4967.3  363.35  4982.1  358.42
  4990.6  356.42  5013.6  356.42    5022  358.42  5023.8  363.47  5037.6  365.23
  5197.4  368.42  5286.8  376.22  5517.5  389.47  5807.7  395.43    5985   395.4
#Mann= 10 ,-1 , 0
  2010.3      .1       0  2698.5     .05       0  2816.8      .1       0
  4011.5     .08       0  4136.4      .1       0  4701.9     .05       0
  4734.1     .08       0  4833.7      .1       0  4982.1     .07       0
    5022      .1       0
Bank Sta=4982.1,5022
XS Rating Curve= 0 ,0
Exp/Cntr=0.3,0.1

Type RM Length L Ch R = 1 ,190039  ,1543,1543,1543
BEGIN DESCRIPTION:
Mapping XS a3a9e864
END DESCRIPTION:
XS GIS Cut Line= 6
      2035612.16     13444267.38       2036315.3     13443347.21
      2036341.35     13442913.18      2036428.15     13442487.84
      2036523.64     13441949.64      2036768.57     13440484.58
#Sta/Elev= 30
  1833.7  391.98  2240.7  387.13  2539.9   390.9  2660.4  389.32  2781.7  386.74
  2902.9     388  3116.8  385.99  3314.1  386.25  3412.7  386.51  3872.5  383.27
  4211.4  385.62    4311  387.42  4637.5  378.52  4727.5  371.21  4784.3  375.37
  4808.3  370.81  4820.1  368.95  4865.3   364.5  4936.2  367.89  4981.9   363.9
  4997.3  357.85  5005.8  355.85  5037.2  357.85  5037.6  362.64  5040.1  363.54
  5097.7  363.75    5218  379.48  5398.3   390.8  5549.9  395.86  5892.7  394.86
#Mann= 13 ,-1 , 0
  1833.7      .1       0  2660.4     .08       0  2781.7      .1       0
  2902.9     .08       0  3116.8      .1       0  3314.1     .08       0
  3412.7      .1       0  4211.4     .08       0    4311      .1       0
  4808.3     .08       0  4820.1      .1       0  4997.3     .07       0
  5037.2      .1       0
Bank Sta=4997.3,5037.2
XS Rating Curve= 0 ,0
Exp/Cntr=0.3,0.1

Type RM Length L Ch R = 1 ,188496  ,2462,2462,2462
BEGIN DESCRIPTION:
San Miguel Creek 66.0
END DESCRIPTION:
XS GIS Cut Line= 3
      2036212.92     13444614.06        2037975.       13441775.
       2038002.8     13440554.35
#Sta/Elev= 30
  1658.1   389.4  1827.1  387.73  2023.3  384.21  2098.3  381.34    2240  386.64
  2512.8  381.77  3125.2  387.96  4164.5   387.9  4374.8  384.33  4553.1   375.1
  4668.8  373.16  4731.4  367.59    4771  372.42  4886.7  375.94  4981.2  361.42
  4982.1  353.74  4990.5  351.74    5022  353.74    5032  362.99    5047  364.99
  5082.1  358.93  5117.1  365.04    5177  367.37  5327.1  373.22  5477.2  391.72
  5667.6  393.86  5757.2  390.09  5787.2  392.56  5837.3  388.06  6220.5  399.51
#Mann= 8 ,-1 , 0
  1658.1     .05       0  1827.1     .08       0  2023.3     .05       0
    4771      .1       0  4982.1     .07       0    5022      .1       0
    5177      .1       0  5667.6     .05       0
Bank Sta=4982.1,5022
XS Rating Curve= 0 ,0
Exp/Cntr=0.3,0.1

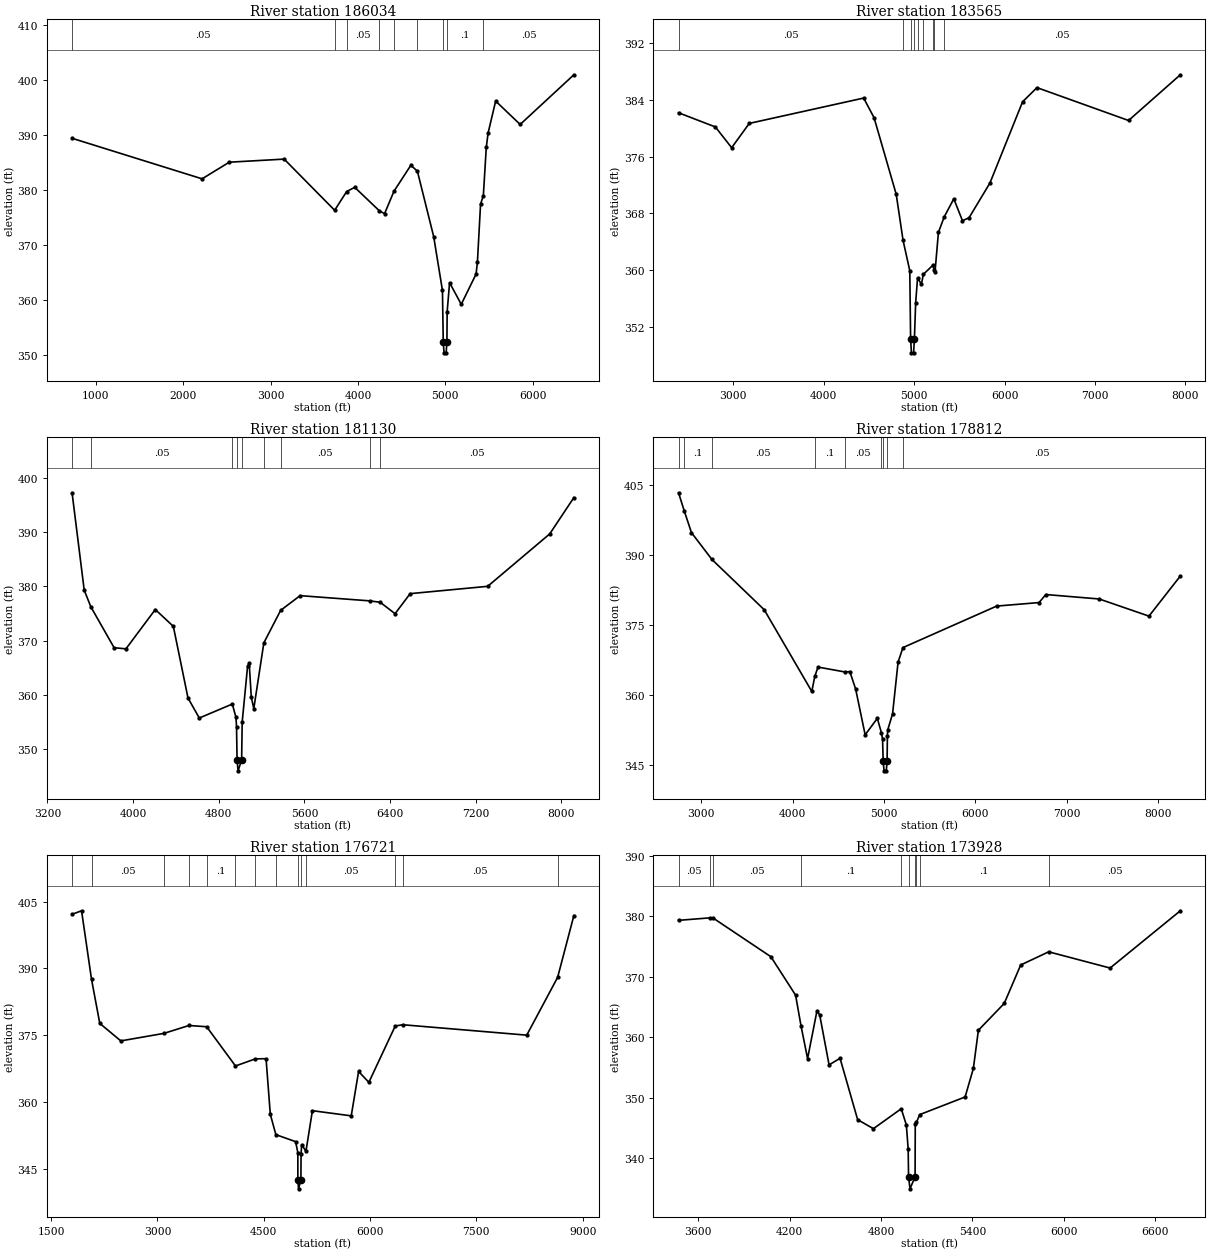
Type RM Length L Ch R = 1 ,186034  ,2469,2469,2469
BEGIN DESCRIPTION:
San Miguel Creek 65.0
END DESCRIPTION:
XS GIS Cut Line= 3
      2040618.31     13445829.38        2040225.       13441575.
      2039880.63     13440144.29
#Sta/Elev= 30
     727  389.41  2215.2  382.05  2526.5  385.07  3154.7  385.63  3732.8  376.34
  3870.1  379.74  3962.6  380.51  4244.2  376.25  4304.1  375.72  4412.3  379.81
  4605.4  384.52  4680.1  383.43  4866.5  371.56  4966.9  361.78    4976  352.46
  4985.1  350.46    5009  350.46  5018.1  352.46  5020.5  357.86  5048.4   363.2
  5182.1  359.27  5351.8  364.76  5367.2  366.95  5403.1  377.46  5434.9     379
  5468.5  387.75  5489.5  390.38    5576  396.17  5856.3  391.92  6471.1  400.94
#Mann= 9 ,-1 , 0
     727     .05       0  3732.8      .1       0  3870.1     .05       0
  4244.2      .1       0  4412.3     .05       0  4680.1      .1       0
    4976     .07       0  5018.1      .1       0  5434.9     .05       0
Bank Sta=4976,5018.1
XS Rating Curve= 0 ,0
Exp/Cntr=0.3,0.1

Type RM Length L Ch R = 1 ,183565  ,2435,2435,2435
BEGIN DESCRIPTION:
San Miguel Creek 64.0
END DESCRIPTION:
XS GIS Cut Line= 4
      2042397.82     13444049.84      2042382.16     13442248.55
        2042375.       13441425.      2041182.62     13438754.88
#Sta/Elev= 30
  2394.6  382.19    2802  380.19    2982  377.27    3177  380.69  4441.9  384.26
    4557  381.49    4802   370.7  4877.3  364.24    4952  359.93    4961  350.37
    4970  348.37    4994  348.37  5003.1  350.37    5017  355.45  5038.2  358.93
  5080.3  358.03    5102  359.43  5205.7  360.69  5223.5  360.01  5230.5  359.71
  5268.7  365.34    5333  367.53  5438.8  370.07  5534.4  366.99  5606.8  367.39
  5838.2  372.29  6199.6  383.74  6358.6  385.73  7371.3   381.1  7943.8  387.54
#Mann= 9 ,-1 , 0
  2394.6     .05       0  4877.3      .1       0    4961     .07       0
  5003.1      .1       0  5038.2     .12       0    5102      .1       0
  5205.7     .07       0  5223.5      .1       0    5333     .05       0
Bank Sta=4961,5003.1
XS Rating Curve= 0 ,0
Exp/Cntr=0.3,0.1

Type RM Length L Ch R = 1 ,181130  ,2318,2318,2318
BEGIN DESCRIPTION:
San Miguel Creek 63.0
END DESCRIPTION:
XS GIS Cut Line= 3
      2044274.99     13441324.97        2043775.       13439825.
      2042701.63     13436910.05
#Sta/Elev= 30
  3429.9  397.29  3543.2  379.33  3604.9  376.25  3822.5  368.69  3933.2  368.48
  4207.3  375.74  4375.9  372.63  4512.9   359.4  4618.4  355.71  4926.8  358.29
  4960.9  355.82  4966.2  354.13  4971.3  347.96  4980.5  345.96  5013.8  347.96
    5019  354.96  5069.3  365.23  5084.5   365.8  5104.2  359.54  5127.5  357.46
  5221.3  369.58  5378.5  375.59  5560.3   378.3  6208.7  377.34  6308.2  377.08
    6447  374.97  6588.2  378.67  7312.2  380.02    7892   389.7  8117.3   396.4
#Mann= 9 ,-1 , 0
  3429.9      .1       0  3604.9     .05       0  4926.8     .12       0
  4971.3     .07       0  5013.8     .12       0  5221.3      .1       0
  5378.5     .05       0  6208.7     .08       0  6308.2     .05       0
Bank Sta=4971.3,5013.8
XS Rating Curve= 0 ,0
Exp/Cntr=0.3,0.1

Type RM Length L Ch R = 1 ,178812  ,2091,2091,2091
BEGIN DESCRIPTION:
San Miguel Creek 62.0
END DESCRIPTION:
XS GIS Cut Line= 3
      2046304.07     13441423.98        2045925.       13439225.
      2043656.49     13436888.36
#Sta/Elev= 30
  2753.4  403.23  2814.6  399.43  2894.8   394.7  3118.7  388.96  3690.4  378.21
  4211.1  360.72  4243.8  363.97    4279  365.94  4571.4   364.9  4627.1  364.96
  4690.5  361.24  4794.5  351.44  4927.5  354.97    4973  351.84  4984.8  350.53
  4991.8  345.74  5001.1  343.74  5025.2  343.74  5034.4  345.74  5037.8  351.24
  5041.4   352.5  5094.4  355.94  5154.6  367.02    5208  370.11    6233  378.99
  6696.2  379.74  6770.5  381.46  7353.9  380.51  7898.4  376.84  8241.5  385.42
#Mann= 9 ,-1 , 0
  2753.4     .05       0  2814.6      .1       0  3118.7     .05       0
  4243.8      .1       0  4571.4     .05       0    4973      .1       0
  4991.8     .07       0  5034.4      .1       0    5208     .05       0
Bank Sta=4991.8,5034.4
XS Rating Curve= 0 ,0
Exp/Cntr=0.3,0.1

Type RM Length L Ch R = 1 ,176721  ,2793,2793,2793
BEGIN DESCRIPTION:
San Miguel Creek 61.0
END DESCRIPTION:
XS GIS Cut Line= 3
      2050275.03     13439225.01      2047304.58      13438019.9
      2043721.76     13436540.59
#Sta/Elev= 30
  1794.4  402.17  1928.4  402.96  2068.9  387.57  2185.6  377.67  2482.4  373.74
  3091.1  375.43    3444   377.2  3693.9  376.92  4100.6  368.11  4382.6  369.71
  4532.2  369.74  4592.2  357.25  4670.6  352.69  4948.8  351.12  4980.7  348.65
  4981.1  342.52  4990.4  340.52  5023.8  342.52  5026.3  348.41  5034.7  350.44
  5095.3  348.96  5186.2  358.07  5734.3  356.91  5838.1  366.87  5983.2  364.44
  6355.2  377.08  6460.2  377.37  8211.2  375.03  8647.1  388.01  8876.2  401.87
#Mann= 14 ,-1 , 0
  1794.4      .1       0  2068.9     .05       0  3091.1      .1       0
    3444     .05       0  3693.9      .1       0  4100.6     .05       0
  4382.6      .1       0  4670.6     .05       0  4981.1     .07       0
  5023.8     .05       0  5095.3     .05       0  6355.2     .08       0
  6460.2     .05       0  8647.1      .1       0
Bank Sta=4981.1,5023.8
XS Rating Curve= 0 ,0
Exp/Cntr=0.3,0.1

Type RM Length L Ch R = 1 ,173928  ,2411,2411,2411
BEGIN DESCRIPTION:
San Miguel Creek 60.0
END DESCRIPTION:
XS GIS Cut Line= 3
      2049404.45     13437916.98        2048575.       13436675.
      2047574.98     13435174.97
#Sta/Elev= 30
  3469.9  379.34  3675.5  379.75  3697.5  379.71  4076.5  373.33  4238.9  366.98
  4274.5  361.91  4317.6   356.5  4379.2  364.37  4397.2  363.72  4458.8  355.46
  4530.9  356.55  4646.5  346.41  4750.1  344.92  4932.8  348.21  4966.4  345.54
  4978.4  341.56    4981  336.98  4990.3  334.98  5023.8  336.98    5025  345.64
  5032.8  345.95  5053.9  347.24  5352.5  350.16  5406.6  354.87  5439.6  361.18
  5609.4  365.61  5717.5  371.96  5901.5  374.14    6305  371.46  6766.2  380.92
#Mann= 10 ,-1 , 0
  3469.9     .05       0  3675.5      .1       0  3697.5     .05       0
  4274.5      .1       0  4932.8     .07       0    4981     .07       0
  5023.8     .07       0  5032.8     .12       0  5053.9      .1       0
  5901.5     .05       0
Bank Sta=4981,5023.8
XS Rating Curve= 0 ,0
Exp/Cntr=0.3,0.1

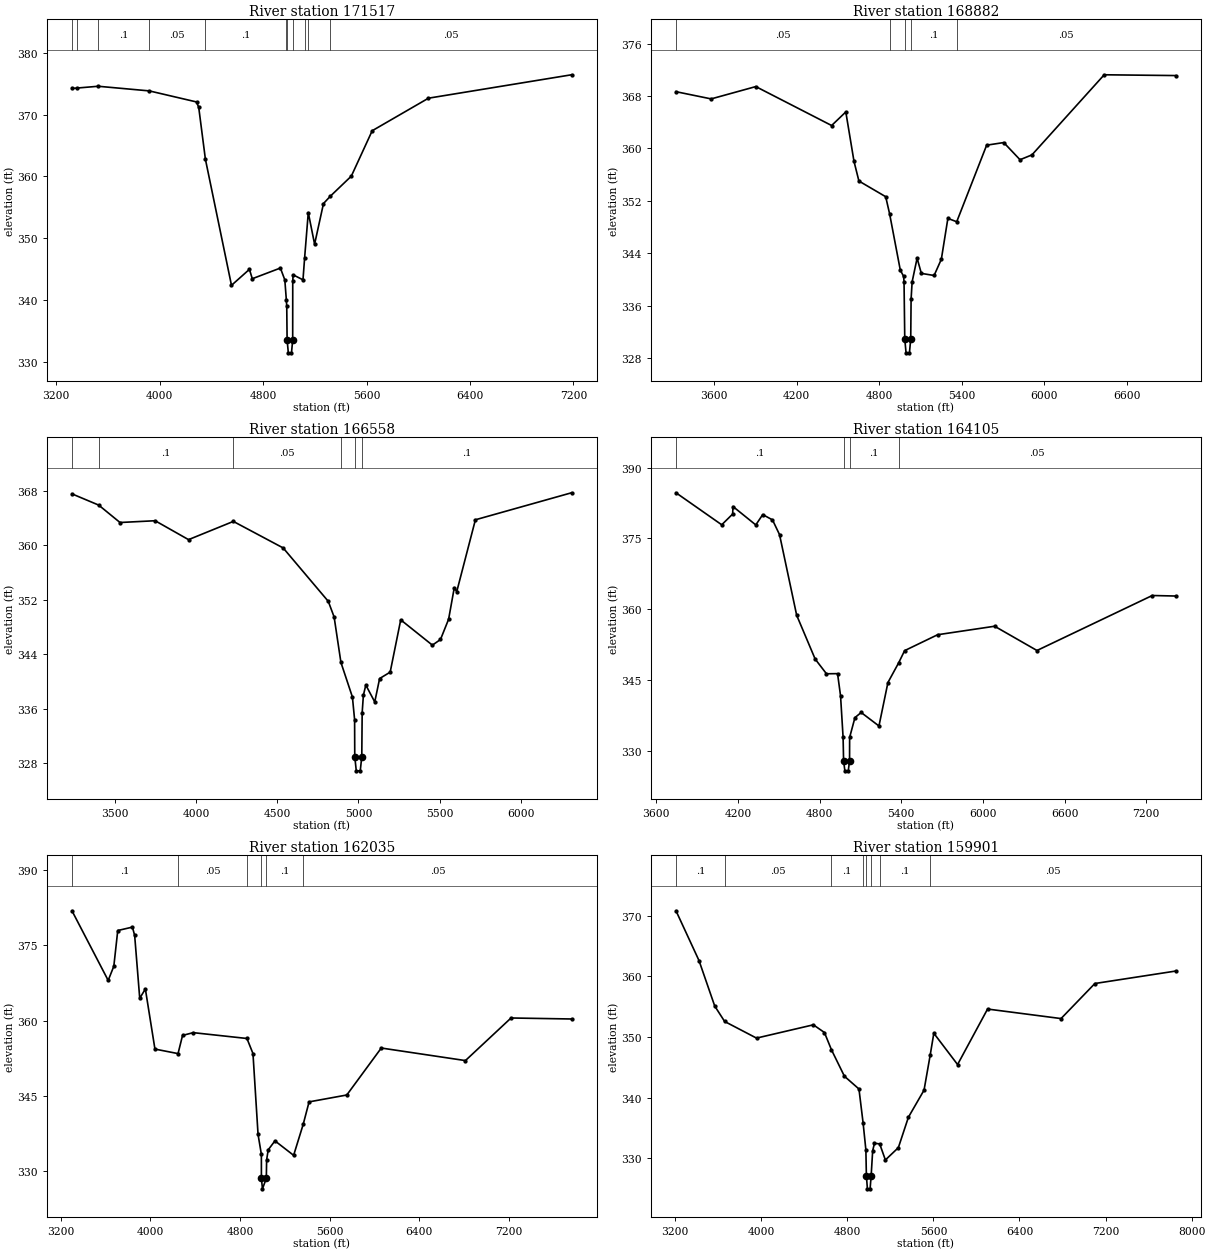
Type RM Length L Ch R = 1 ,171517  ,2635,2635,2635
BEGIN DESCRIPTION:
San Miguel Creek 59.0
END DESCRIPTION:
XS GIS Cut Line= 3
      2051227.37     13437114.02        2050525.       13435625.
      2049274.25     13433793.73
#Sta/Elev= 30
  3321.5  374.23  3359.7   374.3  3524.5  374.59  3919.7  373.84  4285.1  372.05
  4302.1  371.16  4353.6  362.78  4555.4  342.36  4694.2  344.95  4716.3  343.43
  4933.7  345.16  4967.9  343.24  4979.8  339.97  4982.8  338.95  4985.6  333.53
    4995  331.43  5019.5  331.43  5028.8  333.53  5029.2   343.1  5032.2  344.06
  5108.4  343.25  5121.2  346.84  5149.4  354.14  5198.2  349.02  5266.9   355.6
  5319.9  356.79  5482.3  360.04  5643.8  367.39    6079  372.66  7185.5  376.45
#Mann= 11 ,-1 , 0
  3321.5      .1       0  3359.7     .05       0  3524.5      .1       0
  3919.7     .05       0  4353.6      .1       0  4979.8     .07       0
  4985.6     .07       0  5028.8     .07       0  5121.2     .07       0
  5149.4      .1       0  5319.9     .05       0
Bank Sta=4985.6,5028.8
XS Rating Curve= 0 ,0
Exp/Cntr=0.3,0.1

Type RM Length L Ch R = 1 ,168882  ,2324,2324,2324
BEGIN DESCRIPTION:
San Miguel Creek 58.0
END DESCRIPTION:
XS GIS Cut Line= 3
      2053419.22     13436549.81       2052770.8     13435004.54
      2052117.24     13433164.67
#Sta/Elev= 30
  3324.2  368.65  3579.7  367.55  3903.9  369.43  4454.6  363.49  4557.6  365.56
  4617.2  358.01  4652.8  355.02  4847.3  352.63  4875.9     350  4953.4  341.43
    4977   340.5  4980.5  339.69  4985.8  330.91  4995.2  328.81  5019.7  328.81
  5029.1  330.91  5031.8     337  5039.3  339.64  5075.4  343.25  5106.3  340.93
  5198.9  340.61  5251.5  343.09  5298.9  349.32  5363.2  348.81  5580.5  360.49
  5704.8  360.89  5822.9  358.27  5909.5  359.01  6434.3  371.23  6952.5  371.11
#Mann= 5 ,-1 , 0
  3324.2     .05       0  4875.9      .1       0  4985.8     .07       0
  5029.1      .1       0  5363.2     .05       0
Bank Sta=4985.8,5029.1
XS Rating Curve= 0 ,0
Exp/Cntr=0.3,0.1

Type RM Length L Ch R = 1 ,166558  ,2453,2453,2453
BEGIN DESCRIPTION:
San Miguel Creek 57.0
END DESCRIPTION:
XS GIS Cut Line= 3
      2053874.97     13436525.04        2054875.       13435025.
      2054873.22     13433750.33
#Sta/Elev= 30
  3235.4  367.58    3400  365.93  3531.4  363.37  3747.7  363.63  3953.6  360.85
  4229.6  363.53  4536.5  359.63  4814.4  351.78  4850.4  349.48  4892.3   342.8
  4963.1  337.71  4976.6  334.37  4977.5  328.96  4986.9  326.86  5011.4  326.86
  5020.8  328.96  5023.2  335.41  5030.7  337.98  5045.7  339.47  5100.7  336.99
  5130.7  340.43  5195.7  341.37  5260.7  349.06  5455.7  345.34  5505.7  346.17
  5555.7  349.15  5590.7   353.8  5605.7   353.2  5720.7  363.77  6312.9  367.74
#Mann= 6 ,-1 , 0
  3235.4     .05       0    3400      .1       0  4229.6     .05       0
  4892.3      .1       0  4977.5     .07       0  5020.8      .1       0
Bank Sta=4977.5,5020.8
XS Rating Curve= 0 ,0
Exp/Cntr=0.3,0.1

Type RM Length L Ch R = 1 ,164105  ,2070,2070,2070
BEGIN DESCRIPTION:
San Miguel Creek 56.0
END DESCRIPTION:
XS GIS Cut Line= 3
      2057413.99      13436263.4        2057175.       13435025.
      2056281.18     13432786.82
#Sta/Elev= 30
  3744.2  384.66  4080.3  377.88  4160.6  380.15  4163.1  381.75  4330.7  377.85
  4381.6  380.04  4453.4  378.92  4505.3  375.79  4631.2  358.71    4767  349.44
  4850.1  346.32  4931.6  346.35  4953.6  341.65  4972.3  332.84  4975.9  327.86
  4985.4  325.76  5010.2  325.76  5019.8  327.86  5020.3  332.83  5059.3  337.03
  5105.1  338.12  5235.8  335.26  5301.8  344.47  5380.7  348.64  5424.4  351.22
  5666.9  354.59  6085.8  356.39  6397.2  351.25  7244.3   362.9  7415.5  362.79
#Mann= 4 ,-1 , 0
  3744.2      .1       0  4975.9     .07       0  5019.8      .1       0
  5380.7     .05       0
Bank Sta=4975.9,5019.8
XS Rating Curve= 0 ,0
Exp/Cntr=0.3,0.1

Type RM Length L Ch R = 1 ,162035  ,2134,2134,2134
BEGIN DESCRIPTION:
San Miguel Creek 55.0
END DESCRIPTION:
XS GIS Cut Line= 3
        2059225.     13436028.95      2059054.26     13434338.45
      2057192.62     13432305.03
#Sta/Elev= 30
  3300.9  381.87    3624  368.01  3674.2  370.82  3709.4  377.94  3840.1  378.62
  3860.2  376.96  3905.4  364.45  3955.7   366.3  4041.1  354.34  4247.1  353.44
  4287.3  357.06  4382.8  357.61  4861.7  356.45  4915.5  353.45  4960.8  337.35
  4990.5  333.37  4990.6  328.62  5000.2  326.52  5034.6  328.62  5037.2  332.26
  5051.4  334.29  5111.6  336.07  5278.1  333.19  5363.9  339.39  5415.9  343.83
  5752.3   345.2    6060  354.55  6810.4  352.05  7217.4  360.53  7756.9  360.33
#Mann= 6 ,-1 , 0
  3300.9      .1       0  4247.1     .05       0  4861.7      .1       0
  4990.6     .07       0  5034.6      .1       0  5363.9     .05       0
Bank Sta=4990.6,5034.6
XS Rating Curve= 0 ,0
Exp/Cntr=0.3,0.1

Type RM Length L Ch R = 1 ,159901  ,2275,2275,2275
BEGIN DESCRIPTION:
San Miguel Creek 54.0
END DESCRIPTION:
XS GIS Cut Line= 3
      2061574.97     13433724.97      2060153.43     13432632.72
      2057367.18     13432031.41
#Sta/Elev= 30
  3207.3  370.82  3421.1  362.62  3567.5  355.11  3659.6  352.57  3955.8  349.83
  4484.1  352.02  4587.1  350.75  4652.7  347.89  4772.9  343.54  4907.9  341.44
  4946.2  335.88  4972.2  331.41    4977  327.08  4986.6  324.98  5011.4  324.98
    5021  327.08  5035.4  331.26  5052.1  332.49  5100.7  332.39  5153.5  329.74
  5274.1  331.77  5367.6  336.79  5512.8  341.25  5569.4  346.97  5603.7  350.63
  5824.5  345.47  6103.2  354.62  6786.1  353.05  7100.7  358.83  7850.4  360.88
#Mann= 8 ,-1 , 0
  3207.3      .1       0  3659.6     .05       0  4652.7      .1       0
  4946.2     .12       0    4977     .07       0    5021     .12       0
  5100.7      .1       0  5569.4     .05       0
Bank Sta=4977,5021
XS Rating Curve= 0 ,0
Exp/Cntr=0.3,0.1

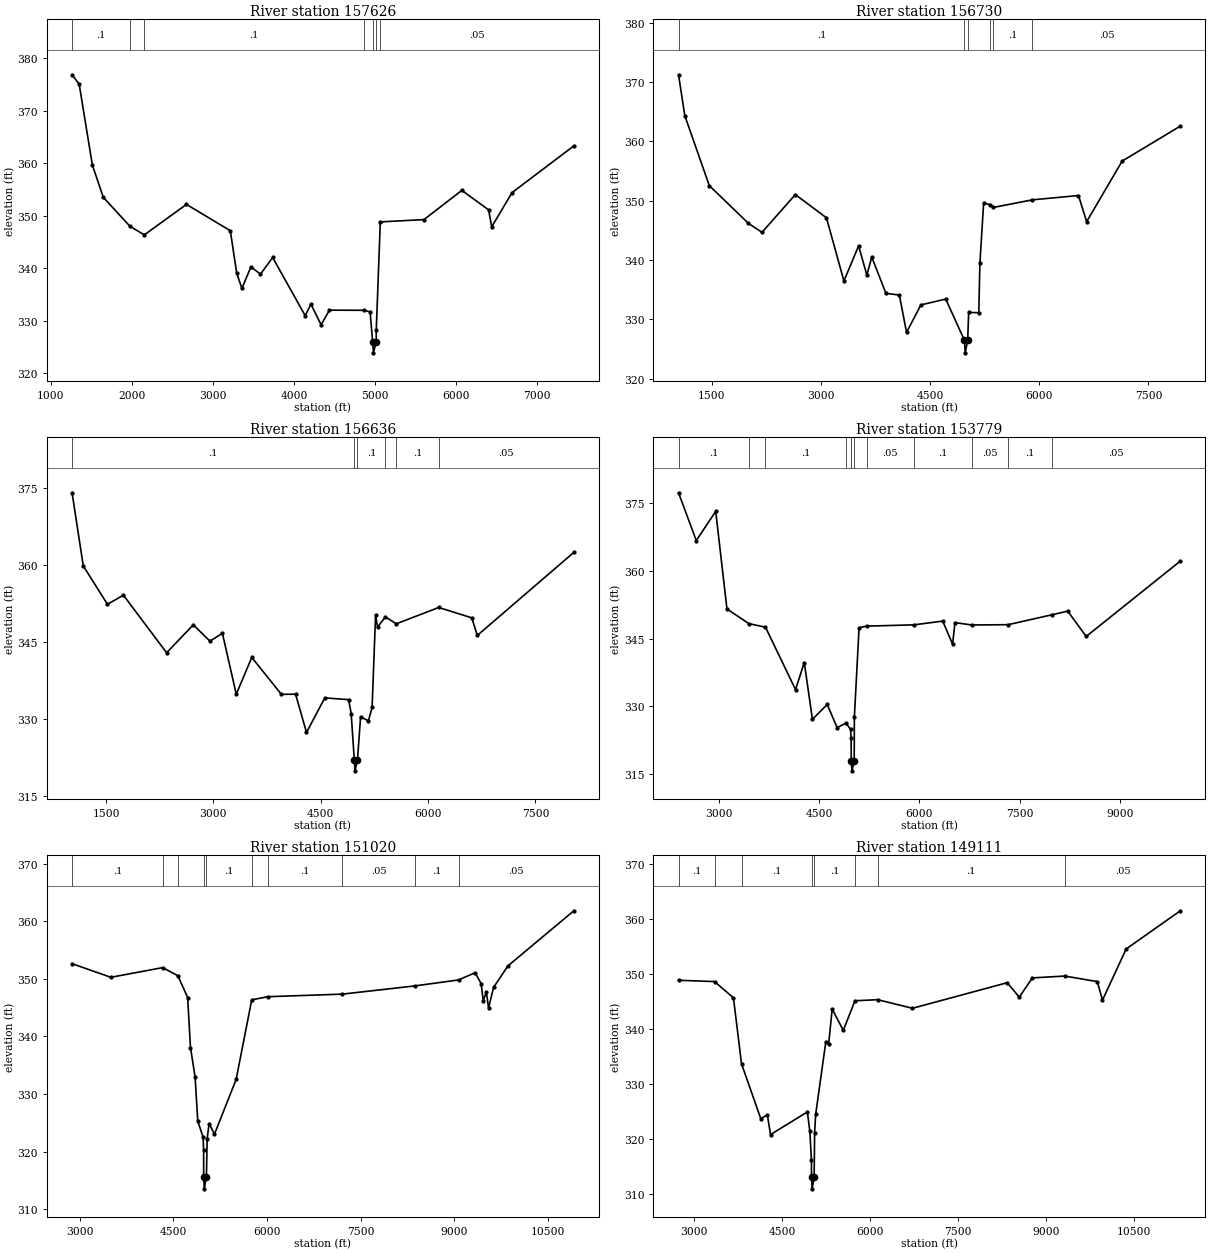
Type RM Length L Ch R = 1 ,157626  ,896,896,896
BEGIN DESCRIPTION:
San Miguel Creek 53.0
END DESCRIPTION:
XS GIS Cut Line= 4
      2061711.74     13433637.32      2061024.26     13431890.82
       2059920.8     13430395.16      2057606.26     13429582.39
#Sta/Elev= 30
  1264.4  376.83    1352  375.06  1514.5  359.64  1649.9  353.48  1979.1  347.96
    2156  346.34    2675  352.14  3216.4  347.13  3294.7  339.04  3359.4  336.15
  3470.1  340.23  3588.1  338.86  3738.5  342.03  4139.4  330.95  4210.4  333.14
  4335.7  329.22    4439     332  4865.4  331.97  4940.2  331.66  4971.5  325.97
  4981.1  323.87  5015.5  325.97  5016.2  328.28    5066  348.81  5604.5  349.25
  6071.6  354.81  6401.9   351.1  6439.6  347.87    6691  354.39  7453.1  363.29
#Mann= 7 ,-1 , 0
  1264.4      .1       0  1979.1     .05       0    2156      .1       0
  4865.4     .12       0  4971.5     .07       0  5015.5     .12       0
    5066     .05       0
Bank Sta=4971.5,5015.5
XS Rating Curve= 0 ,0
Exp/Cntr=0.3,0.1

Type RM Length L Ch R = 1 ,156730  ,94,94,94
BEGIN DESCRIPTION:
Mapping XS 80568dd9
END DESCRIPTION:
XS GIS Cut Line= 6
      2061861.94     13433647.42      2061367.15     13431676.93
      2060516.46     13430600.54       2060492.2     13430056.44
      2060360.09     13429814.72      2057774.18     13429246.53
#Sta/Elev= 30
  1041.9  371.23  1127.9  364.34  1464.1  352.56    2003  346.18    2189  344.67
  2647.2  351.04  3074.8  347.12  3314.9  336.47  3516.9   342.4  3630.2  337.46
  3697.6   340.5  3892.3  334.39  4076.5   334.1  4175.5  327.81  4372.4  332.44
  4713.9  333.42  4971.9  326.46  4981.5  324.36  5015.9  326.46  5029.3  331.17
  5168.6  331.13  5183.4  339.43    5235  349.61    5329  349.31  5369.1  348.87
  5905.7  350.15  6538.6  350.88  6650.9  346.47  7138.5  356.68  7938.2  362.58
#Mann= 6 ,-1 , 0
  1041.9      .1       0  4971.9     .07       0  5015.9      .1       0
    5329     .05       0  5369.1      .1       0  5905.7     .05       0
Bank Sta=4971.9,5015.9
XS Rating Curve= 0 ,0
Exp/Cntr=0.3,0.1

Type RM Length L Ch R = 1 ,156636  ,2857,2857,2857
BEGIN DESCRIPTION:
Mapping XS 16ea8571
END DESCRIPTION:
XS GIS Cut Line= 6
      2061974.78     13433656.05      2061540.76     13431538.04
      2060646.67     13430479.02      2060560.16     13429941.95
      2060395.93      13429657.4      2057869.42     13429159.68
#Sta/Elev= 30
  1026.1  374.06  1182.6  359.81  1520.8  352.33  1743.1  354.11  2346.8  342.89
  2719.4  348.33  2952.4  345.15  3126.2  346.69  3319.9   334.8  3536.4  341.98
  3950.1  334.79  4148.6  334.81    4301  327.37    4557   334.1  4889.8  333.75
  4925.2  331.03  4969.1  321.98  4978.7  319.88  5013.1  321.98  5056.9   330.4
  5166.3  329.62  5217.5  332.24  5265.9  350.17  5293.5  347.89  5403.4  349.87
  5555.5  348.53  6148.4  351.71  6610.1  349.69  6687.2  346.26  8036.1  362.45
#Mann= 6 ,-1 , 0
  1026.1      .1       0  4969.1     .07       0  5013.1      .1       0
  5403.4     .05       0  5555.5      .1       0  6148.4     .05       0
Bank Sta=4969.1,5013.1
XS Rating Curve= 0 ,0
Exp/Cntr=0.3,0.1

Type RM Length L Ch R = 1 ,153779  ,2759,2759,2759
BEGIN DESCRIPTION:
Mapping XS 7adda797
END DESCRIPTION:
XS GIS Cut Line= 6
      2063072.04     13432645.98      2062442.99     13431307.41
       2062065.1     13429711.96      2061787.32     13429364.74
      2061092.87     13429225.85      2057881.06     13429121.68
#Sta/Elev= 30
  2401.6  377.34  2666.4  366.76    2957  373.22    3125   351.6  3453.4  348.34
  3700.5  347.57    4149  333.73    4280  339.73  4401.6  327.15  4623.1  330.44
  4770.8  325.32    4904   326.3  4971.4  324.92  4979.8  322.93  4981.8  317.84
  4991.5  315.74  5025.9  317.84    5028  327.62  5098.4  347.43  5210.6   347.8
  5916.3  348.08  6348.2  348.91  6495.4  343.81    6531  348.58    6785  348.05
  7324.8  348.12  7976.1   350.3  8215.1  351.12  8491.1  345.51  9897.3  362.21
#Mann= 11 ,-1 , 0
  2401.6      .1       0  3453.4     .05       0  3700.5      .1       0
    4904     .07       0  4981.8     .07       0  5025.9     .07       0
  5210.6     .05       0  5916.3      .1       0    6785     .05       0
  7324.8      .1       0  7976.1     .05       0
Bank Sta=4981.8,5025.9
XS Rating Curve= 0 ,0
Exp/Cntr=0.3,0.1

Type RM Length L Ch R = 1 ,151020  ,1909,1909,1909
BEGIN DESCRIPTION:
San Miguel Creek 52.0
END DESCRIPTION:
XS GIS Cut Line= 5
      2065867.15     13430050.49       2063950.8     13429144.54
      2063284.71     13429073.94      2060226.56     13429184.62
      2058050.35     13429044.35
#Sta/Elev= 30
  2880.3  352.62  3501.8  350.26  4330.6  351.94  4572.9  350.54  4729.9  346.75
  4775.4  338.07  4849.2  332.95    4892  325.28  4977.1   322.5  4985.8  320.24
  4986.2  315.63  4995.8  313.53  5030.5  315.63    5042  322.21  5073.7  324.87
  5159.2  323.02  5506.1  332.53  5755.7  346.35  6013.3  346.89  7207.3  347.34
  8362.4  348.76  9064.6   349.8  9330.3  351.05  9425.8  349.18  9460.5  346.23
  9510.6  347.66  9545.7  344.94  9625.9  348.51  9856.4  352.25 10910.7  361.81
#Mann= 10 ,-1 , 0
  2880.3      .1       0  4330.6     .05       0  4572.9      .1       0
  4986.2     .07       0  5030.5      .1       0  5755.7     .05       0
  6013.3      .1       0  7207.3     .05       0  8362.4      .1       0
  9064.6     .05       0
Bank Sta=4986.2,5030.5
XS Rating Curve= 0 ,0
Exp/Cntr=0.3,0.1

Type RM Length L Ch R = 1 ,149111  ,3049,3049,3049
BEGIN DESCRIPTION:
San Miguel Creek 51.0
END DESCRIPTION:
XS GIS Cut Line= 6
      2066046.77      13428251.2       2063930.8     13427434.54
      2063655.83     13427474.34      2063100.25     13428178.47
      2060248.69     13429089.93       2058139.7     13428894.65
#Sta/Elev= 30
  2731.9  348.85  3346.5  348.61    3669  345.65  3806.4  333.65  4135.2  323.65
    4247  324.37  4301.4  320.76  4930.2  324.88  4972.5  321.32  4999.4  316.17
  5001.3  312.98    5011  310.88  5045.7  312.98  5053.9  321.12  5072.3  324.49
  5245.4  337.68  5293.4  337.27  5353.5  343.61  5542.7  339.73  5742.3  345.12
  6130.4  345.31  6723.4  343.75  8340.8  348.41  8545.5  345.77  8768.2  349.28
  9321.5  349.62  9878.5   348.6  9965.1  345.22 10368.6  354.54 11293.6   361.5
#Mann= 8 ,-1 , 0
  2731.9      .1       0  3346.5     .05       0  3806.4      .1       0
  5001.3     .07       0  5045.7      .1       0  5742.3     .05       0
  6130.4      .1       0  9321.5     .05       0
Bank Sta=5001.3,5045.7
XS Rating Curve= 0 ,0
Exp/Cntr=0.3,0.1

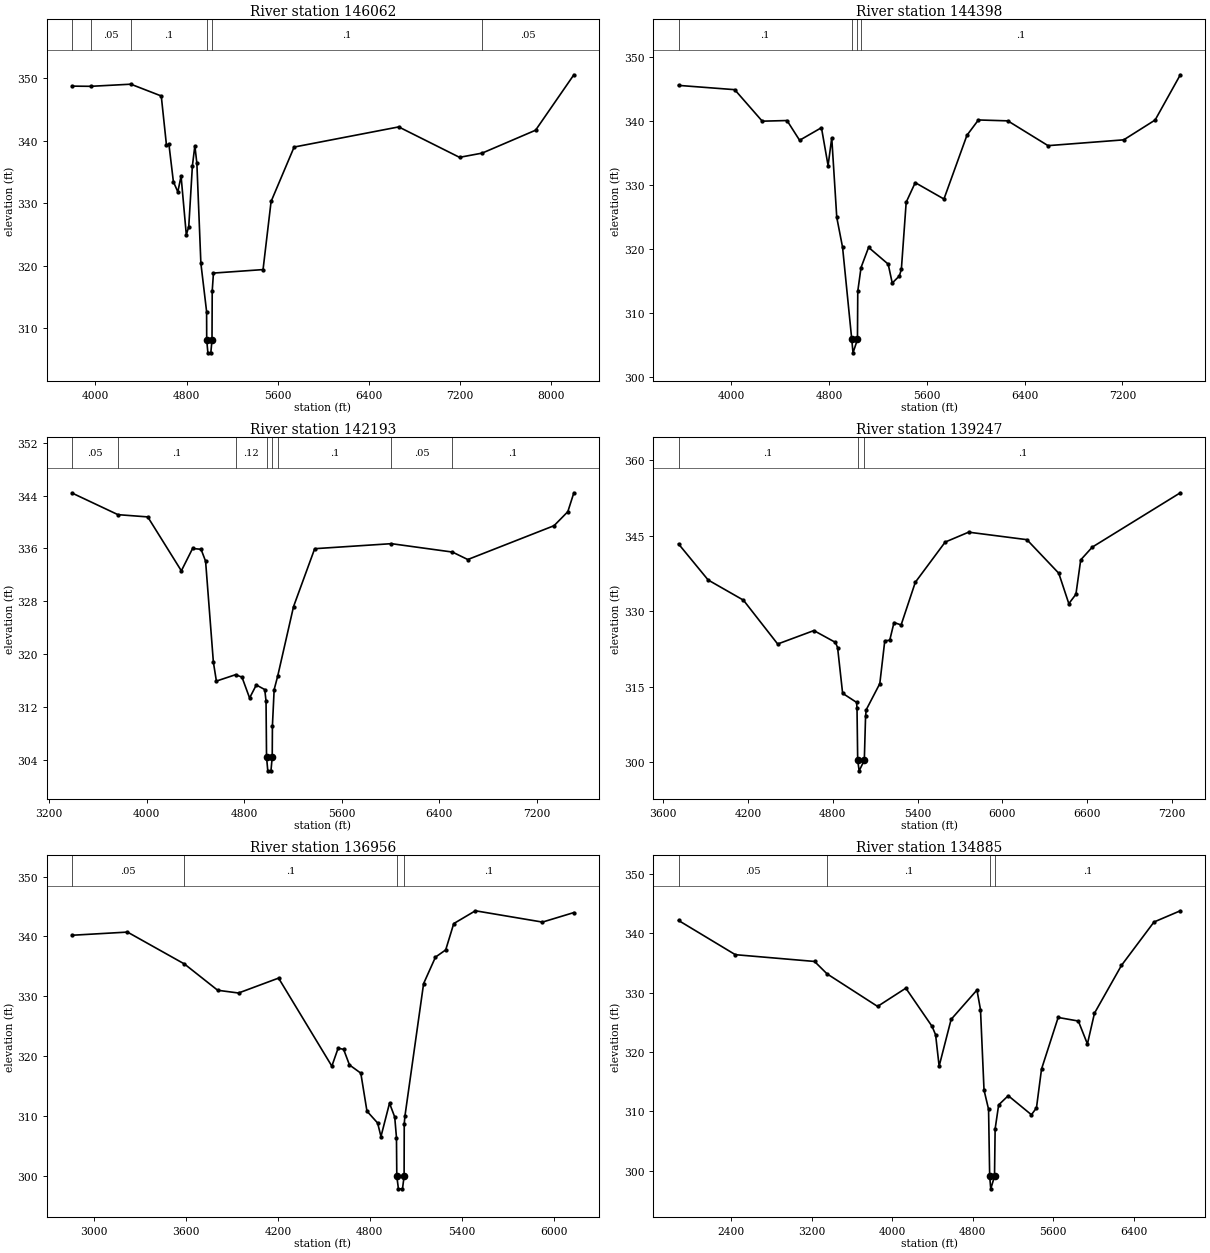
Type RM Length L Ch R = 1 ,146062  ,1664,1664,1664
BEGIN DESCRIPTION:
San Miguel Creek 50.0
END DESCRIPTION:
XS GIS Cut Line= 4
      2066550.79     13427490.55       2065790.8     13426554.54
      2065352.86     13426162.41      2062957.05     13425120.75
#Sta/Elev= 30
  3794.3  348.77  3959.3  348.74  4310.3  349.08  4577.5  347.19  4623.2  339.29
  4644.7  339.45  4683.9  333.44    4723  331.81  4751.4  334.34  4797.4  324.93
  4818.9  326.23  4850.9  335.99  4872.5  339.21  4890.1   336.4  4925.3  320.36
  4975.6  312.61  4976.5   308.1  4986.8     306  5012.7     306    5023   308.1
  5024.9  315.92  5035.7  318.79  5471.2  319.35  5541.8  330.27    5744     339
  6662.4  342.23  7196.4  337.35  7395.3  338.03  7864.1   341.7  8200.3  350.59
#Mann= 6 ,-1 , 0
  3794.3      .1       0  3959.3     .05       0  4310.3      .1       0
  4976.5     .07       0    5023      .1       0  7395.3     .05       0
Bank Sta=4976.5,5023
XS Rating Curve= 0 ,0
Exp/Cntr=0.3,0.1

Type RM Length L Ch R = 1 ,144398  ,2205,2205,2205
BEGIN DESCRIPTION:
San Miguel Creek 49.0
END DESCRIPTION:
XS GIS Cut Line= 3
      2067475.25     13426826.47       2066920.8     13425504.54
      2065691.77     13423129.27
#Sta/Elev= 30
  3566.5  345.59  4026.3  344.92  4251.8  339.99  4454.6  340.09  4557.6     337
  4736.5  338.97  4790.8  333.04  4820.8  337.39  4861.9  324.93  4909.4  320.25
  4984.6  305.84  4994.9  303.74  5031.3  305.84  5033.8  313.37  5060.6  317.09
  5122.4  320.24  5282.8  317.62    5316  314.66  5374.2  315.77  5390.7  316.81
  5430.2  327.31  5504.2  330.37  5739.3  327.81  5927.5  337.78  6021.3  340.18
  6262.2  340.04  6591.5  336.16  7211.2  337.07  7468.1  340.17  7674.4  347.25
#Mann= 4 ,-1 , 0
  3566.5      .1       0  4984.6     .07       0  5031.3      .1       0
  5060.6      .1       0
Bank Sta=4984.6,5031.3
XS Rating Curve= 0 ,0
Exp/Cntr=0.3,0.1

Type RM Length L Ch R = 1 ,142193  ,2946,2946,2946
BEGIN DESCRIPTION:
San Miguel Creek 48.0
END DESCRIPTION:
XS GIS Cut Line= 3
      2069037.75     13425589.48        2068475.       13424075.
      2066785.14     13422230.11
#Sta/Elev= 30
  3388.5  344.39  3764.9  341.12  4009.4  340.78  4285.2  332.62  4377.4     336
  4446.9  335.88  4484.1  334.08  4548.1  318.79  4572.8  315.94  4730.7  316.91
  4782.8  316.53  4845.2  313.38  4900.1  315.35  4969.5  314.66  4980.1  312.91
  4984.2  304.46  4994.5  302.36  5020.5  302.36  5030.9  304.46  5032.5  309.17
  5046.7  314.65  5075.5  316.67  5205.8  327.21  5379.4  335.97  6008.6  336.73
  6509.8  335.46  6635.5  334.33  7343.4  339.45  7456.5  341.57    7506  344.43
#Mann= 8 ,-1 , 0
  3388.5     .05       0  3764.9      .1       0  4730.7     .12       0
  4984.2     .07       0  5030.9     .12       0  5075.5      .1       0
  6008.6     .05       0  6509.8      .1       0
Bank Sta=4984.2,5030.9
XS Rating Curve= 0 ,0
Exp/Cntr=0.3,0.1

Type RM Length L Ch R = 1 ,139247  ,2291,2291,2291
BEGIN DESCRIPTION:
San Miguel Creek 47.0
END DESCRIPTION:
XS GIS Cut Line= 3
      2070708.76      13424213.6       2070940.8     13422944.54
      2070721.78     13420697.99
#Sta/Elev= 30
  3709.9  343.35  3919.4  336.18  4168.5  332.18  4410.8  323.46  4666.6  326.13
  4819.1  323.78  4834.3  322.75  4869.9  313.66  4968.4  311.86  4971.6  310.72
  4976.4  300.35  4986.7  298.25  5023.2  300.35  5032.2   309.2  5037.2  310.42
  5132.7  315.58  5167.8  324.08    5203  324.22  5233.1  327.73  5283.4  327.25
  5383.8  335.73  5594.8  343.72  5760.6  345.69  6172.6   344.2  6397.8  337.53
    6469  331.48  6519.2  333.35    6553  340.18  6634.8  342.72  7257.2  353.52
#Mann= 3 ,-1 , 0
  3709.9      .1       0  4976.4     .07       0  5023.2      .1       0
Bank Sta=4976.4,5023.2
XS Rating Curve= 0 ,0
Exp/Cntr=0.3,0.1

Type RM Length L Ch R = 1 ,136956  ,2071,2071,2071
BEGIN DESCRIPTION:
San Miguel Creek 46.0
END DESCRIPTION:
XS GIS Cut Line= 3
      2072010.84     13424786.55       2073020.8     13422894.54
      2073538.62     13421887.24
#Sta/Elev= 30
  2855.3   340.2  3217.2  340.73  3589.2   335.4  3806.3  331.01  3942.4  330.55
    4204  333.04    4552  318.33  4593.1  321.34  4628.9  321.13  4667.1  318.53
  4741.1  317.16  4781.3  310.81  4850.9  308.83  4872.8  306.57  4928.6  312.14
  4962.6  309.83    4974   306.4  4976.2  299.93  4986.8  297.83  5013.3  297.83
  5023.9  299.93  5024.8   308.7  5029.3  309.98  5151.3  332.13  5228.9  336.55
  5295.5  337.75  5348.1  342.15  5489.5  344.29  5927.5   342.4  6132.6  343.99
#Mann= 4 ,-1 , 0
  2855.3     .05       0  3589.2      .1       0  4976.2     .07       0
  5023.9      .1       0
Bank Sta=4976.2,5023.9
XS Rating Curve= 0 ,0
Exp/Cntr=0.3,0.1

Type RM Length L Ch R = 1 ,134885  ,1759,1759,1759
BEGIN DESCRIPTION:
San Miguel Creek 45.0
END DESCRIPTION:
XS GIS Cut Line= 3
      2074420.57     13427130.29        2074575.       13424025.
      2074654.94     13422156.34
#Sta/Elev= 30
  1880.4  342.15  2443.9  336.39  3229.9  335.25  3354.3  333.16  3855.6  327.68
    4136  330.75  4396.3  324.32  4431.3  322.91  4466.4  317.62  4585.5   325.5
  4841.8  330.44  4876.9  327.13  4911.9   313.6    4957  310.36    4968  299.07
  4978.7  296.97    5016  299.07  5022.1  307.05  5057.1   311.1  5152.2  312.65
  5382.4  309.44  5432.4  310.61  5482.5  317.13  5647.6  325.82  5847.8  325.22
  5937.9  321.36    6008  326.54    6276  334.59  6598.5  341.89  6859.9  343.78
#Mann= 4 ,-1 , 0
  1880.4     .05       0  3354.3      .1       0    4968     .07       0
    5016      .1       0
Bank Sta=4968,5016
XS Rating Curve= 0 ,0
Exp/Cntr=0.3,0.1