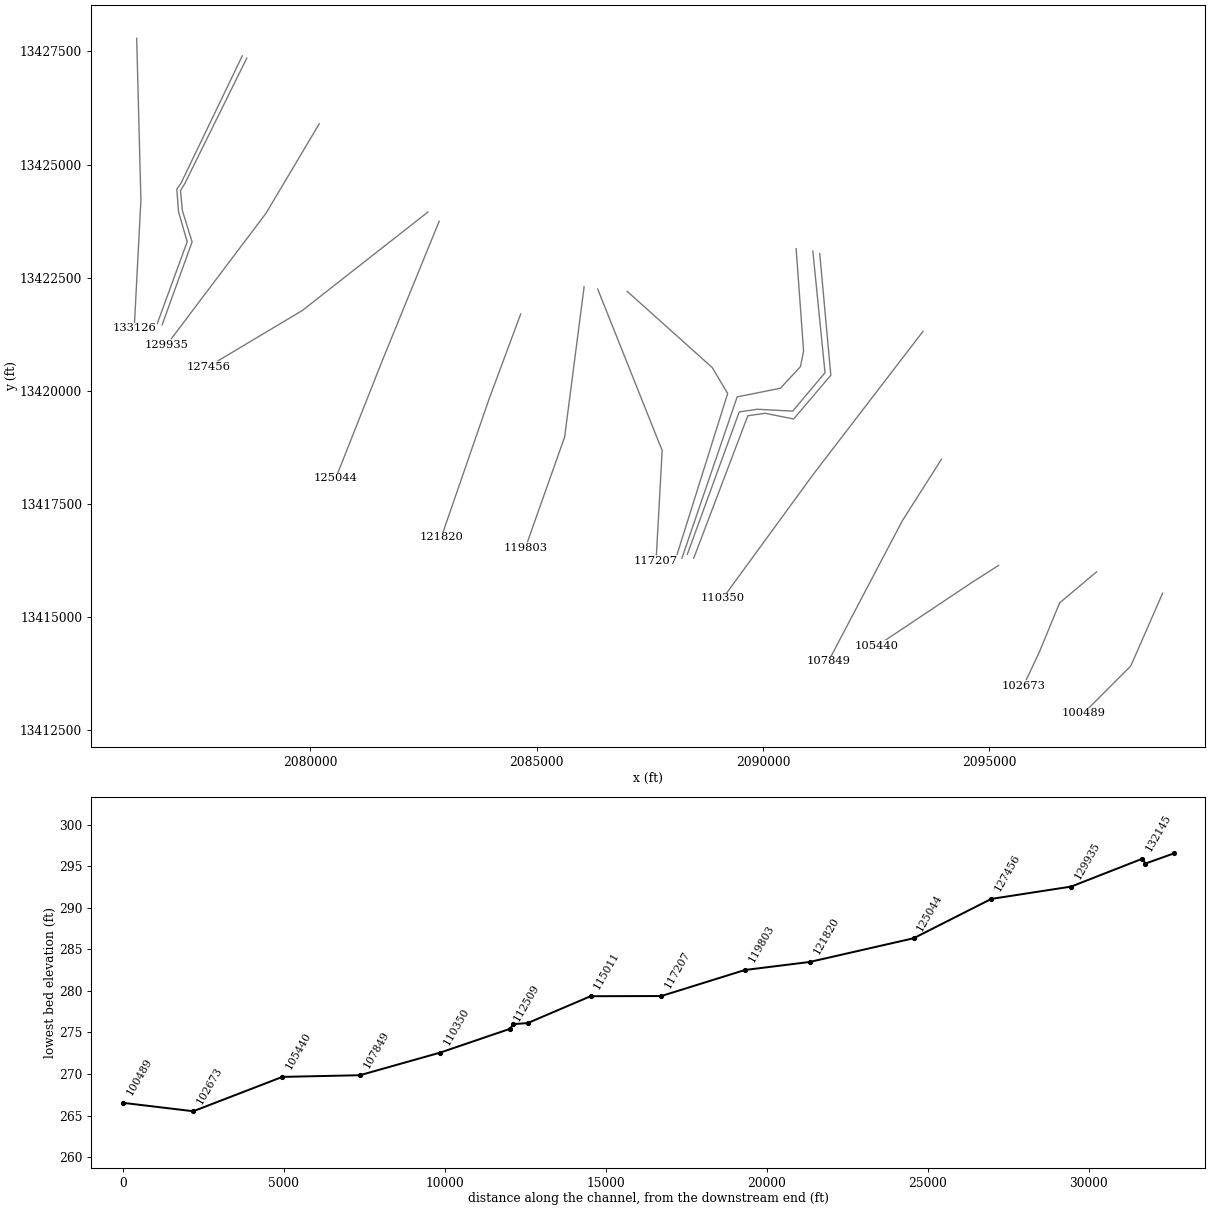
HEC-RAS study San Miguel Creek.prj: San Miguel Creek Base Level Engineering

--- San Miguel Creek.g01 (geometry) --- (continued)

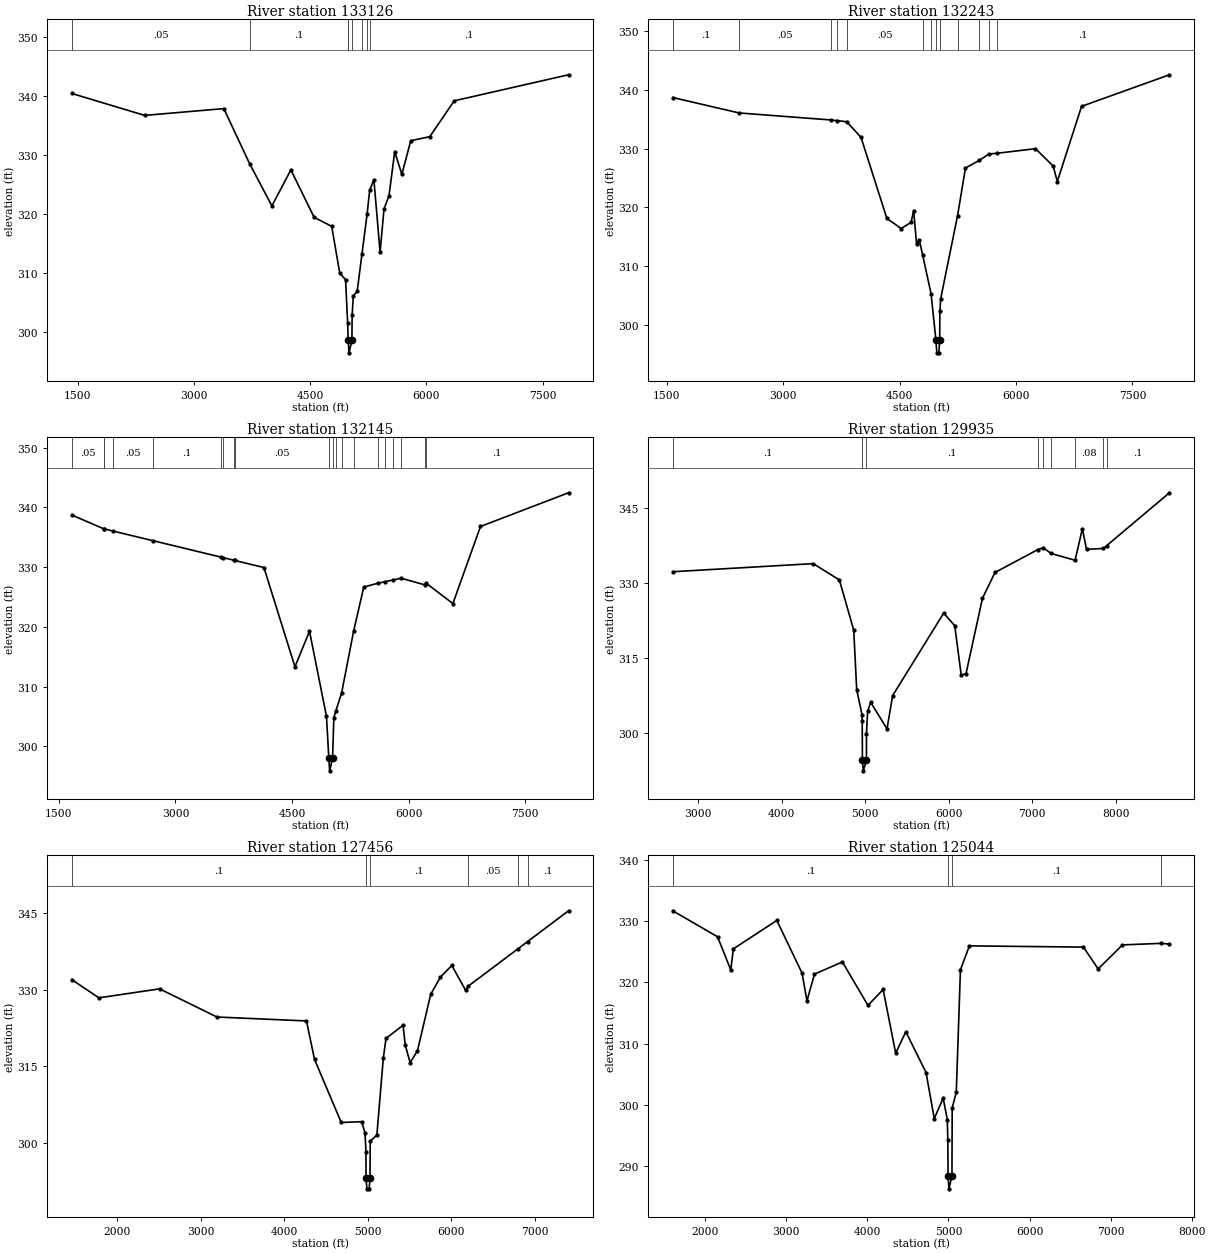
Type RM Length L Ch R = 1 ,133126  ,883,883,883
BEGIN DESCRIPTION:
San Miguel Creek 44.0
END DESCRIPTION:
XS GIS Cut Line= 3
      2076167.63     13427787.12       2076260.8     13424214.54
      2076113.38     13421385.28
#Sta/Elev= 30
  1426.2  340.46  2366.1  336.75  3386.5   337.9  3722.2   328.5  4006.7  321.42
  4251.8  327.52  4551.9  319.48  4778.5  317.96    4882  310.02    4957  308.93
  4984.1   301.6  4990.9  298.63  5001.6  296.53  5038.9  298.63  5042.1  302.97
  5057.1  306.19  5107.2  306.95  5169.1  313.33  5235.5  320.08  5268.1  324.09
  5322.5  325.85  5402.6  313.56  5452.7  320.88  5517.7  323.17  5591.1   330.6
    5683  326.77  5798.1  332.46  6043.5  333.15  6358.5  339.22  7833.1  343.63
#Mann= 8 ,-1 , 0
  1426.2     .05       0  3722.2      .1       0  4984.1     .12       0
  4990.9     .07       0  5038.9     .12       0  5169.1      .1       0
  5235.5     .16       0  5268.1      .1       0
Bank Sta=4990.9,5038.9
XS Rating Curve= 0 ,0
Exp/Cntr=0.3,0.1

Type RM Length L Ch R = 1 ,132243  ,98,98,98
BEGIN DESCRIPTION:
Mapping XS 817019f5
END DESCRIPTION:
XS GIS Cut Line= 6
      2078500.01     13427400.02      2077145.11     13424583.91
      2077053.97     13424456.31      2077090.42     13423964.12
      2077282.81     13423293.01      2076621.35     13421485.73
#Sta/Elev= 30
    1576  338.66  2431.4  336.04  3610.7  334.85  3696.8  334.73  3817.8  334.55
  4002.4   331.9  4335.7  318.13  4519.4  316.42  4647.8  317.46  4680.7  319.47
  4718.4  313.84    4754  314.46  4797.8  311.84  4905.6  305.33  4968.2  297.41
    4979  295.31  5005.6  295.31  5016.3  297.41  5018.7  302.35  5028.8  304.48
  5246.4  318.58  5348.6  326.69  5529.1     328  5650.1  329.07  5751.8  329.19
  6250.9  329.97  6478.7  327.02  6531.9   324.4  6844.7  337.16  7976.7  342.52
#Mann= 13 ,-1 , 0
    1576      .1       0  2431.4     .05       0  3610.7     .08       0
  3696.8      .1       0  3817.8     .05       0  4797.8      .1       0
  4905.6     .05       0  4968.2     .04       0  5016.3     .05       0
  5246.4      .1       0  5529.1     .08       0  5650.1     .05       0
  5751.8      .1       0
Bank Sta=4968.2,5016.3
XS Rating Curve= 0 ,0
Exp/Cntr=0.3,0.1

Type RM Length L Ch R = 1 ,132145  ,2210,2210,2210
BEGIN DESCRIPTION:
Mapping XS 84302197
END DESCRIPTION:
XS GIS Cut Line= 6
      2078599.98     13427349.96      2077228.99     13424577.44
      2077135.35     13424423.54      2077177.66     13423977.58
      2077391.54     13423291.92      2076730.79     13421459.85
#Sta/Elev= 30
  1667.7  338.71  2076.2  336.41  2087.5  336.37  2199.3  336.02  2714.8   334.4
  3583.7  331.67  3615.5  331.57  3751.3  331.14  3764.1   331.1  4138.3  329.92
  4537.5   313.3  4724.4  319.26  4942.6  305.03    4973  297.99  4983.7  295.89
  5021.1  297.99  5037.4  304.79  5062.9  305.91  5138.2  308.98  5292.7  319.32
  5422.3  326.65  5604.3  327.29  5698.1  327.55  5800.7  327.84  5903.3  328.13
  6214.5  326.99    6219  327.35  6568.5  323.89  6923.4  336.79  8055.8  342.43
#Mann= 20 ,-1 , 0
  1667.7     .05       0  2076.2      .1       0  2087.5     .08       0
  2199.3     .05       0  2714.8      .1       0  3583.7     .05       0
  3615.5      .1       0  3751.3     .08       0  3764.1     .05       0
    4973     .04       0  5021.1     .05       0  5062.9      .1       0
  5138.2     .05       0  5292.7     .08       0  5604.3      .1       0
  5698.1     .08       0  5800.7     .05       0  5903.3     .08       0
  6214.5     .05       0    6219      .1       0
Bank Sta=4973,5021.1
XS Rating Curve= 0 ,0
Exp/Cntr=0.3,0.1

Type RM Length L Ch R = 1 ,129935  ,2479,2479,2479
BEGIN DESCRIPTION:
San Miguel Creek 43.0
END DESCRIPTION:
XS GIS Cut Line= 3
      2080200.01     13425900.02        2079025.       13423925.
      2076827.49     13421012.43
#Sta/Elev= 30
  2694.9  332.31  4376.6  333.93  4690.2  330.67  4862.1  320.63  4897.6  308.77
  4960.9  303.78  4963.8  302.56  4966.1  294.64  4976.8  292.54  5014.2  294.64
  5014.9  299.95  5028.4  304.43  5064.8  306.24  5260.5  300.92  5328.2  307.58
  5939.1  324.04  6071.3  321.53  6149.4  311.62  6206.6  311.98  6403.3  327.01
  6553.2  332.16  7067.8  336.75  7132.4   337.1  7224.6  335.96    7512  334.59
  7599.2   340.9  7649.1  336.78  7851.7  336.96  7891.7  337.54  8641.6  348.08
#Mann= 9 ,-1 , 0
  2694.9      .1       0  4966.1     .07       0  5014.2      .1       0
  7067.8     .08       0  7132.4     .05       0  7224.6      .1       0
    7512     .08       0  7851.7     .05       0  7891.7      .1       0
Bank Sta=4966.1,5014.2
XS Rating Curve= 0 ,0
Exp/Cntr=0.3,0.1

Type RM Length L Ch R = 1 ,127456  ,2412,2412,2412
BEGIN DESCRIPTION:
San Miguel Creek 42.0
END DESCRIPTION:
XS GIS Cut Line= 3
      2082599.97     13423949.98        2079825.       13421775.
      2077744.55     13420533.48
#Sta/Elev= 30
  1457.7  331.94  1781.8  328.39  2508.6  330.14  3195.3  324.64  4267.9  323.87
  4364.1  316.36  4684.2  304.03  4929.7  304.18    4969  301.96  4980.3  298.27
  4980.8  293.16  4991.5  291.06  5018.2  291.06  5028.9  293.16  5031.1  300.38
  5110.9  301.56  5187.8  316.57  5219.9  320.45  5424.3  323.03  5450.5  319.18
  5508.9  315.72  5596.5  318.02  5756.1  329.09  5872.8  332.45  6008.1  334.71
  6172.6  329.89  6207.5   330.7  6795.8  337.91  6914.8  339.37  7406.2   345.4
#Mann= 6 ,-1 , 0
  1457.7      .1       0  4980.8     .07       0  5028.9      .1       0
  6207.5     .05       0  6795.8     .08       0  6914.8      .1       0
Bank Sta=4980.8,5028.9
XS Rating Curve= 0 ,0
Exp/Cntr=0.3,0.1

Type RM Length L Ch R = 1 ,125044  ,3224,3224,3224
BEGIN DESCRIPTION:
San Miguel Creek 41.0
END DESCRIPTION:
XS GIS Cut Line= 3
        2082850.       13423750.        2081575.       13420625.
      2080562.24     13418065.69
#Sta/Elev= 30
  1598.2  331.65  2151.6  327.41  2314.7     322  2346.1  325.44  2882.7  330.08
  3193.9  321.49  3254.3  316.96  3346.6  321.32  3691.4  323.31  4006.9  316.23
    4194  318.82    4349  308.43  4473.8  311.94  4723.3  305.29  4824.8  297.79
  4934.5  301.11  4985.5  297.63  4992.1  294.37  4994.9  288.43  5005.6  286.33
  5043.1  288.43  5045.9  299.51  5096.3  302.07  5147.7  322.04  5258.5  325.93
  6664.4  325.73  6846.5  322.18  7146.6  326.09  7621.7  326.34  7725.7  326.22
#Mann= 4 ,-1 , 0
  1598.2      .1       0  4994.9     .07       0  5043.1      .1       0
  7621.7     .08       0
Bank Sta=4994.9,5043.1
XS Rating Curve= 0 ,0
Exp/Cntr=0.3,0.1

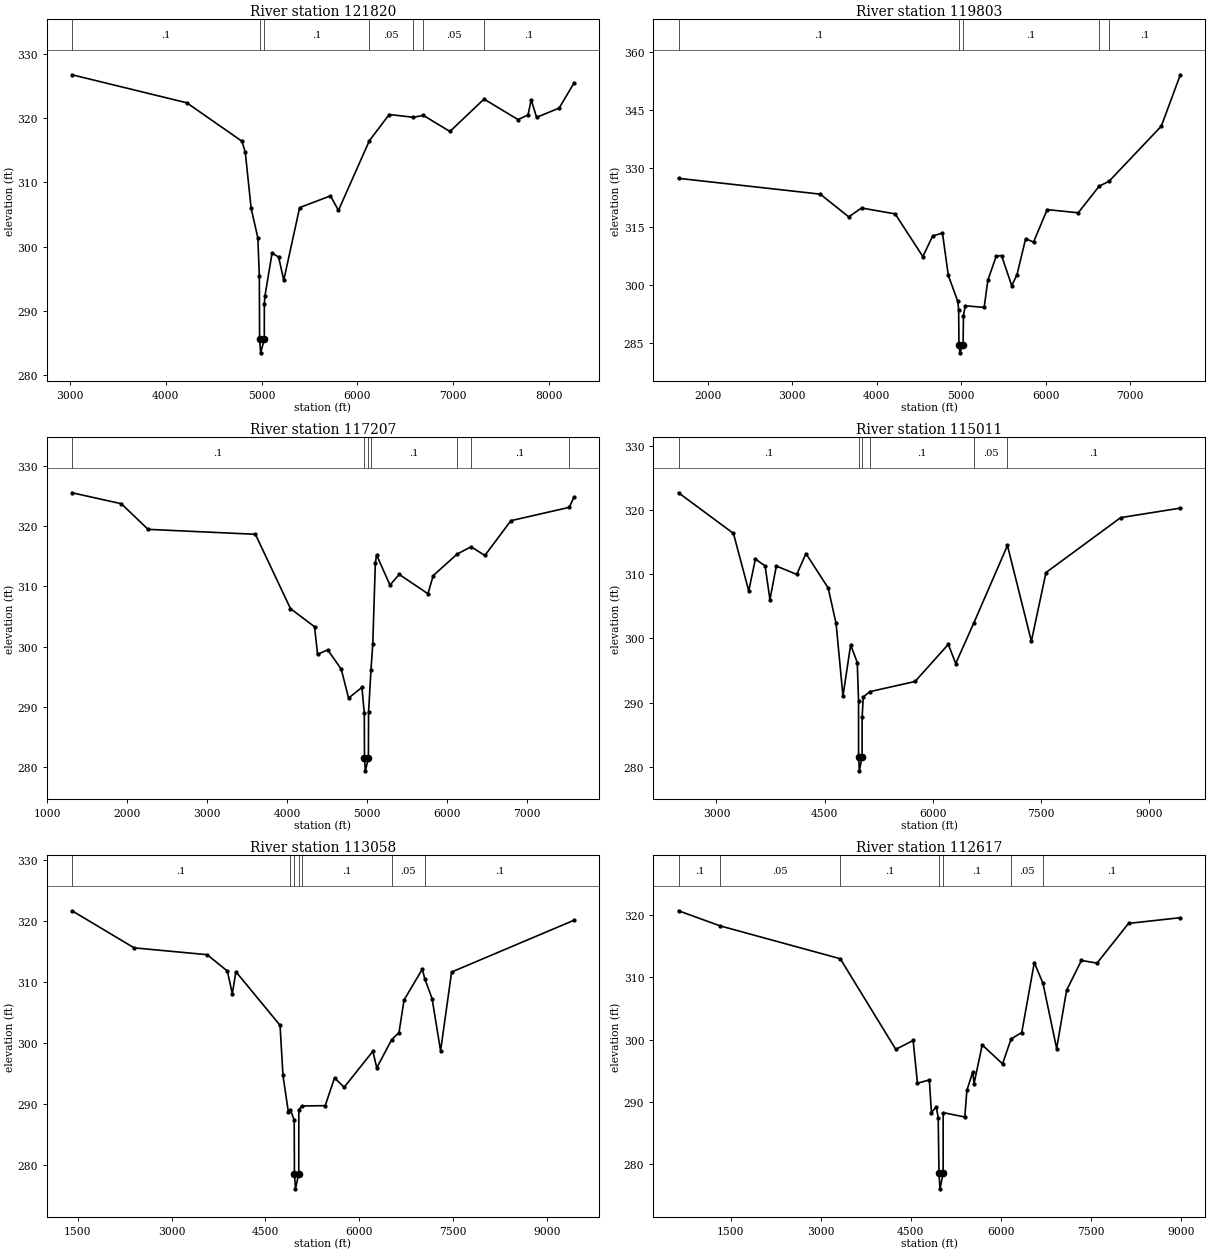
Type RM Length L Ch R = 1 ,121820  ,2017,2017,2017
BEGIN DESCRIPTION:
San Miguel Creek 40.0
END DESCRIPTION:
XS GIS Cut Line= 3
      2084650.01     13421700.03      2083947.62     13419810.71
      2082894.47     13416764.58
#Sta/Elev= 30
  3020.9  326.74  4218.5  322.38  4794.6   316.4  4829.1   314.7  4890.6  305.94
  4960.3  301.38    4976  295.43  4978.7  285.58  4989.7  283.48  5027.6  285.58
  5028.2  291.07  5034.3  292.29  5108.7  298.98  5177.5  298.39  5230.6  294.77
  5396.8  306.08  5718.8   307.9  5801.8  305.64  6124.3  316.47  6331.7  320.56
  6583.1  320.13  6688.6  320.42  6965.7  317.92  7321.7  322.96  7676.9  319.77
  7780.4  320.48  7814.5  322.83  7870.3  320.12  8105.4  321.55  8259.6  325.42
#Mann= 7 ,-1 , 0
  3020.9      .1       0  4978.7     .07       0  5027.6      .1       0
  6124.3     .05       0  6583.1     .08       0  6688.6     .05       0
  7321.7      .1       0
Bank Sta=4978.7,5027.6
XS Rating Curve= 0 ,0
Exp/Cntr=0.3,0.1

Type RM Length L Ch R = 1 ,119803  ,2596,2596,2596
BEGIN DESCRIPTION:
San Miguel Creek 39.0
END DESCRIPTION:
XS GIS Cut Line= 3
        2086050.     13422299.97       2085620.8     13418984.54
      2084754.58     13416538.49
#Sta/Elev= 30
  1656.9  327.45  3333.7  323.38    3671  317.53  3822.3  319.81  4220.6  318.29
  4548.3   307.3  4664.3  312.62  4780.2  313.35  4849.4  302.43  4961.7  295.75
  4971.8  293.59  4975.3  284.61  4986.3  282.51  5024.2  284.61  5028.7  292.11
  5049.9  294.63  5273.7  294.21  5317.3  301.22  5415.9  307.37  5479.3  307.56
  5600.2  299.79    5662  302.66  5764.8  311.93  5857.5  311.02  6019.4   319.4
  6386.6  318.58  6634.7  325.43  6751.3  326.69  7369.7  340.88  7594.9  354.12
#Mann= 5 ,-1 , 0
  1656.9      .1       0  4975.3     .07       0  5024.2      .1       0
  6634.7     .08       0  6751.3      .1       0
Bank Sta=4975.3,5024.2
XS Rating Curve= 0 ,0
Exp/Cntr=0.3,0.1

Type RM Length L Ch R = 1 ,117207  ,2196,2196,2196
BEGIN DESCRIPTION:
San Miguel Creek 38.0
END DESCRIPTION:
XS GIS Cut Line= 4
        2086350.     13422249.99      2087715.85     13418827.49
      2087774.02     13418691.34      2087640.01     13416251.05
#Sta/Elev= 30
    1309  325.54  1925.4  323.72  2259.2  319.47  3602.3  318.65  4041.1  306.31
    4342   303.3  4380.3  298.71  4506.4  299.47  4676.3  296.26  4767.9  291.45
  4934.7  293.23  4964.5  288.96    4967  281.48    4978  279.38    5016  281.48
  5017.9  289.11  5047.7  296.05  5070.5  300.41  5102.7  313.81  5117.7  315.24
  5286.1  310.21  5401.3  311.99  5760.9  308.78  5826.9   311.8  6126.7  315.37
  6300.6  316.58  6472.9  315.13  6798.4  320.91  7528.3  323.12    7586  324.79
#Mann= 7 ,-1 , 0
    1309      .1       0    4967     .07       0    5016      .1       0
  5047.7      .1       0  6126.7     .05       0  6300.6      .1       0
  7528.3     .08       0
Bank Sta=4967,5016
XS Rating Curve= 0 ,0
Exp/Cntr=0.3,0.1

Type RM Length L Ch R = 1 ,115011  ,1953,1953,1953
BEGIN DESCRIPTION:
San Miguel Creek 37.0
END DESCRIPTION:
XS GIS Cut Line= 4
      2087000.01       13422200.       2088880.8     13420514.54
      2089220.71      13419942.1      2088091.19     13416348.06
#Sta/Elev= 30
  2474.5  322.68  3235.9  316.35  3448.2  307.39  3540.2  312.36  3674.8  311.29
    3742  306.03  3830.6  311.27    4114  309.96  4241.4  313.21  4549.4  307.85
  4659.3  302.32  4754.6     291  4861.2  298.98  4953.1  296.23  4970.7  290.24
  4971.1  281.56    4982  279.36  5020.1  281.56  5020.4  287.68    5036  290.85
  5124.7  291.69  5754.4  293.28  6215.6  299.07  6318.2  296.08  6568.4  302.37
  7035.9  314.47  7367.6  299.55  7569.9  310.25  8605.7  318.81  9433.1  320.29
#Mann= 6 ,-1 , 0
  2474.5      .1       0  4971.1     .07       0  5020.1      .1       0
  5124.7      .1       0  6568.4     .05       0  7035.9      .1       0
Bank Sta=4971.1,5020.1
XS Rating Curve= 0 ,0
Exp/Cntr=0.3,0.1

Type RM Length L Ch R = 1 ,113058  ,441,441,441
BEGIN DESCRIPTION:
Mapping XS 047b1bdd
END DESCRIPTION:
XS GIS Cut Line= 6
      2090732.86     13423139.98      2090897.79     13420883.07
      2090828.35     13420535.85      2090385.64     13420058.42
      2089430.78     13419867.44      2088210.61     13416304.85
#Sta/Elev= 30
  1411.7  321.66  2402.9  315.59  3570.1  314.47  3892.4  311.79  3971.4  308.07
  4028.7  311.68  4733.9  302.91  4780.6  294.69  4866.7   288.7  4896.5  289.09
    4960  287.43  4963.8  278.63  4980.2  276.13  5032.8  278.63  5033.7  289.04
  5081.8   289.7  5455.6  289.75  5604.4  294.31  5757.8  292.76  6216.3  298.65
  6279.1  295.95  6517.8  300.57  6633.6  301.69  6714.5  307.04  7006.4  312.11
  7046.4  310.52  7162.8  307.26  7298.4  298.72  7474.2  311.63  9427.2   320.1
#Mann= 7 ,-1 , 0
  1411.7      .1       0  4896.5     .12       0  4963.8     .07       0
  5032.8     .12       0  5081.8      .1       0  6517.8     .05       0
  7046.4      .1       0
Bank Sta=4963.8,5032.8
XS Rating Curve= 0 ,0
Exp/Cntr=0.3,0.1

Type RM Length L Ch R = 1 ,112617  ,108,108,108
BEGIN DESCRIPTION:
Mapping XS 9239ffa1
END DESCRIPTION:
XS GIS Cut Line= 6
      2091102.03     13423087.23      2091370.96     13420401.65
      2090657.18     13419553.44      2089877.09     13419594.38
      2089476.63     13419536.08      2088329.96     13416391.64
#Sta/Elev= 30
   628.7   320.7  1322.4  318.27  3323.9  312.99  4248.4  298.42  4537.7  299.85
  4609.6  292.98  4807.7  293.51  4842.7  288.27  4922.9  289.18  4955.3  287.45
  4968.8   278.5  4985.3     276  5037.8   278.5  5038.3  288.25  5398.6  287.55
  5433.6  291.84  5531.3   294.8  5553.2  292.93    5689  299.14  6027.2  296.09
  6170.3   300.1  6347.4  301.13  6556.8  312.37  6701.3  309.03  6929.3  298.56
  7094.7  307.91  7341.2  312.71    7603  312.29  8126.4  318.67  8989.9  319.59
#Mann= 7 ,-1 , 0
   628.7      .1       0  1322.4     .05       0  3323.9      .1       0
  4968.8     .07       0  5037.8      .1       0  6170.3     .05       0
  6701.3      .1       0
Bank Sta=4968.8,5037.8
XS Rating Curve= 0 ,0
Exp/Cntr=0.3,0.1

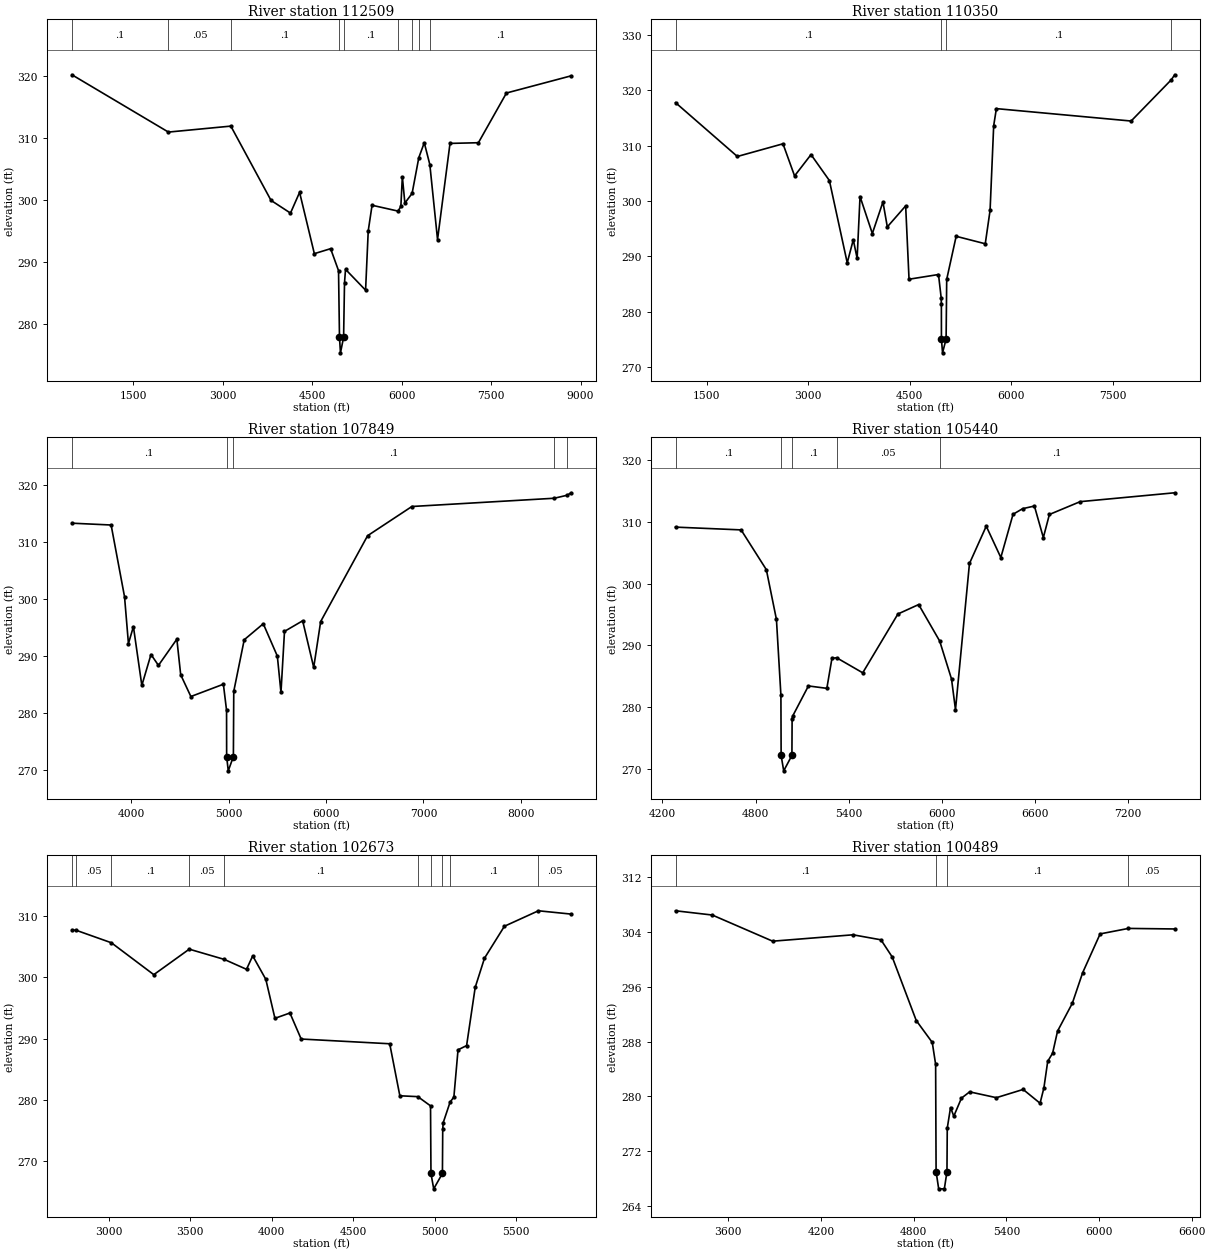
Type RM Length L Ch R = 1 ,112509  ,2159,2159,2159
BEGIN DESCRIPTION:
San Miguel Creek 36.0
END DESCRIPTION:
XS GIS Cut Line= 6
      2091253.95     13423032.94      2091499.14      13420345.7
      2090677.69     13419379.27      2090045.14     13419505.54
      2089665.88     13419451.33      2088471.04     13416304.87
#Sta/Elev= 30
   474.4  320.13  2091.2  310.92  3137.6  311.88  3811.3  299.94  4137.4   297.9
  4290.1  301.23  4537.4  291.38    4810  292.18  4942.8  288.65  4958.7  277.94
  4975.2  275.44  5027.7  277.94    5043  286.69    5060  288.86  5396.1  285.51
  5440.6  295.04  5504.7  299.16  5940.3  298.22  5987.5  298.98  6012.3  303.74
  6054.8  299.51  6175.9  301.07  6288.5  306.82  6379.9  309.21    6473   305.7
  6602.2  293.65  6811.2   309.1  7287.2  309.21  7757.3   317.2    8841  319.96
#Mann= 9 ,-1 , 0
   474.4      .1       0  2091.2     .05       0  3137.6      .1       0
  4958.7     .07       0  5027.7      .1       0  5940.3     .05       0
  6175.9      .1       0  6288.5     .05       0    6473      .1       0
Bank Sta=4958.7,5027.7
XS Rating Curve= 0 ,0
Exp/Cntr=0.3,0.1

Type RM Length L Ch R = 1 ,110350  ,2501,2501,2501
BEGIN DESCRIPTION:
San Miguel Creek 35.0
END DESCRIPTION:
XS GIS Cut Line= 3
      2093535.33     13421315.13        2091125.       13418175.
      2089112.41     13415417.62
#Sta/Elev= 30
  1041.7  317.76  1954.8  308.04  2628.7  310.33    2800  304.53  3042.9  308.38
  3313.9   303.7  3577.7  288.85    3667     293  3723.9  289.65  3766.7  300.81
  3948.4  294.13  4105.2  299.83  4169.6  295.33  4440.6  299.12  4490.4  285.88
  4925.5  286.73  4964.9  282.55  4968.1  281.35  4968.8  275.09  4985.3  272.59
  5037.9  275.09  5046.7  285.86  5186.4  293.63  5616.2  292.28  5687.3  298.31
  5740.6   313.6  5780.4  316.68  7770.4  314.44  8363.2  321.88    8414  322.79
#Mann= 4 ,-1 , 0
  1041.7      .1       0  4968.8     .07       0  5037.9      .1       0
  8363.2     .05       0
Bank Sta=4968.8,5037.9
XS Rating Curve= 0 ,0
Exp/Cntr=0.3,0.1

Type RM Length L Ch R = 1 ,107849  ,2409,2409,2409
BEGIN DESCRIPTION:
San Miguel Creek 34.0
END DESCRIPTION:
XS GIS Cut Line= 3
       2093943.9     13418491.91        2093075.       13417125.
      2091444.49     13414023.48
#Sta/Elev= 30
  3391.6  313.35  3793.8  313.03  3931.6  300.42  3971.5  292.21  4022.6  295.19
    4109  284.86    4203  290.29  4279.6  288.38  4468.5  292.98  4507.9  286.73
  4612.4  282.91  4946.1  285.07  4978.7  280.48  4979.6  272.36  4996.1  269.86
  5048.7  272.36  5052.6  283.82    5160  292.88  5355.5  295.69  5499.9  290.01
  5537.2  283.62  5573.4  294.35  5759.8  296.21  5873.2  288.02  5944.7  296.08
  6426.3  311.15    6881  316.28  8342.3  317.73  8475.1  318.26  8515.3  318.69
#Mann= 5 ,-1 , 0
  3391.6      .1       0  4979.6     .07       0  5048.7      .1       0
  8342.3     .05       0  8475.1     .08       0
Bank Sta=4979.6,5048.7
XS Rating Curve= 0 ,0
Exp/Cntr=0.3,0.1

Type RM Length L Ch R = 1 ,105440  ,2767,2767,2767
BEGIN DESCRIPTION:
San Miguel Creek 33.0
END DESCRIPTION:
XS GIS Cut Line= 3
      2095203.48     13416145.21        2094625.       13415775.
      2092520.48     13414370.22
#Sta/Elev= 30
  4284.1  309.19  4706.7  308.74  4869.4  302.29  4934.5  294.21  4963.3  281.92
  4964.7  272.16  4981.3  269.66  5034.2  272.16  5035.5  278.08    5040  278.59
  5140.6  283.43  5259.3  283.04  5292.3  287.91  5322.5     288  5490.6  285.56
  5717.4   295.1    5851  296.63  5986.6  290.71  6062.8  284.56  6088.4  279.58
  6178.5  303.29  6286.6  309.34  6380.6  304.26  6459.3  311.27  6520.9  312.18
    6597  312.61  6654.6  307.49  6693.6  311.24  6891.9  313.32  7501.2  314.76
#Mann= 5 ,-1 , 0
  4284.1      .1       0  4964.7     .07       0  5034.2      .1       0
  5322.5     .05       0  5986.6      .1       0
Bank Sta=4964.7,5034.2
XS Rating Curve= 0 ,0
Exp/Cntr=0.3,0.1

Type RM Length L Ch R = 1 ,102673  ,2184,2184,2184
BEGIN DESCRIPTION:
San Miguel Creek 32.0
END DESCRIPTION:
XS GIS Cut Line= 4
      2097369.05     13416003.68      2096553.06      13415317.9
       2096110.8     13414244.54      2095754.74     13413486.94
#Sta/Elev= 30
  2773.2  307.67  2800.8  307.61  3015.4  305.59  3275.6   300.4  3493.3  304.55
  3708.6  302.88  3844.7  301.27  3882.8  303.46  3963.2  299.64  4019.2  293.29
  4111.1  294.16  4180.2  289.92  4723.7  289.15  4785.9  280.68  4896.2  280.54
  4974.2  279.04  4976.9  268.03  4993.7  265.53  5047.2  268.03  5049.1  275.24
    5052   276.3  5094.3  279.65  5117.5  280.47    5143  288.16  5195.6  288.85
  5248.4  298.33  5305.4  303.08  5427.7  308.28  5636.4   310.8  5837.1  310.26
#Mann= 10 ,-1 , 0
  2773.2      .1       0  2800.8     .05       0  3015.4      .1       0
  3493.3     .05       0  3708.6      .1       0  4896.2     .12       0
  4976.9     .07       0  5047.2     .12       0  5094.3      .1       0
  5636.4     .05       0
Bank Sta=4976.9,5047.2
XS Rating Curve= 0 ,0
Exp/Cntr=0.3,0.1

Type RM Length L Ch R = 1 ,100489  ,3490,3490,3490
BEGIN DESCRIPTION:
San Miguel Creek 31.0
END DESCRIPTION:
XS GIS Cut Line= 3
      2098827.37      13415530.6        2098125.       13413925.
      2097079.86     13412877.26
#Sta/Elev= 30
  3257.9  307.05    3496  306.43  3886.9  302.62  4407.4  303.55  4588.2  302.82
  4661.1  300.32  4816.7  291.06  4920.4  287.87  4942.2  284.68  4945.2  269.04
    4962  266.54  4998.7  266.54  5015.6  269.04  5017.5  275.38  5038.7  278.38
  5059.9  277.13  5109.4  279.75  5162.4  280.67  5335.7  279.82  5508.9  281.02
  5618.5  279.01  5643.3  281.25    5668  285.11  5699.8  286.31  5731.7  289.52
  5827.1  293.56  5894.3  298.03  6007.4  303.68  6190.7  304.48  6490.3   304.4
#Mann= 4 ,-1 , 0
  3257.9      .1       0  4945.2     .07       0  5015.6      .1       0
  6190.7     .05       0
Bank Sta=4945.2,5015.6
XS Rating Curve= 0 ,0
Exp/Cntr=0.3,0.1