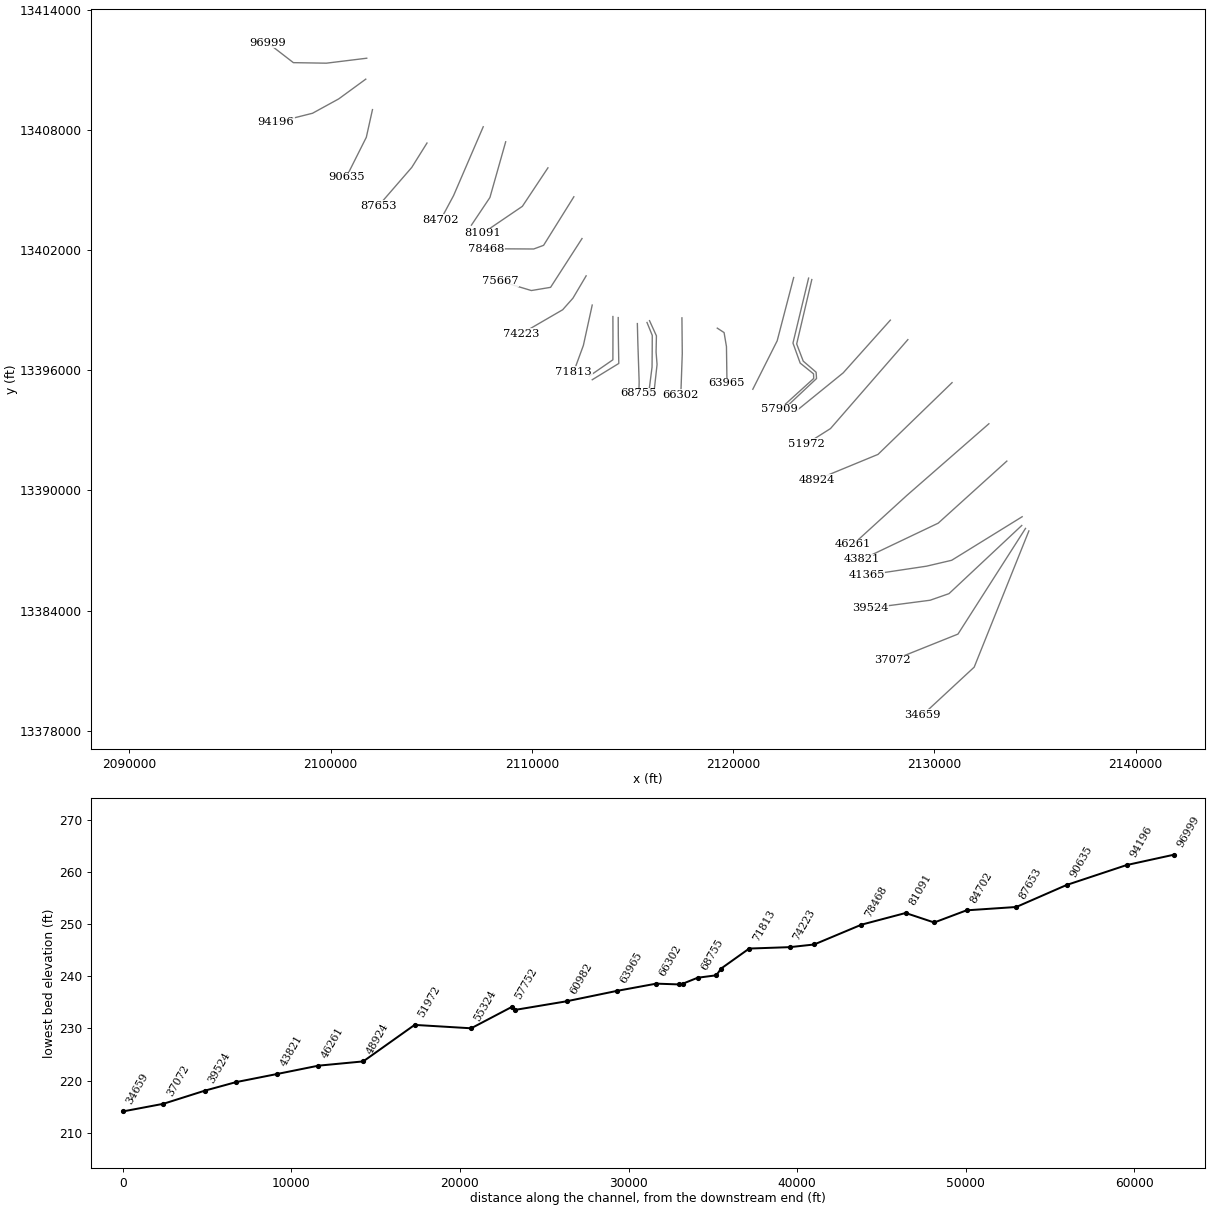
HEC-RAS study San Miguel Creek.prj: San Miguel Creek Base Level Engineering

--- San Miguel Creek.g01 (geometry) --- (continued)

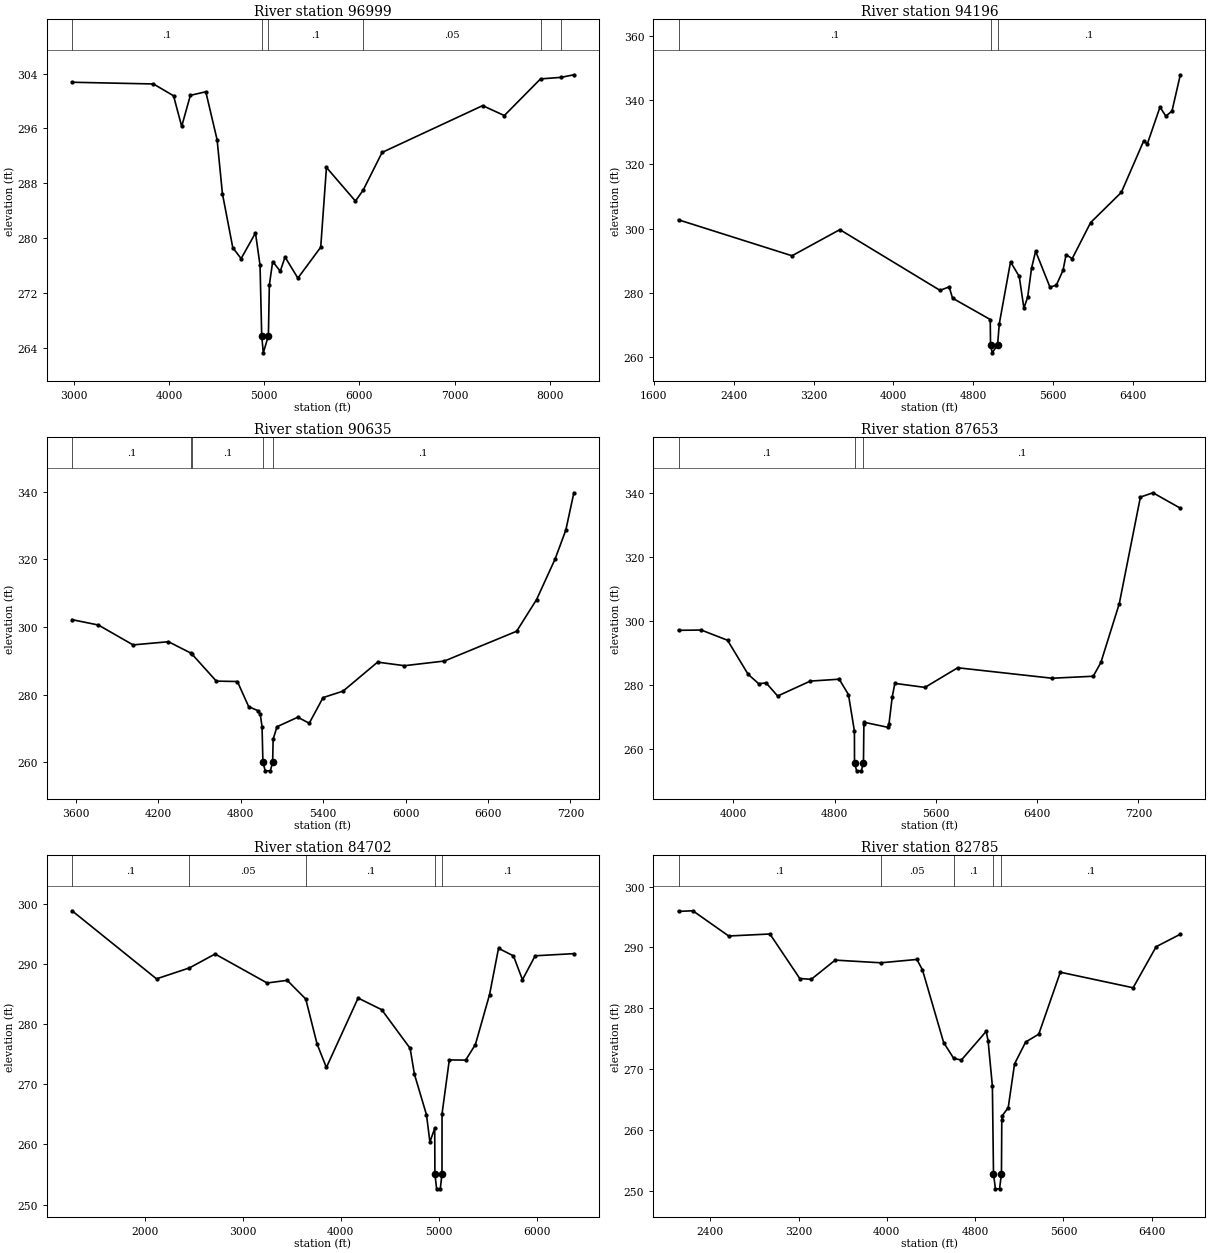
Type RM Length L Ch R = 1 ,96999   ,2803,2803,2803
BEGIN DESCRIPTION:
San Miguel Creek 30.0
END DESCRIPTION:
XS GIS Cut Line= 4
      2101796.16     13411572.25       2099790.8     13411324.54
      2098150.28     13411350.89      2096874.89     13412339.96
#Sta/Elev= 30
  2979.4  302.74  3834.5  302.49  4046.1  300.77  4131.7   296.3  4223.1  300.83
  4385.3  301.35  4504.4  294.33    4560  286.49  4669.1   278.6  4756.5  277.01
  4907.6  280.75  4955.5  276.04  4973.1  265.76  4989.9  263.26  5043.5  265.76
  5053.3  273.14  5088.3  276.58  5168.3  275.17  5218.3  277.24  5353.3  274.16
  5593.4  278.67  5653.7  290.31  5958.4   285.4  6039.4  286.99  6238.5   292.5
    7296  299.33  7523.7  297.88  7904.4  303.23  8118.2  303.45  8254.7  303.83
#Mann= 6 ,-1 , 0
  2979.4      .1       0  4973.1     .07       0  5043.5      .1       0
  6039.4     .05       0  7904.4      .1       0  8118.2     .05       0
Bank Sta=4973.1,5043.5
XS Rating Curve= 0 ,0
Exp/Cntr=0.3,0.1

Type RM Length L Ch R = 1 ,94196   ,3561,3561,3561
BEGIN DESCRIPTION:
San Miguel Creek 28.0
END DESCRIPTION:
XS GIS Cut Line= 4
      2101747.39      13410527.2      2100402.88     13409540.99
       2099100.8     13408824.54       2097282.7      13408364.9
#Sta/Elev= 30
  1846.4   302.7  2983.5  291.51  3463.2  299.65  4467.3  280.73  4558.6  281.83
  4592.3  278.31  4970.2  271.66  4973.3  263.78  4990.2  261.28  5043.9  263.78
    5061  270.34  5173.6  289.61    5261  285.07  5307.7  275.17  5345.6  278.66
  5384.1  287.62  5425.1  292.93  5568.7  281.74  5632.8  282.36  5699.6  286.96
  5730.3  291.83  5791.8  290.62  5976.4  301.85  6284.1  311.25  6507.2   327.2
  6545.4  326.41  6671.3   337.8  6730.3  334.99  6791.8  336.58  6875.3  347.87
#Mann= 3 ,-1 , 0
  1846.4      .1       0  4973.3     .07       0  5043.9      .1       0
Bank Sta=4973.3,5043.9
XS Rating Curve= 0 ,0
Exp/Cntr=0.3,0.1

Type RM Length L Ch R = 1 ,90635   ,2982,2982,2982
BEGIN DESCRIPTION:
San Miguel Creek 27.0
END DESCRIPTION:
XS GIS Cut Line= 3
      2102081.23     13409007.46        2101775.       13407625.
      2100775.02     13405625.03
#Sta/Elev= 30
  3573.1  302.16  3764.4  300.58  4017.1   294.7  4274.8  295.64  4436.3   292.3
  4447.9  291.88  4622.9  283.99  4776.5  283.87  4858.5  276.43  4925.1  275.26
  4942.9  274.14  4955.8  270.52  4962.1  259.96  4979.1  257.46  5015.9  257.46
  5032.8  259.96  5036.6  266.83  5064.5   270.5  5215.5  273.31  5299.3  271.54
  5399.9  279.12  5545.3  281.03  5796.8   289.6  5992.5  288.55  6283.2  289.93
  6808.7  298.74    6954  308.12  7088.2  320.07  7166.4  328.61  7225.1  339.68
#Mann= 5 ,-1 , 0
  3573.1      .1       0  4436.3     .08       0  4447.9      .1       0
  4962.1     .07       0  5032.8      .1       0
Bank Sta=4962.1,5032.8
XS Rating Curve= 0 ,0
Exp/Cntr=0.3,0.1

Type RM Length L Ch R = 1 ,87653   ,2951,2951,2951
BEGIN DESCRIPTION:
San Miguel Creek 26.0
END DESCRIPTION:
XS GIS Cut Line= 3
      2104789.74     13407337.94       2104033.6     13406121.74
      2102380.01     13404204.93
#Sta/Elev= 30
  3567.9  297.18  3747.7  297.26  3954.9  294.07  4117.8  283.41  4201.6  280.48
  4259.5  280.75    4351  276.64  4608.3   281.3  4836.8   281.9    4910   277.1
  4957.2  265.67  4957.9  255.75  4974.8  253.25  5011.6  253.25  5028.6  255.75
    5032  267.76  5035.7  268.41    5220  266.87  5230.5  267.99  5255.7  276.31
  5276.5  280.59  5514.1  279.33  5772.9  285.47  6517.8   282.2  6843.6  282.82
    6904  287.12  7049.3  305.51  7216.1  338.82  7315.3  340.17  7531.5  335.35
#Mann= 3 ,-1 , 0
  3567.9      .1       0  4957.9     .07       0  5028.6      .1       0
Bank Sta=4957.9,5028.6
XS Rating Curve= 0 ,0
Exp/Cntr=0.3,0.1

Type RM Length L Ch R = 1 ,84702   ,1917,1917,1917
BEGIN DESCRIPTION:
San Miguel Creek 25.0
END DESCRIPTION:
XS GIS Cut Line= 3
      2107584.74     13408150.43       2106110.8     13404714.54
      2105462.36     13403499.32
#Sta/Elev= 30
  1261.3  298.94  2122.2   287.6  2457.9  289.42  2719.5  291.74  3249.7  286.91
  3454.5  287.35  3643.9  284.24  3759.1  276.75  3854.2  272.83  4177.8   284.4
    4418  282.46    4708  276.02  4751.9  271.71  4874.8  264.95  4909.7  260.42
  4958.7  262.69  4960.7  255.11    4978  252.61  5015.5  252.61  5032.8  255.11
  5033.5  265.12  5107.5  274.09  5274.3  274.06  5373.5  276.65    5518  284.98
  5609.3  292.69  5761.7  291.42  5853.3  287.45  5982.8  291.44  6377.4   291.8
#Mann= 5 ,-1 , 0
  1261.3      .1       0  2457.9     .05       0  3643.9      .1       0
  4960.7     .07       0  5032.8      .1       0
Bank Sta=4960.7,5032.8
XS Rating Curve= 0 ,0
Exp/Cntr=0.3,0.1

Type RM Length L Ch R = 1 ,82785   ,1694,1694,1694
BEGIN DESCRIPTION:
San Miguel Creek 24.0
END DESCRIPTION:
XS GIS Cut Line= 3
        2108700.     13407399.98      2107917.48     13404620.54
      2106997.45     13403239.54
#Sta/Elev= 30
  2112.5  295.94    2242  296.04    2567  291.89  2940.6  292.22  3211.1  284.89
    3315  284.76  3531.8  287.92  3945.6  287.48  4272.2  288.03  4322.7  286.32
  4514.9  274.35  4605.7  271.76  4675.2  271.47  4900.2   276.2  4917.2  274.69
  4956.4  267.18  4966.5  252.78  4983.8  250.28  5021.3  250.28  5038.6  252.78
  5041.6   261.6  5045.7  262.31  5099.8  263.63  5157.3  270.85    5258  274.44
  5376.7  275.74    5572  285.93  6231.6  283.37  6440.5  290.13  6659.4  292.18
#Mann= 5 ,-1 , 0
  2112.5      .1       0  3945.6     .05       0  4605.7      .1       0
  4966.5     .07       0  5038.6      .1       0
Bank Sta=4966.5,5038.6
XS Rating Curve= 0 ,0
Exp/Cntr=0.3,0.1

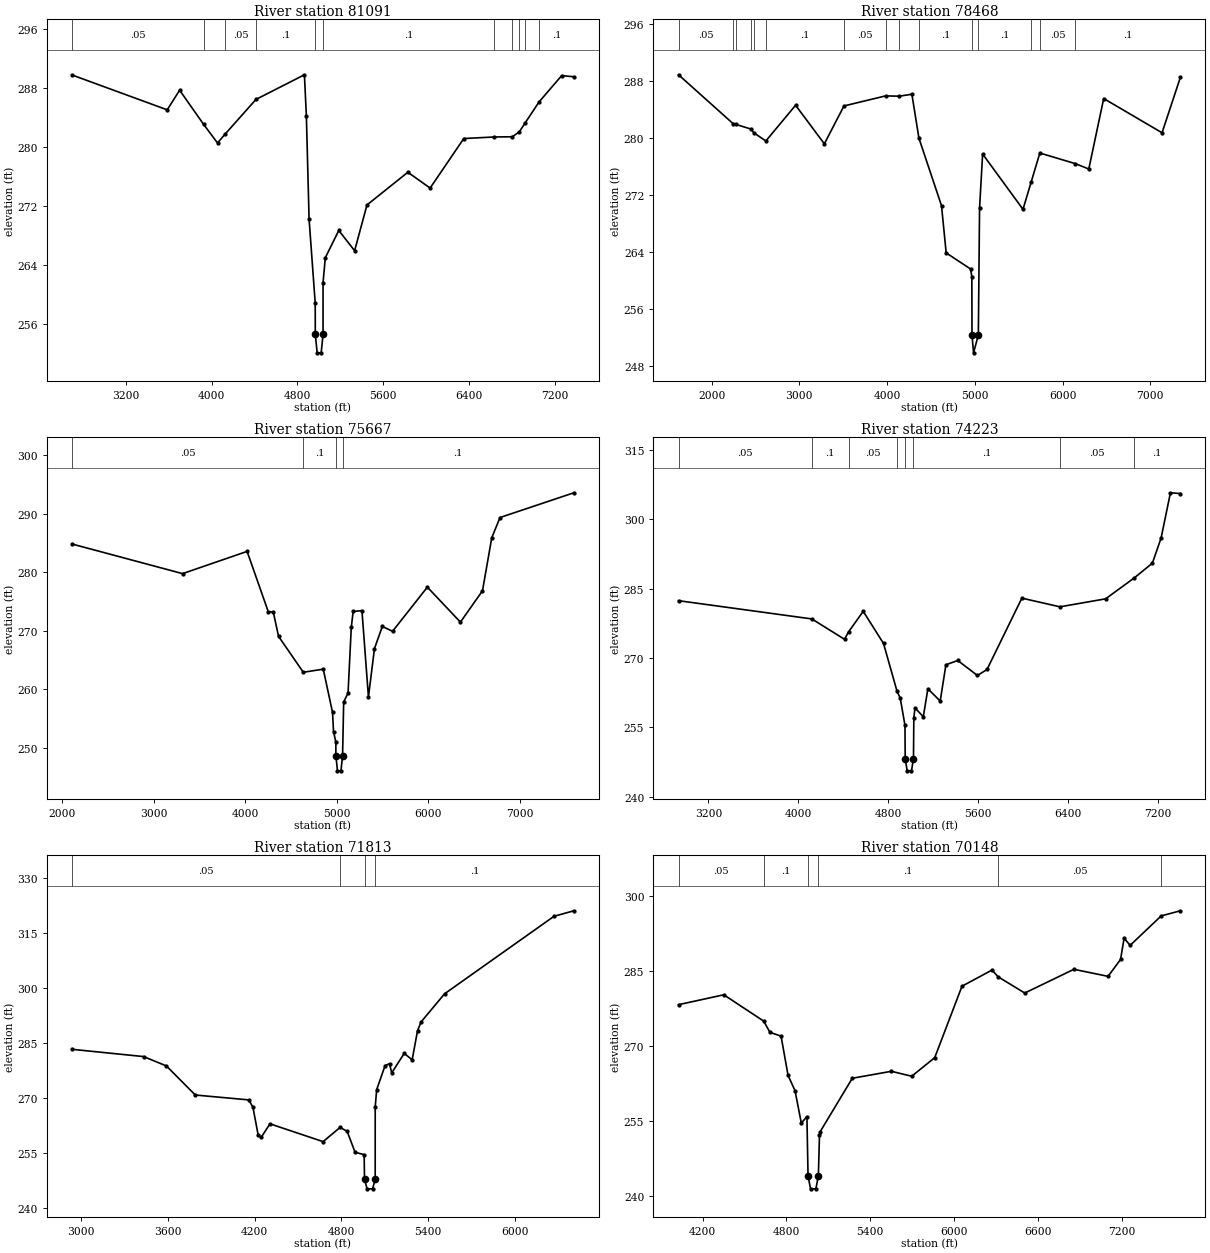
Type RM Length L Ch R = 1 ,81091   ,2623,2623,2623
BEGIN DESCRIPTION:
San Miguel Creek 23.0
END DESCRIPTION:
XS GIS Cut Line= 3
      2110800.01     13406100.01      2109529.89     13404178.91
      2107564.47     13402837.06
#Sta/Elev= 30
    2697  289.75  3584.8  285.03  3700.7  287.69  3923.7  283.08  4054.3  280.54
  4128.3  281.79    4413  286.44  4865.3  289.78  4883.4  284.24    4909  270.19
  4966.1  258.82  4966.9   254.6  4984.2   252.1  5021.7   252.1  5039.1   254.6
  5039.2  261.61  5060.3  264.99  5185.9  268.68  5333.9  265.94  5449.1  272.14
  5830.5  276.57  6038.4  274.43  6352.4  281.14  6633.2  281.35  6805.2  281.38
  6871.1  282.05  6921.7  283.18  7054.4  286.09  7266.2  289.67  7379.8  289.51
#Mann= 11 ,-1 , 0
    2697     .05       0  3923.7      .1       0  4128.3     .05       0
    4413      .1       0  4966.9     .07       0  5039.1      .1       0
  6633.2     .05       0  6805.2     .08       0  6871.1      .1       0
  6921.7     .05       0  7054.4      .1       0
Bank Sta=4966.9,5039.1
XS Rating Curve= 0 ,0
Exp/Cntr=0.3,0.1

Type RM Length L Ch R = 1 ,78468   ,2801,2801,2801
BEGIN DESCRIPTION:
San Miguel Creek 22.0
END DESCRIPTION:
XS GIS Cut Line= 4
      2112087.74     13404655.07      2110583.47     13402231.67
      2110091.96     13402048.92      2107749.09     13402061.34
#Sta/Elev= 30
  1623.3  288.84  2243.3  282.01  2274.7  281.89  2452.2  281.22  2480.1  280.72
  2618.7  279.56  2957.5  284.57  3285.3  279.16  3508.9  284.47  3983.6  285.88
  4138.9  285.84  4283.2  286.11  4363.2  279.96  4620.7  270.49    4674  263.87
  4951.3  261.62  4966.5  260.55  4968.4  252.36  4985.7  249.86  5040.6  252.36
  5054.5  270.16  5089.5  277.73  5549.5  269.98  5643.3  273.83  5741.6  277.87
  6147.1  276.38  6299.5  275.63  6469.5  285.51  7134.5  280.71  7342.9  288.46
#Mann= 15 ,-1 , 0
  1623.3     .05       0  2243.3     .08       0  2274.7     .05       0
  2452.2     .08       0  2480.1     .05       0  2618.7      .1       0
  3508.9     .05       0  3983.6      .1       0  4138.9     .05       0
  4363.2      .1       0  4968.4     .07       0  5040.6      .1       0
  5643.3     .08       0  5741.6     .05       0  6147.1      .1       0
Bank Sta=4968.4,5040.6
XS Rating Curve= 0 ,0
Exp/Cntr=0.3,0.1

Type RM Length L Ch R = 1 ,75667   ,1444,1444,1444
BEGIN DESCRIPTION:
San Miguel Creek 21.0
END DESCRIPTION:
XS GIS Cut Line= 4
      2112493.03     13402569.94       2110930.8     13400134.54
      2109975.84     13399974.72      2108421.76     13400444.61
#Sta/Elev= 30
  2106.6  284.84  3314.6  279.78  4019.9  283.58  4251.5  273.26    4306  273.23
  4363.5  269.06  4634.2  262.92  4852.5  263.45  4953.9  256.05  4964.5  252.78
  4990.2  250.97  4990.3  248.67    5008  246.07  5045.9  246.07  5063.5  248.67
  5075.7  257.86  5123.3  259.35  5158.7  270.58    5179  273.31  5275.3  273.46
  5346.3   258.7  5412.2  266.97  5498.1  270.76  5609.9  269.92  5990.3  277.47
  6351.9  271.49    6593  276.85  6694.4  285.91  6784.6  289.37  7591.8   293.6
#Mann= 4 ,-1 , 0
  2106.6     .05       0  4634.2      .1       0  4990.3     .07       0
  5063.5      .1       0
Bank Sta=4990.3,5063.5
XS Rating Curve= 0 ,0
Exp/Cntr=0.3,0.1

Type RM Length L Ch R = 1 ,74223   ,2410,2410,2410
BEGIN DESCRIPTION:
San Miguel Creek 20.0
END DESCRIPTION:
XS GIS Cut Line= 4
       2112698.3      13400707.9      2112041.81     13399592.78
       2111530.8     13399014.54      2109455.34     13397804.78
#Sta/Elev= 30
  2934.3  282.41  4121.2  278.46  4412.2  274.05  4448.6  275.67  4578.7   280.1
  4759.4  273.15  4879.9  262.79  4908.3  261.31  4950.5  255.42  4952.5  248.16
  4970.3  245.56  5008.5  245.56  5026.3  248.16  5029.4  257.06  5040.1  259.19
  5113.8  257.27  5154.3  263.32  5264.3  260.68  5315.1  268.53  5420.5  269.46
  5595.9  266.21  5680.9  267.51  5991.3  282.96  6330.4  281.08  6736.9  282.81
  6992.3  287.34  7153.7  290.54  7231.1  295.99  7314.2  305.78  7402.3  305.61
#Mann= 8 ,-1 , 0
  2934.3     .05       0  4121.2      .1       0  4448.6     .05       0
  4879.9      .1       0  4952.5     .07       0  5026.3      .1       0
  6330.4     .05       0  6992.3      .1       0
Bank Sta=4952.5,5026.3
XS Rating Curve= 0 ,0
Exp/Cntr=0.3,0.1

Type RM Length L Ch R = 1 ,71813   ,1665,1665,1665
BEGIN DESCRIPTION:
San Miguel Creek 19.0
END DESCRIPTION:
XS GIS Cut Line= 3
      2113000.01     13399250.04       2112560.8     13397234.54
      2112077.65     13395911.92
#Sta/Elev= 30
  2937.2   283.3    3432  281.32  3589.7  278.77  3789.3  270.85  4159.3  269.52
  4188.4  267.51  4224.2  259.98  4244.7  259.28  4306.1     263  4673.5  258.15
  4791.5  262.03  4840.1  260.94  4894.6  255.26  4957.7  254.59    4960  247.89
  4977.9  245.29  5016.1  245.29  5033.9  247.89  5034.1   267.6  5044.1   272.3
  5102.5  278.89    5133  279.38  5148.3  276.88  5234.6  282.19  5289.6  280.44
  5326.9  288.39  5351.4  290.76  5514.1  298.43  6270.9  319.54  6408.1  321.04
#Mann= 4 ,-1 , 0
  2937.2     .05       0  4791.5      .1       0    4960     .07       0
  5033.9      .1       0
Bank Sta=4960,5033.9
XS Rating Curve= 0 ,0
Exp/Cntr=0.3,0.1

Type RM Length L Ch R = 1 ,70148   ,283,283,283
BEGIN DESCRIPTION:
Mapping XS 97483d2b
END DESCRIPTION:
XS GIS Cut Line= 4
      2114028.07     13398676.53       2114030.8     13397704.54
      2114026.89      13396517.3      2112849.99     13395699.99
#Sta/Elev= 30
    4028  278.31    4352  280.29  4637.8  275.02    4682  272.79    4762  272.01
    4812  264.17    4862  261.09    4907  254.61    4947  255.92  4955.1  244.06
  4972.9  241.46  5011.2  241.46    5029  244.06    5037  252.16    5042   252.9
    5272  263.59    5552  264.98    5697  263.99    5862  267.71    6057     282
  6272.5  285.25  6314.5  283.91  6506.5  280.64  6858.3  285.39  7102.8  283.98
  7192.3  287.36  7217.6  291.62  7260.8  290.18    7483  296.07  7620.1   297.1
#Mann= 6 ,-1 , 0
    4028     .05       0  4637.8      .1       0  4955.1     .07       0
    5029      .1       0  6314.5     .05       0    7483     .08       0
Bank Sta=4955.1,5029
XS Rating Curve= 0 ,0
Exp/Cntr=0.3,0.1

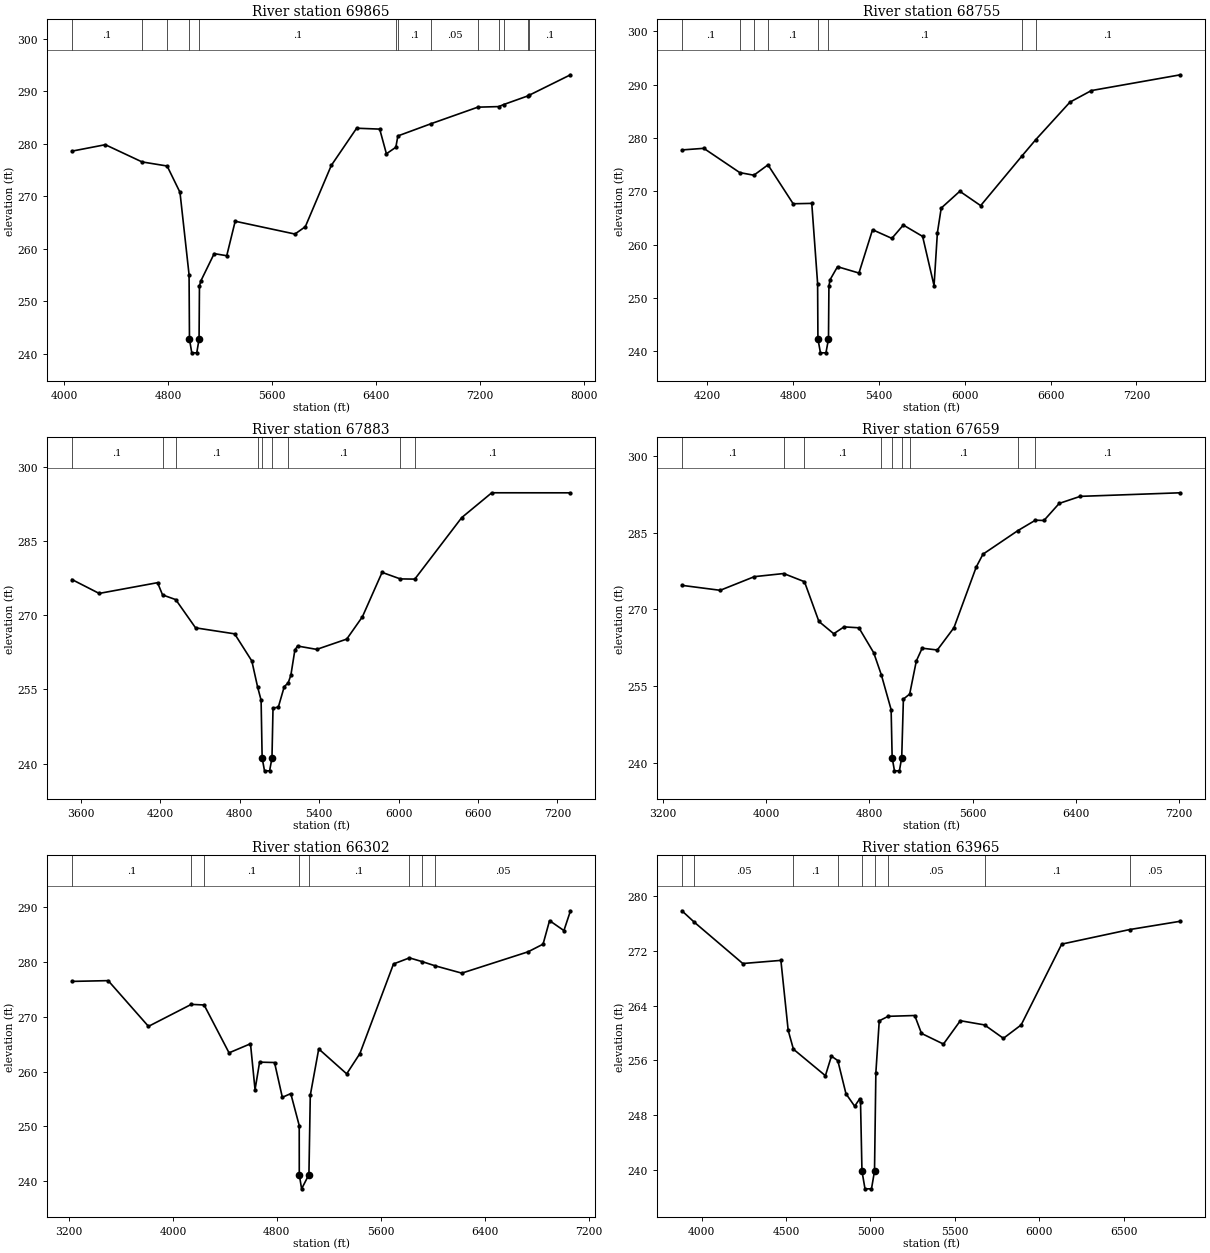
Type RM Length L Ch R = 1 ,69865   ,1110,1110,1110
BEGIN DESCRIPTION:
Mapping XS 61561cef
END DESCRIPTION:
XS GIS Cut Line= 4
      2114292.35     13398624.62      2114296.72     13397716.58
      2114320.75     13396335.04      2113001.65     13395522.45
#Sta/Elev= 30
  4059.9  278.59    4317  279.82    4600  276.54  4793.1  275.76    4892  270.75
    4962  255.05  4965.1  242.77  4982.9  240.17  5021.2  240.17    5039  242.77
    5042  252.91    5052  253.83  5155.4  259.07  5252.1  258.67  5317.1  265.24
  5777.2   262.8  5857.2   264.2  6057.2  275.87  6252.2  282.96  6429.9  282.79
  6481.5  278.09  6554.1  279.33  6569.9  281.49  6827.7  283.84  7185.3  286.97
    7347  287.08  7383.3  287.46  7573.6  289.14  7581.4  289.25    7899  293.14
#Mann= 13 ,-1 , 0
  4059.9      .1       0    4600     .05       0  4793.1      .1       0
  4965.1     .07       0    5039      .1       0  6554.1     .08       0
  6569.9      .1       0  6827.7     .05       0  7185.3      .1       0
    7347     .08       0  7383.3     .05       0  7573.6     .08       0
  7581.4      .1       0
Bank Sta=4965.1,5039
XS Rating Curve= 0 ,0
Exp/Cntr=0.3,0.1

Type RM Length L Ch R = 1 ,68755   ,872,872,872
BEGIN DESCRIPTION:
Mapping XS c64325df
END DESCRIPTION:
XS GIS Cut Line= 4
      2115242.87     13398325.57      2115267.01     13397378.14
      2115332.12     13395425.02       2115319.1     13394839.51
#Sta/Elev= 30
  4021.4  277.74  4174.5  278.04  4426.2  273.49  4524.8     273  4623.5  274.94
  4799.7  267.65  4929.8  267.72  4970.7  252.69  4972.9   242.3  4990.7   239.7
    5029   239.7  5046.8   242.3  5049.8  252.21  5058.1  253.42  5109.9  255.85
  5259.9  254.66    5355  262.78  5490.1  261.16  5570.1  263.66  5705.2  261.53
  5785.2  252.29  5808.5   262.2  5835.3  266.84  5965.3  269.99  6111.2   267.3
  6398.8  276.57  6497.4  279.69  6735.8   286.7  6885.8  288.87    7509  291.83
#Mann= 8 ,-1 , 0
  4021.4      .1       0  4426.2     .08       0  4524.8     .05       0
  4623.5      .1       0  4972.9     .07       0  5046.8      .1       0
  6398.8     .08       0  6497.4      .1       0
Bank Sta=4972.9,5046.8
XS Rating Curve= 0 ,0
Exp/Cntr=0.3,0.1

Type RM Length L Ch R = 1 ,67883   ,224,224,224
BEGIN DESCRIPTION:
San Miguel Creek 18.0
END DESCRIPTION:
XS GIS Cut Line= 5
       2115722.6     13398380.61      2115984.05     13397734.83
       2115980.8     13396964.54      2115973.05     13396151.87
      2115785.86     13394677.51
#Sta/Elev= 30
    3533   277.2  3738.9  274.39  4179.9  276.56  4217.7  274.09  4317.2  273.14
    4467  267.44    4762  266.23    4892  260.75  4935.7  255.49    4962  252.83
  4969.9  241.17  4987.8  238.57  5026.2  238.57  5044.1  241.17    5052  251.25
    5092  251.42    5137  255.58  5166.3  256.31    5187   257.9    5217  262.95
    5237  263.77  5382.1  263.09  5608.8  265.17  5727.1  269.67  5875.8  278.64
  6013.3  277.32  6122.9  277.28  6477.4   289.7  6704.2  294.71  7298.9   294.7
#Mann= 9 ,-1 , 0
    3533      .1       0  4217.7     .08       0  4317.2      .1       0
  4935.7     .12       0  4969.9     .07       0  5044.1     .12       0
  5166.3      .1       0  6013.3     .08       0  6122.9      .1       0
Bank Sta=4969.9,5044.1
XS Rating Curve= 0 ,0
Exp/Cntr=0.3,0.1

Type RM Length L Ch R = 1 ,67659   ,1357,1357,1357
BEGIN DESCRIPTION:
Mapping XS 13b44e21
END DESCRIPTION:
XS GIS Cut Line= 5
      2115847.58     13398470.94      2116190.63      13397713.9
      2116173.57     13396901.35      2116222.18      13396283.3
      2116047.64     13394689.66
#Sta/Elev= 30
  3345.7  274.69  3642.7  273.72  3907.7  276.39  4135.1     277  4296.4   275.4
  4408.3  267.63  4523.3  265.23  4603.3  266.57  4718.4  266.39  4833.4  261.51
  4892.7  257.18  4968.4  250.39  4976.4  241.02  4994.3  238.42  5032.7  238.42
  5050.6  241.02  5063.6  252.45  5112.3  253.43    5164  259.91  5209.1   262.4
  5326.8  262.05  5455.8  266.41  5628.7  278.28  5680.7  280.78  5951.9   285.4
  6087.8  287.43  6153.6  287.37  6272.1  290.71  6435.2  292.09  7212.7  292.79
#Mann= 9 ,-1 , 0
  3345.7      .1       0  4135.1     .05       0  4296.4      .1       0
  4892.7     .12       0  4976.4     .07       0  5050.6     .12       0
  5112.3      .1       0  5951.9     .08       0  6087.8      .1       0
Bank Sta=4976.4,5050.6
XS Rating Curve= 0 ,0
Exp/Cntr=0.3,0.1

Type RM Length L Ch R = 1 ,66302   ,2337,2337,2337
BEGIN DESCRIPTION:
San Miguel Creek 17.0
END DESCRIPTION:
XS GIS Cut Line= 3
      2117458.12     13398611.56        2117475.       13396825.
      2117403.15      13394776.5
#Sta/Elev= 30
  3222.9  276.49    3502  276.63    3812  268.27  4141.5  272.29  4240.1  272.18
    4432  263.43    4597  265.09    4632   256.7    4667  261.73    4782  261.66
    4842   255.3    4907  255.98    4972  250.14  4972.4  241.17  4990.3  238.57
  5046.6  241.17  5057.1  255.67  5122.1  264.15  5337.2  259.59  5438.6  263.29
  5697.5  279.68  5820.1  280.79    5919   280.1  6017.8  279.34  6222.8     278
  6733.1   281.9  6848.2   283.3  6898.2   287.6  7008.7  285.78  7059.3   289.4
#Mann= 8 ,-1 , 0
  3222.9      .1       0  4141.5     .08       0  4240.1      .1       0
  4972.4     .07       0  5046.6      .1       0  5820.1     .05       0
    5919     .08       0  6017.8     .05       0
Bank Sta=4972.4,5046.6
XS Rating Curve= 0 ,0
Exp/Cntr=0.3,0.1

Type RM Length L Ch R = 1 ,63965   ,2983,2983,2983
BEGIN DESCRIPTION:
San Miguel Creek 16.0
END DESCRIPTION:
XS GIS Cut Line= 4
      2119214.15     13398097.85      2119552.67     13397876.51
       2119670.8     13397174.54      2119697.16     13395339.33
#Sta/Elev= 30
  3883.7  277.88  3957.5   276.2  4244.2  270.16  4469.7  270.62  4512.9  260.38
  4543.9  257.62  4733.3  253.74  4768.8   256.6  4806.7  255.95    4855   251.1
  4906.5  249.27  4936.8  250.37  4941.2  249.85  4949.7  239.78  4967.7  237.18
  5006.1  237.18    5024  239.78    5032  254.18    5052  261.77  5104.4  262.43
  5262.1  262.55  5302.1  259.93  5432.1  258.37  5532.1  261.79  5675.6  261.17
  5787.1  259.21  5892.1  261.17  6132.2     273  6534.2  275.13  6835.4  276.35
#Mann= 9 ,-1 , 0
  3883.7      .1       0  3957.5     .05       0  4543.9      .1       0
  4806.7     .12       0  4949.7     .07       0    5024     .12       0
  5104.4     .05       0  5675.6      .1       0  6534.2     .05       0
Bank Sta=4949.7,5024
XS Rating Curve= 0 ,0
Exp/Cntr=0.3,0.1

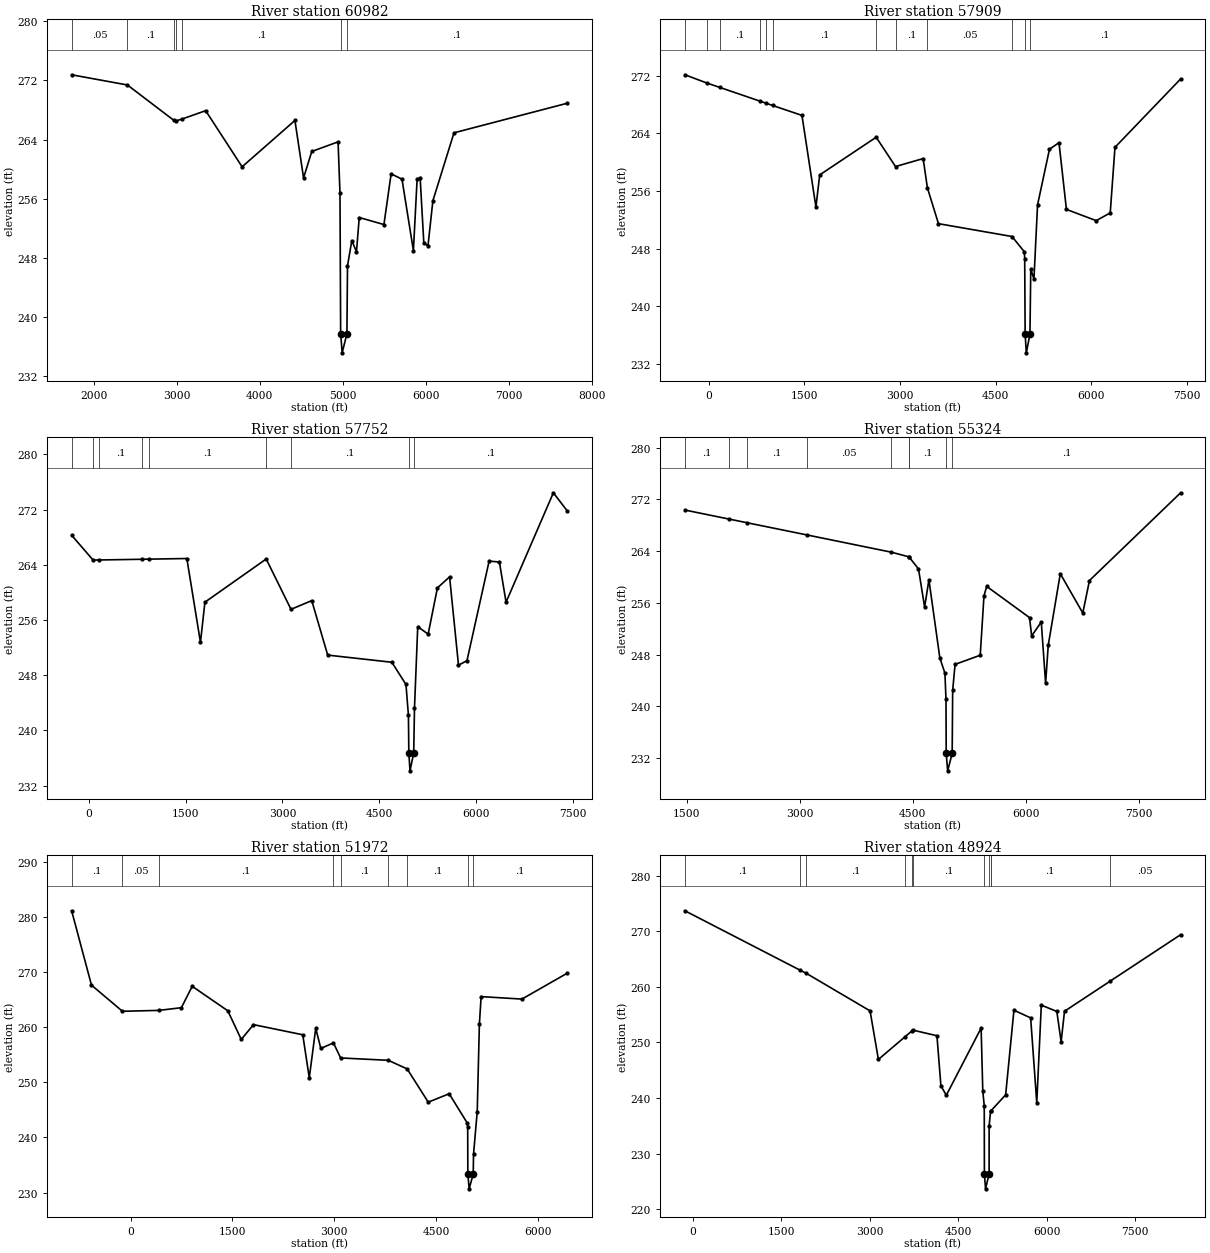
Type RM Length L Ch R = 1 ,60982   ,3073,3073,3073
BEGIN DESCRIPTION:
San Miguel Creek 15.0
END DESCRIPTION:
XS GIS Cut Line= 3
      2123011.36     13400624.23       2122190.8     13397464.54
      2120979.91     13395047.38
#Sta/Elev= 30
  1735.5  272.75  2407.2  271.37  2966.4  266.59    2989  266.51  3069.2  266.79
    3349   267.9  3787.7  260.32  4423.5  266.58  4527.6  258.82  4626.4  262.39
  4943.1  263.69    4966  256.73  4974.1  237.79  4992.3  235.19  5049.6  237.79
  5056.5  246.93  5108.5  250.36  5164.5  248.84    5198  253.47  5495.1  252.52
  5581.7  259.37  5712.5  258.65  5849.9     249  5894.5  258.62  5930.9  258.87
  5975.6  249.98  6025.7  249.68  6084.5  255.74  6338.7  264.91  7703.5  268.91
#Mann= 7 ,-1 , 0
  1735.5     .05       0  2407.2      .1       0  2966.4     .08       0
    2989     .05       0  3069.2      .1       0  4974.1     .07       0
  5049.6      .1       0
Bank Sta=4974.1,5049.6
XS Rating Curve= 0 ,0
Exp/Cntr=0.3,0.1

Type RM Length L Ch R = 1 ,57909   ,157,157,157
BEGIN DESCRIPTION:
Mapping XS 62b93c98
END DESCRIPTION:
XS GIS Cut Line= 6
      2123752.26     13400595.64      2122975.46     13397351.44
      2123333.54     13396353.18       2123997.3     13395816.86
      2124005.63     13395584.92      2122325.57     13394055.56
#Sta/Elev= 30
  -374.9  272.13   -34.9     271   170.7  270.38   796.2  268.49   898.4  268.18
  1000.7  267.87  1460.6  266.49  1679.7  253.78    1739  258.23  2624.6  263.46
  2927.6  259.39    3361   260.5  3427.6  256.43  3601.3  251.46  4754.2  249.68
  4948.3  247.55  4953.3  246.55  4960.3  236.13  4978.5  233.53  5035.8  236.13
  5048.5  245.14  5098.5  243.78  5154.8  254.07  5341.6  261.79    5491  262.71
  5607.6  253.44  6075.1  251.88  6294.5  252.96  6368.9  262.06  7398.4  271.55
#Mann= 12 ,-1 , 0
  -374.9      .1       0   -34.9     .05       0   170.7      .1       0
   796.2     .08       0   898.4     .05       0  1000.7      .1       0
  2624.6     .05       0  2927.6      .1       0  3427.6     .05       0
  4754.2      .1       0  4960.3     .07       0  5035.8      .1       0
Bank Sta=4960.3,5035.8
XS Rating Curve= 0 ,0
Exp/Cntr=0.3,0.1

Type RM Length L Ch R = 1 ,57752   ,2428,2428,2428
BEGIN DESCRIPTION:
Mapping XS b26a7949
END DESCRIPTION:
XS GIS Cut Line= 6
      2123911.98     13400522.71      2123159.92     13397308.04
      2123485.45     13396450.83      2124125.64     13395897.45
      2124147.34     13395582.78      2122495.96     13394022.61
#Sta/Elev= 30
  -266.8  268.29    66.4  264.69   161.8  264.71   824.6  264.81   926.9  264.83
  1518.8  264.92  1729.7  252.76  1798.7  258.59  2748.5  264.85    3133  257.55
  3454.5  258.82  3701.7  250.92  4695.8  249.88  4914.8  246.66  4952.8  242.19
    4959  236.74  4977.3  234.14  5034.5  236.74  5046.9  243.27    5097  255.04
  5258.4  253.96  5402.1  260.66  5590.7  262.26  5728.8  249.46  5860.1  250.11
  6203.5  264.55  6362.9  264.41  6465.8  258.59  7199.1  274.45  7416.1   271.8
#Mann= 9 ,-1 , 0
  -266.8      .1       0    66.4     .05       0   161.8      .1       0
   824.6     .08       0   926.9      .1       0  2748.5     .05       0
    3133      .1       0    4959     .07       0  5034.5      .1       0
Bank Sta=4959,5034.5
XS Rating Curve= 0 ,0
Exp/Cntr=0.3,0.1

Type RM Length L Ch R = 1 ,55324   ,3352,3352,3352
BEGIN DESCRIPTION:
San Miguel Creek 12.0
END DESCRIPTION:
XS GIS Cut Line= 3
      2127814.88      13398497.2       2125470.8     13395864.54
       2123103.5      13393934.6
#Sta/Elev= 30
    1475  270.36  2057.8  268.97  2297.9   268.4  3094.3  266.51  4215.7  263.84
  4447.9  263.12  4452.6  263.06  4575.1  261.26  4656.6  255.35  4713.5  259.57
  4858.6  247.48  4925.9  245.13  4940.1  241.12    4943  232.72  4962.3  230.02
  5022.3  232.72  5028.9  242.46  5060.8  246.49  5394.7   247.9  5444.3  257.08
  5480.2  258.55  6048.9  253.72  6076.9  250.89  6204.7  253.04  6262.2  243.58
  6297.3  249.44  6457.1  260.51  6755.8  254.43  6844.5  259.46  8054.3  273.03
#Mann= 9 ,-1 , 0
    1475      .1       0  2057.8     .07       0  2297.9      .1       0
  3094.3     .05       0  4215.7     .08       0  4447.9     .05       0
  4452.6      .1       0    4943     .07       0  5022.3      .1       0
Bank Sta=4943,5022.3
XS Rating Curve= 0 ,0
Exp/Cntr=0.3,0.1

Type RM Length L Ch R = 1 ,51972   ,3048,3048,3048
BEGIN DESCRIPTION:
San Miguel Creek 11.0
END DESCRIPTION:
XS GIS Cut Line= 3
      2128684.24     13397523.68       2124840.8     13393084.54
      2123627.31     13392312.05
#Sta/Elev= 30
  -871.8  281.08  -579.2   267.6  -122.7  262.86   413.2  263.02   746.6  263.51
   906.2  267.39    1431  262.95  1629.5  257.75  1809.9  260.44  2536.5   258.6
  2632.5  250.78  2727.9  259.78  2802.5  256.12  2988.5  257.13  3094.8   254.4
  3797.6  253.97  4075.9  252.41  4387.2  246.38  4695.4  247.91  4961.4  242.62
  4968.5  241.86  4970.8  233.37  4990.2  230.67  5050.4  233.37  5054.6  236.93
  5109.3  244.69    5141  260.53  5166.8  265.52  5768.5  265.07  6438.5  269.78
#Mann= 9 ,-1 , 0
  -871.8      .1       0  -122.7     .05       0   413.2      .1       0
  2988.5     .08       0  3094.8      .1       0  3797.6     .05       0
  4075.9      .1       0  4970.8     .07       0  5050.4      .1       0
Bank Sta=4970.8,5050.4
XS Rating Curve= 0 ,0
Exp/Cntr=0.3,0.1

Type RM Length L Ch R = 1 ,48924   ,2663,2663,2663
BEGIN DESCRIPTION:
San Miguel Creek 10.0
END DESCRIPTION:
XS GIS Cut Line= 3
        2130881.     13395376.94       2127200.8     13391794.54
      2124174.11     13390541.28
#Sta/Elev= 30
  -135.9  273.68  1816.2  263.01  1917.9  262.47    3006  255.68  3147.5  246.95
    3599  251.02  3713.2  252.05  3732.2  252.22    4141  251.21  4208.2   242.2
  4300.1  240.51  4890.6  252.59  4918.9  241.23  4943.6  238.62  4946.1  226.38
  4965.6  223.68  5026.1  226.38  5026.4  235.01  5050.6  237.65    5052  237.65
  5306.6  240.58  5447.3   255.8  5731.1  254.42  5834.8  239.15  5911.8  256.71
  6175.1  255.58  6248.3  250.11  6305.4  255.61  7072.1  260.97  8275.9  269.38
#Mann= 11 ,-1 , 0
  -135.9      .1       0  1816.2     .05       0  1917.9      .1       0
    3599     .05       0  3713.2     .08       0  3732.2      .1       0
  4946.1     .07       0  5026.1      .1       0  5050.6     .12       0
    5052      .1       0  7072.1     .05       0
Bank Sta=4946.1,5026.1
XS Rating Curve= 0 ,0
Exp/Cntr=0.3,0.1

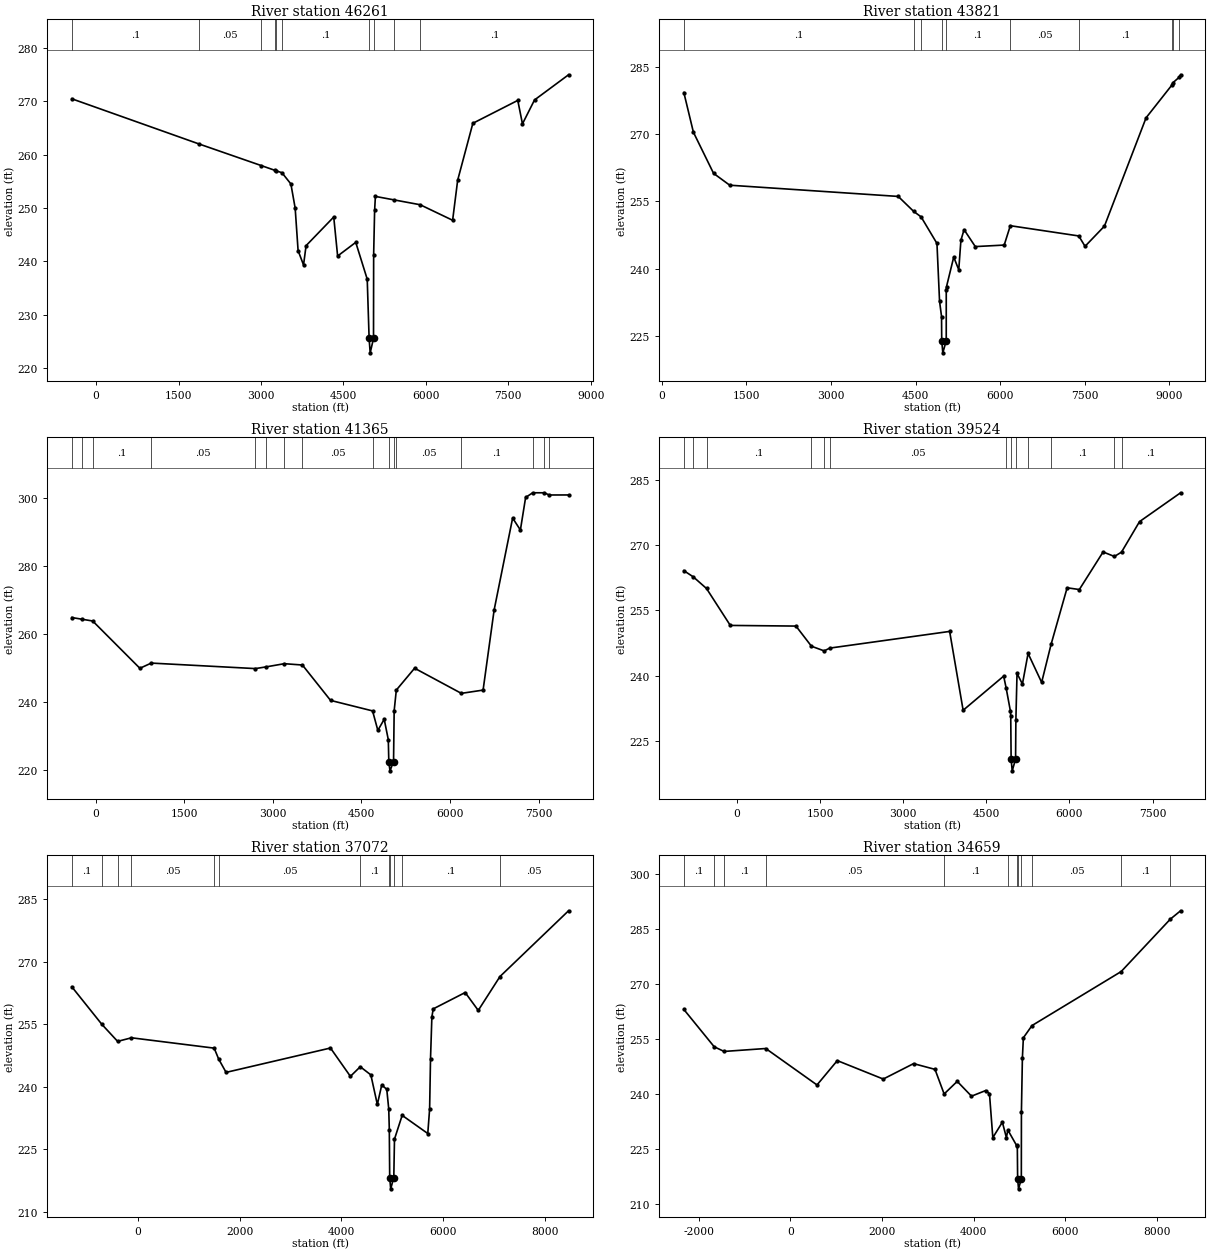
Type RM Length L Ch R = 1 ,46261   ,2440,2440,2440
BEGIN DESCRIPTION:
San Miguel Creek 9.0
END DESCRIPTION:
XS GIS Cut Line= 3
      2132710.93     13393324.12       2128620.8     13389734.54
      2125969.33      13387305.8
#Sta/Elev= 30
  -441.9  270.46    1877  261.98  3006.8  257.94  3254.8  257.05  3275.1  256.98
  3382.1   256.6    3544   254.5  3621.9  249.97    3675  242.02  3774.2  239.32
  3820.2  242.94  4323.6  248.31  4394.3     241    4724  243.56  4932.8  236.66
  4967.3  225.56  4986.8  222.86  5047.3  225.56  5049.8  241.28  5067.4  249.56
  5081.6  252.17  5425.1  251.51  5895.8  250.61  6486.6   247.7  6578.5  255.21
  6854.7  265.87  7672.1  270.16  7757.2  265.76  7976.4  270.24  8595.7  274.96
#Mann= 10 ,-1 , 0
  -441.9      .1       0    1877     .05       0  3006.8      .1       0
  3254.8     .05       0  3275.1     .08       0  3382.1      .1       0
  4967.3     .07       0  5047.3      .1       0  5425.1     .05       0
  5895.8      .1       0
Bank Sta=4967.3,5047.3
XS Rating Curve= 0 ,0
Exp/Cntr=0.3,0.1

Type RM Length L Ch R = 1 ,43821   ,2456,2456,2456
BEGIN DESCRIPTION:
San Miguel Creek 8.0
END DESCRIPTION:
XS GIS Cut Line= 3
      2133603.13     13391460.85      2130191.79     13388361.86
      2126404.86     13386550.11
#Sta/Elev= 30
   391.2  279.23   560.5   270.4     918  261.24  1204.5   258.6    4192   256.1
  4464.7  252.78  4597.2  251.55  4878.6  245.63  4924.7  232.76    4960  229.35
    4963  223.97  4982.6  221.27  5043.3  223.97  5043.6  235.22  5048.5  236.03
  5175.9  242.59  5265.3  239.77  5303.4  246.35  5359.5   248.7  5558.3  244.93
    6071  245.27  6179.3  249.58  7392.5   247.3  7504.3  244.99  7848.2  249.49
  8586.2  273.61  9045.8  280.93  9063.9  281.44  9171.3  282.62    9198  283.19
#Mann= 10 ,-1 , 0
   391.2      .1       0  4464.7     .05       0  4597.2      .1       0
    4963     .07       0  5043.3      .1       0  6179.3     .05       0
  7392.5      .1       0  9045.8     .05       0  9063.9     .08       0
  9171.3     .05       0
Bank Sta=4963,5043.3
XS Rating Curve= 0 ,0
Exp/Cntr=0.3,0.1

Type RM Length L Ch R = 1 ,41365   ,1841,1841,1841
BEGIN DESCRIPTION:
San Miguel Creek 7.0
END DESCRIPTION:
XS GIS Cut Line= 4
      2134364.73     13388683.48      2130862.12     13386508.99
       2129610.8     13386214.54       2126635.6     13385766.81
#Sta/Elev= 30
  -408.2  264.77  -241.5  264.29   -54.5  263.75   745.2  249.85   938.1  251.38
    2702  249.76  2879.5  250.25  3192.8   251.2  3499.3  250.81  3976.1  240.41
  4687.9  237.32  4777.3   231.6  4885.2  234.86  4954.5  228.87  4963.2   222.4
  4982.8   219.7  5043.5   222.4  5053.9  237.37  5090.3  243.44  5400.2  249.87
    6192  242.48  6560.7  243.44  6747.8  266.99  7061.2  294.02  7192.7   290.5
  7281.4  300.08  7401.1  301.45  7598.9  301.45  7679.6   300.8  8008.7  300.81
#Mann= 16 ,-1 , 0
  -408.2      .1       0  -241.5     .05       0   -54.5      .1       0
   938.1     .05       0    2702      .1       0  2879.5     .05       0
  3192.8      .1       0  3499.3     .05       0  4687.9      .1       0
  4963.2     .07       0  5043.5      .1       0  5090.3     .05       0
    6192      .1       0  7401.1     .08       0  7598.9     .05       0
  7679.6      .1       0
Bank Sta=4963.2,5043.5
XS Rating Curve= 0 ,0
Exp/Cntr=0.3,0.1

Type RM Length L Ch R = 1 ,39524   ,2452,2452,2452
BEGIN DESCRIPTION:
San Miguel Creek 6.0
END DESCRIPTION:
XS GIS Cut Line= 4
      2134343.92     13388246.01      2130728.78     13384844.06
       2129790.8     13384514.54      2126811.14     13384123.56
#Sta/Elev= 30
  -958.3  264.14  -787.2  262.71  -549.5  260.04    -120  251.54  1064.9  251.39
  1344.4  246.75  1573.4  245.68  1675.3  246.32    3838  250.16  4081.4  232.01
  4812.7  239.87  4856.5   237.2  4934.6  231.82  4940.4  230.74  4947.4  220.77
    4967  218.07  5027.8  220.77    5033  229.67  5053.8  240.51  5151.1  238.04
  5253.3  245.09  5498.1  238.43  5667.9  247.16  5958.1   260.2  6178.3   259.8
    6607  268.45  6811.2  267.41  6939.2  268.41  7264.5  275.43  8005.2  282.07
#Mann= 13 ,-1 , 0
  -958.3      .1       0  -787.2     .05       0  -549.5      .1       0
  1344.4     .05       0  1573.4      .1       0  1675.3     .05       0
  4856.5      .1       0  4947.4     .07       0  5027.8      .1       0
  5253.3     .05       0  5667.9      .1       0  6811.2     .05       0
  6939.2      .1       0
Bank Sta=4947.4,5027.8
XS Rating Curve= 0 ,0
Exp/Cntr=0.3,0.1

Type RM Length L Ch R = 1 ,37072   ,2413,2413,2413
BEGIN DESCRIPTION:
San Miguel Creek 5.0
END DESCRIPTION:
XS GIS Cut Line= 3
      2134531.39     13388100.14        2131175.       13382825.
      2127927.26     13381516.82
#Sta/Elev= 30
 -1294.4  263.98    -705  254.99  -394.9   250.9  -123.2  251.76  1500.8  249.28
  1589.2  246.66  1734.7  243.47  3784.5  249.31  4175.7  242.52  4369.5  244.82
  4577.4  242.87  4704.8  235.78  4791.2  240.45  4889.8  239.41  4928.7  234.71
  4939.8  229.77  4947.4  218.26    4967  215.56  5027.9  218.26  5041.5  227.47
  5192.4  233.17  5695.2  228.82  5731.5  234.69    5749  246.72  5775.8   256.8
  5802.7  258.69  6429.8  262.61  6686.3  258.32  7112.1  266.43  8459.3   282.2
#Mann= 12 ,-1 , 0
 -1294.4      .1       0    -705     .05       0  -394.9      .1       0
  -123.2     .05       0  1500.8      .1       0  1589.2     .05       0
  4369.5      .1       0  4928.7     .12       0  4947.4     .07       0
  5027.9     .12       0  5192.4      .1       0  7112.1     .05       0
Bank Sta=4947.4,5027.9
XS Rating Curve= 0 ,0
Exp/Cntr=0.3,0.1

Type RM Length L Ch R = 1 ,34659   ,2539,2539,2539
BEGIN DESCRIPTION:
San Miguel Creek 4.0
END DESCRIPTION:
XS GIS Cut Line= 3
      2134698.07     13387975.17       2131980.8     13381174.54
       2129411.6     13378782.44
#Sta/Elev= 30
 -2323.4  263.01 -1661.3  252.83 -1446.2  251.56  -537.1  252.36   580.5  242.42
  1023.2  249.06  2025.7  244.03    2687  248.24  3154.3  246.67  3353.6  239.96
  3639.2   243.4  3950.3  239.36  4258.7  240.89  4342.2  240.06  4415.3  228.06
  4623.7  232.27  4711.4  228.06    4743  230.13  4932.2  225.95  4949.6   225.7
  4956.5  216.79  4976.2  214.09  5037.1  216.79    5039  235.02  5060.3  249.77
  5081.6  255.29    5270  258.62  7215.3  273.35    8286  287.63  8510.4  289.92
#Mann= 12 ,-1 , 0
 -2323.4      .1       0 -1661.3     .08       0 -1446.2      .1       0
  -537.1     .05       0  3353.6      .1       0    4743     .12       0
  4932.2      .1       0  4956.5     .07       0  5037.1      .1       0
    5270     .05       0  7215.3      .1       0    8286     .05       0
Bank Sta=4956.5,5037.1
XS Rating Curve= 0 ,0
Exp/Cntr=0.3,0.1