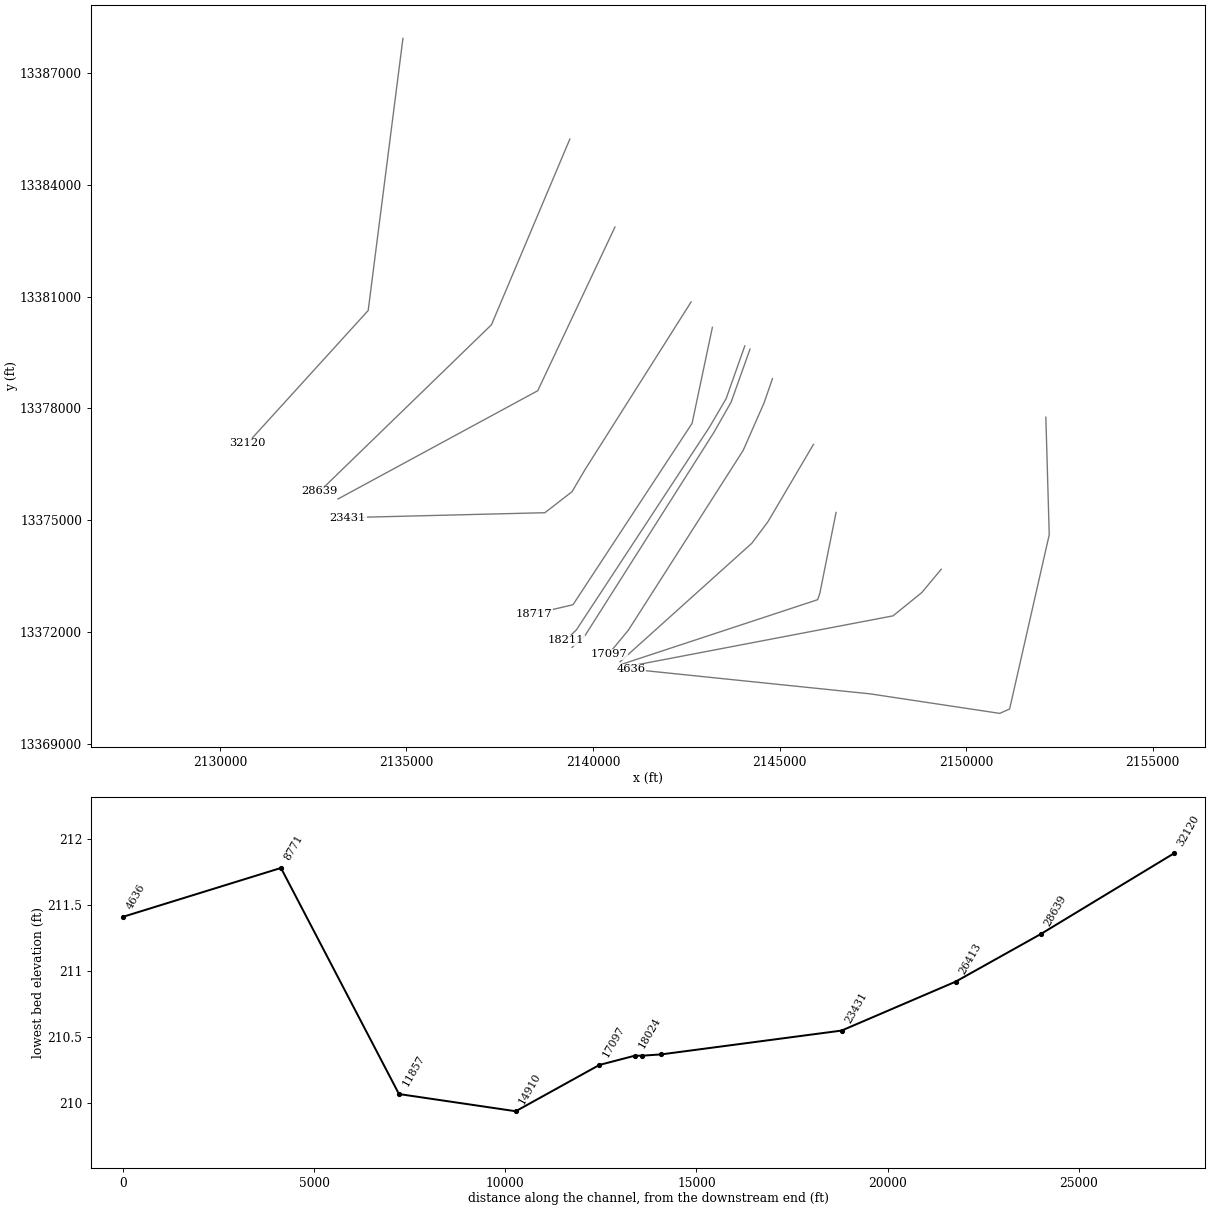
HEC-RAS study San Miguel Creek.prj: San Miguel Creek Base Level Engineering

--- San Miguel Creek.g01 (geometry) --- (continued)

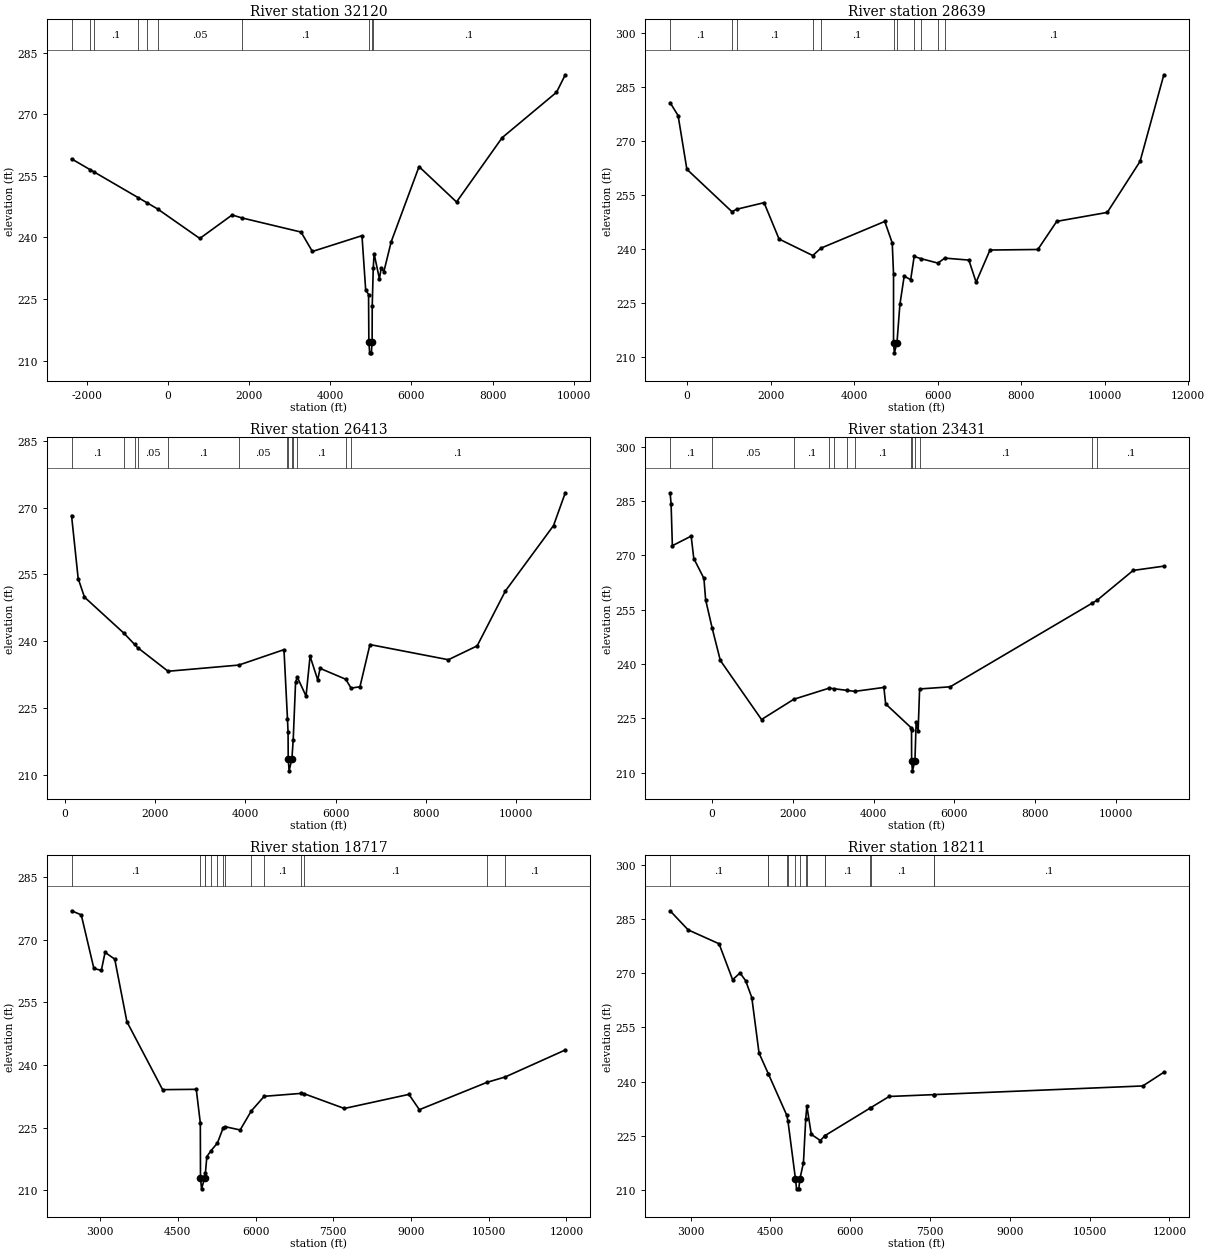
Type RM Length L Ch R = 1 ,32120   ,3481,3481,3481
BEGIN DESCRIPTION:
San Miguel Creek 3.0
END DESCRIPTION:
XS GIS Cut Line= 3
      2134906.39      13387923.1        2133975.       13380625.
      2130739.75     13377063.71
#Sta/Elev= 30
 -2374.8  259.14 -1919.2  256.52 -1819.4  255.95  -726.4  249.66  -519.4  248.47
  -254.2  246.94   786.2  239.75  1582.6  245.47  1826.5  244.75  3281.3  241.31
  3560.8  236.58  4782.9  240.43  4874.1  227.25  4945.1   226.1  4952.7  214.59
  4972.3  211.89  5013.6  211.89  5033.3  214.59  5035.5  223.27  5060.9  232.47
  5081.5  236.05  5212.6  229.93  5258.5   232.6  5322.4  231.67  5502.8  238.93
  6189.4  257.25  7113.5  248.63  8238.9  264.31  9576.9  275.35  9793.9  279.62
#Mann= 10 ,-1 , 0
 -2374.8      .1       0 -1919.2     .08       0 -1819.4      .1       0
  -726.4     .05       0  -519.4      .1       0  -254.2     .05       0
  1826.5      .1       0  4952.7     .07       0  5033.3      .1       0
  5060.9      .1       0
Bank Sta=4952.7,5033.3
XS Rating Curve= 0 ,0
Exp/Cntr=0.3,0.1

Type RM Length L Ch R = 1 ,28639   ,2226,2226,2226
BEGIN DESCRIPTION:
San Miguel Creek 2.0
END DESCRIPTION:
XS GIS Cut Line= 3
      2139379.51     13385222.71      2137278.37     13380242.28
      2132675.03     13375775.03
#Sta/Elev= 30
  -405.5  280.67  -213.2  277.07    -3.7  262.19  1075.5  250.42  1186.1  251.09
  1844.2  252.92  2203.4  242.84  3011.2  238.26  3203.6   240.3  4733.9  247.72
  4912.9  241.74  4943.6  233.13  4943.7  213.98  4963.7  211.28  5025.5  213.98
  5095.9  224.69  5198.5  232.54  5354.1  231.57  5437.7  238.01  5594.1  237.42
  6006.5  236.17  6169.4  237.55  6747.2     237  6920.5  230.87  7252.8  239.79
  8398.5  239.94  8851.1  247.74 10060.3  250.22 10845.4  264.37 11414.6  288.39
#Mann= 11 ,-1 , 0
  -405.5      .1       0  1075.5     .05       0  1186.1      .1       0
  3011.2     .05       0  3203.6      .1       0  4943.7     .07       0
  5025.5     .12       0  5437.7     .16       0  5594.1      .1       0
  6006.5     .16       0  6169.4      .1       0
Bank Sta=4943.7,5025.5
XS Rating Curve= 0 ,0
Exp/Cntr=0.3,0.1

Type RM Length L Ch R = 1 ,26413   ,2982,2982,2982
BEGIN DESCRIPTION:
Mapping XS d2d75124
END DESCRIPTION:
XS GIS Cut Line= 3
      2140587.81     13382862.28      2138518.61     13378473.62
      2133165.95     13375570.63
#Sta/Elev= 30
     148  268.23   294.8  254.09   434.2  249.91  1314.3  241.76  1544.5   239.3
  1609.9   238.6    2287  233.27  3855.2  234.66  4855.4  238.12  4932.8  222.61
    4946  219.59  4949.3  213.62  4969.3  210.92  5031.1  213.62  5059.8  217.83
  5112.3  230.78  5150.1  231.97  5344.3  227.69  5433.6  236.65  5603.4  231.32
  5655.2  233.92  6224.1  231.48  6342.3  229.48  6539.3   229.8  6760.4  239.26
  8498.3  235.86  9136.4  238.97  9762.1  251.29 10828.5  265.97 11089.2  273.33
#Mann= 13 ,-1 , 0
     148      .1       0  1314.3     .05       0  1544.5      .1       0
  1609.9     .05       0    2287      .1       0  3855.2     .05       0
  4932.8     .12       0  4949.3     .07       0  5031.1     .12       0
  5059.8     .12       0  5150.1      .1       0  6224.1     .16       0
  6342.3      .1       0
Bank Sta=4949.3,5031.1
XS Rating Curve= 0 ,0
Exp/Cntr=0.3,0.1

Type RM Length L Ch R = 1 ,23431   ,4714,4714,4714
BEGIN DESCRIPTION:
Mapping XS b206f84a
END DESCRIPTION:
XS GIS Cut Line= 5
      2142628.91     13380854.66      2139784.57     13376355.93
      2139437.35     13375765.65      2138711.16     13375202.48
      2133430.38      13375071.2
#Sta/Elev= 30
 -1031.7  287.26 -1007.1  284.29  -975.3  272.66  -510.7   275.3  -445.4  269.12
  -195.1  263.64  -152.5  257.73      10  249.87   210.4  241.01  1229.1  224.71
  2028.5   230.3  2903.5  233.37  3015.4  233.21  3332.9  232.76  3536.3  232.47
  4254.5  233.56  4298.7  229.01    4926  222.47  4938.3  221.82  4940.7  213.25
  4960.8  210.55  5022.7  213.25  5052.3  224.01  5102.1  221.67  5138.2  233.14
  5894.6  233.73  9400.4  256.78  9526.3  257.61 10418.9  265.84   11177  267.02
#Mann= 13 ,-1 , 0
 -1031.7      .1       0      10     .05       0  2028.5      .1       0
  2903.5     .16       0  3015.4      .1       0  3332.9     .16       0
  3536.3      .1       0    4926     .07       0  4940.7     .07       0
  5022.7     .07       0  5138.2      .1       0  9400.4     .05       0
  9526.3      .1       0
Bank Sta=4940.7,5022.7
XS Rating Curve= 0 ,0
Exp/Cntr=0.3,0.1

Type RM Length L Ch R = 1 ,18717   ,506,506,506
BEGIN DESCRIPTION:
Mapping XS 1f934d43
END DESCRIPTION:
XS GIS Cut Line= 4
      2143198.87     13380173.12      2142654.56     13377598.04
      2139462.72     13372734.48      2138409.42     13372488.08
#Sta/Elev= 30
  2448.4  276.87    2636  275.89  2879.5  263.07  3023.6  262.62  3095.6  266.92
    3282  265.31  3517.1  250.34  4206.2  234.09  4856.1  234.17  4934.2  226.12
  4937.5  213.07  4957.7  210.37  5019.9  213.07  5032.5  214.15  5060.5   218.1
    5144  219.53  5264.4  221.34  5377.6  225.02  5406.9  225.25    5703  224.45
  5918.5     229  6167.6   232.5  6871.6  233.19  6932.4  233.14  7714.3  229.59
  8960.6  232.96  9162.5   229.3 10470.2  235.85 10818.4  237.12 11979.5  243.58
#Mann= 14 ,-1 , 0
  2448.4      .1       0  4937.5     .07       0  5019.9      .1       0
  5032.5     .07       0    5144     .12       0  5264.4      .1       0
  5377.6     .12       0  5406.9      .1       0  5918.5     .16       0
  6167.6      .1       0  6871.6     .16       0  6932.4      .1       0
 10470.2     .05       0 10818.4      .1       0
Bank Sta=4937.5,5019.9
XS Rating Curve= 0 ,0
Exp/Cntr=0.3,0.1

Type RM Length L Ch R = 1 ,18211   ,187,187,187
BEGIN DESCRIPTION:
Mapping XS 5f0215e2
END DESCRIPTION:
XS GIS Cut Line= 5
      2144067.76     13379676.15      2143567.17     13378260.95
      2143121.47     13377498.14      2139555.36     13372062.17
      2139271.97     13371786.72
#Sta/Elev= 30
  2615.4  287.22  2954.8  281.94  3536.2   278.1  3790.9  268.16    3930  270.02
  4035.5   267.9  4151.5  263.22  4287.4  247.89  4461.3  242.19  4461.6  242.18
  4810.4  230.64  4831.8  229.01  4972.6  213.06  4992.7  210.36  5034.8  210.36
    5055  213.06  5122.3  217.59  5165.1  229.71  5186.9   233.2  5269.9  225.42
  5440.3  223.71  5526.5  225.07  5529.2  225.09  6369.6  232.63  6385.1  232.77
  6733.3  235.89  7574.1   236.4  7583.4  236.41 11501.3   238.8 11896.5  242.58
#Mann= 15 ,-1 , 0
  2615.4      .1       0  4461.3     .08       0  4461.6      .1       0
  4810.4     .05       0  4831.8      .1       0  4972.6     .07       0
    5055     .07       0  5165.1     .05       0  5186.9      .1       0
  5526.5     .08       0  5529.2      .1       0  6369.6     .08       0
  6385.1      .1       0  7574.1     .05       0  7583.4      .1       0
Bank Sta=4972.6,5055
XS Rating Curve= 0 ,0
Exp/Cntr=0.3,0.1

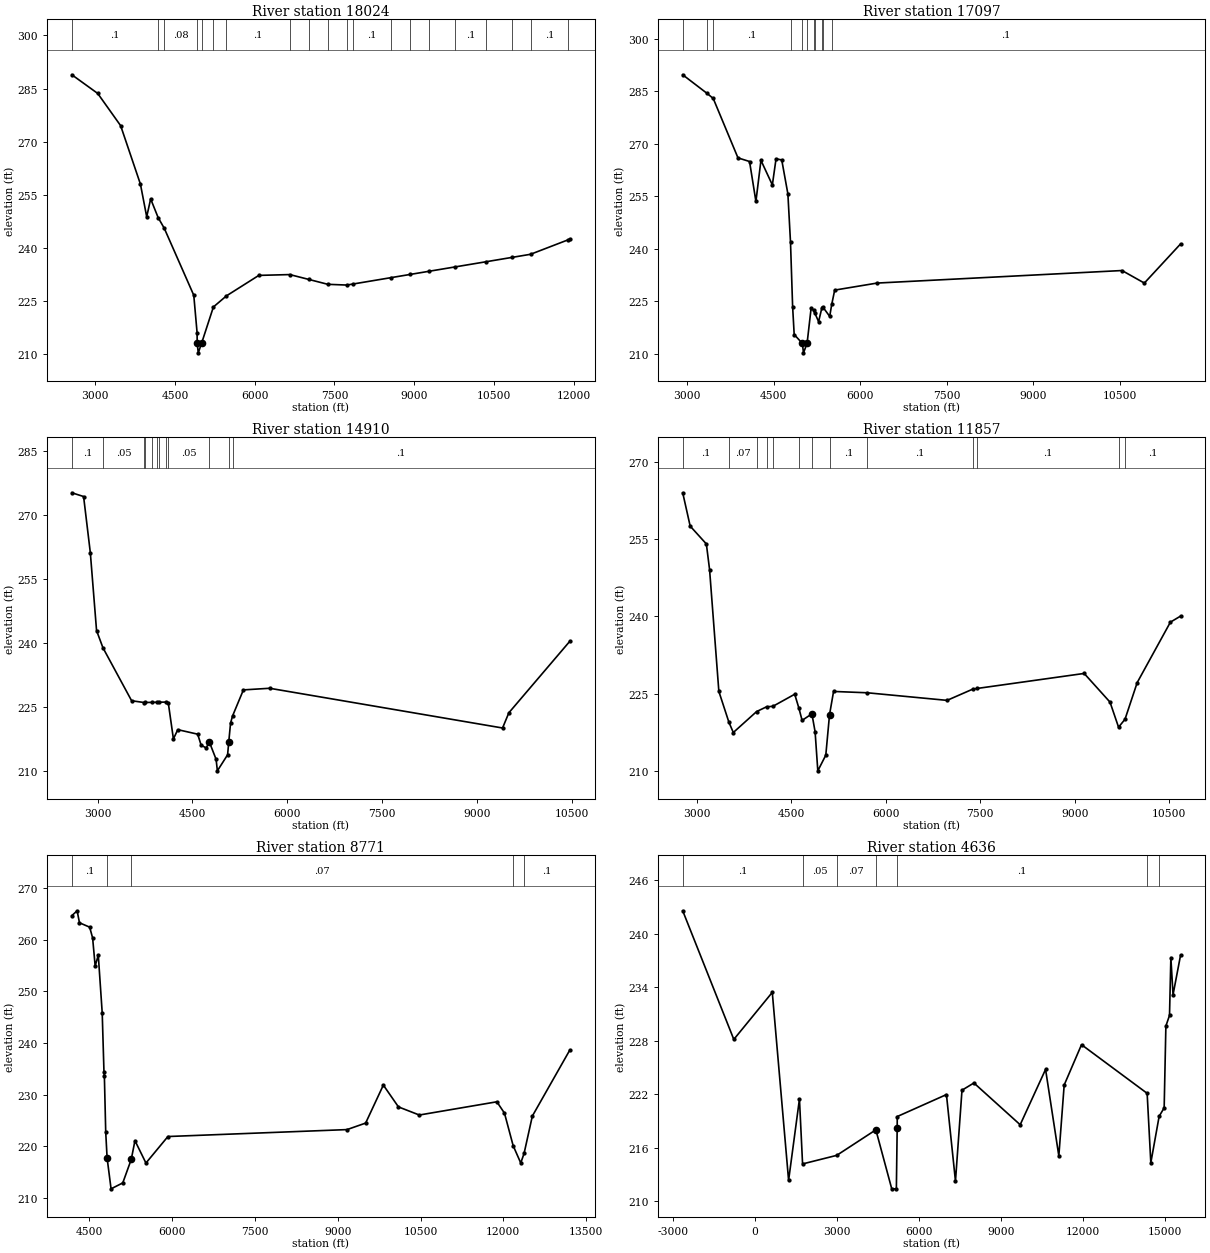
Type RM Length L Ch R = 1 ,18024   ,927,927,927
BEGIN DESCRIPTION:
San Miguel Creek 1.5
END DESCRIPTION:
XS GIS Cut Line= 5
       2144207.4     13379589.84      2143702.44     13378171.18
      2143242.49     13377360.86      2139792.08     13371917.39
      2139439.07     13371591.41
#Sta/Elev= 30
  2562.4  288.88  3048.6  283.61  3479.7  274.51  3851.9     258  3969.9  248.78
  4044.3  253.83  4184.9  248.55  4300.4  245.53  4855.2  226.62  4917.6  216.04
  4919.5  213.06  4939.7  210.36  5001.9  213.06  5224.3  223.31  5469.8  226.45
  6078.6  232.23  6661.3  232.46  7018.8  231.09  7376.3  229.71  7733.7   229.5
  7852.9   229.8  8567.9   231.6  8925.3   232.5  9282.8   233.4  9777.2  234.64
 10355.3  236.09 10831.9  237.29 11189.4  238.19   11897  242.28 11925.4  242.38
#Mann= 20 ,-1 , 0
  2562.4      .1       0  4184.9     .08       0  4300.4     .08       0
  4919.5     .07       0  5001.9     .05       0  5224.3     .05       0
  5469.8      .1       0  6661.3      .1       0  7018.8      .1       0
  7376.3      .1       0  7733.7      .1       0  7852.9      .1       0
  8567.9      .1       0  8925.3      .1       0  9282.8      .1       0
  9777.2      .1       0 10355.3      .1       0 10831.9      .1       0
 11189.4      .1       0   11897     .08       0
Bank Sta=4919.5,5001.9
XS Rating Curve= 0 ,0
Exp/Cntr=0.3,0.1

Type RM Length L Ch R = 1 ,17097   ,2187,2187,2187
BEGIN DESCRIPTION:
San Miguel Creek 1.2
END DESCRIPTION:
XS GIS Cut Line= 5
      2144809.11     13378797.24      2144583.42      13378146.2
        2144025.       13376875.      2140946.76      13372051.8
      2140416.73     13371410.07
#Sta/Elev= 30
  2922.5  289.68    3346  284.35  3451.5  282.92  3880.8  265.95  4081.3  264.92
  4191.8  253.51    4279  265.25  4476.8  258.23  4540.6  265.68  4639.5  265.37
  4746.1  255.67  4791.5  241.85  4828.3  223.43  4855.3  215.52  4996.6  212.99
  5016.7  210.29    5079  212.99  5148.5  222.99    5191  222.47  5212.1  221.68
  5278.8   219.2  5335.3  223.14  5348.6  223.44  5471.3   220.7  5506.1  224.11
  5557.6   228.2  6292.5  230.21 10539.6  233.79 10926.9  230.21 11554.1  241.37
#Mann= 11 ,-1 , 0
  2922.5      .1       0    3346     .05       0  3451.5      .1       0
  4791.5     .12       0  4996.6     .07       0    5079     .12       0
    5191      .1       0  5212.1     .12       0  5335.3      .1       0
  5348.6     .12       0  5506.1      .1       0
Bank Sta=4996.6,5079
XS Rating Curve= 0 ,0
Exp/Cntr=0.3,0.1

Type RM Length L Ch R = 1 ,14910   ,3053,3053,3053
BEGIN DESCRIPTION:
Mapping XS ee340dfe
END DESCRIPTION:
XS GIS Cut Line= 4
      2145908.26     13377036.15      2144688.94     13374962.24
      2144255.48     13374383.37      2140727.87     13371207.75
#Sta/Elev= 30
  2594.2  275.24  2779.7  274.36  2886.1  261.19  2984.8  242.88  3085.8  238.84
  3539.4   226.4  3739.6  225.98    3758  225.99  3856.2  226.02  3942.4  226.05
  3972.8  226.06  4089.3  226.09  4120.4  225.82  4200.5  217.44  4269.8  219.61
  4584.3  218.55    4640  215.94    4720  215.32  4767.7  216.76    4876  212.64
  4896.2  209.94  5057.8  213.71  5075.5  216.62  5104.7  221.16  5136.9  222.85
  5307.9  228.95  5723.2  229.33  9407.8     220  9507.2  223.57 10469.6  240.33
#Mann= 12 ,-1 , 0
  2594.2      .1       0  3085.8     .05       0  3739.6     .16       0
    3758     .12       0  3856.2     .16       0  3942.4     .12       0
  3972.8     .16       0  4089.3     .12       0  4120.4     .05       0
  4767.7    .033       0  5075.5     .07       0  5136.9      .1       0
Bank Sta=4767.7,5075.5
XS Rating Curve= 0 ,0
Exp/Cntr=0.3,0.1

Type RM Length L Ch R = 1 ,11857   ,3086,3086,3086
BEGIN DESCRIPTION:
Mapping XS 5c63a815
END DESCRIPTION:
XS GIS Cut Line= 4
      2146513.53     13375209.78      2146076.09     13373031.57
      2146018.21     13372869.49      2140790.41     13371145.29
#Sta/Elev= 30
  2778.3  263.97  2896.6  257.51  3153.6  254.05  3204.5  249.08  3351.8  225.46
  3511.6  219.48  3581.1   217.5  3950.7  221.56  4108.3  222.48  4209.5  222.58
  4555.4  224.92  4621.7  222.22  4672.7  219.85    4828  221.12  4878.9  217.64
  4921.8  210.07  5048.6  213.11  5107.6  220.94  5171.8  225.46    5709   225.2
  6972.6  223.73    7377  225.89  7450.1  226.04  9147.9  228.95  9558.1  223.39
  9693.6  218.53    9796  220.07  9989.5  227.18 10516.2  238.89 10676.9  240.06
#Mann= 13 ,-1 , 0
  2778.3      .1       0  3511.6     .07       0  3950.7     .12       0
  4108.3      .1       0  4209.5     .16       0  4621.7      .1       0
    4828    .033       0  5107.6      .1       0    5709      .1       0
    7377     .16       0  7450.1      .1       0  9693.6     .07       0
    9796      .1       0
Bank Sta=4828,5107.6
XS Rating Curve= 0 ,0
Exp/Cntr=0.3,0.1

Type RM Length L Ch R = 1 ,8771    ,4135,4135,4135
BEGIN DESCRIPTION:
Mapping XS 6dbcb558
END DESCRIPTION:
XS GIS Cut Line= 4
      2149332.05     13373686.93      2148811.24     13373061.95
       2148040.4     13372436.95      2140957.09     13371082.79
#Sta/Elev= 30
  4184.6  264.63  4279.9  265.57  4322.2  263.25    4507   262.4  4560.4  260.32
  4606.6  254.89  4663.2  256.98  4734.2  245.82  4766.1  234.39  4773.2  233.69
    4798  222.68  4822.7  217.77  4894.5  211.78  5106.8  212.93  5260.2  217.47
  5327.4   221.1  5526.4  216.77  5924.4   221.9  9168.5  223.24  9505.9   224.5
  9826.7  231.85 10100.3  227.63 10478.2  226.06 11883.1  228.62   12021  226.42
 12178.4  220.12 12315.9  216.78 12376.3  218.64 12525.9  225.86 13202.1  238.58
#Mann= 5 ,-1 , 0
  4184.6      .1       0  4822.7    .033       0  5260.2     .07       0
 12178.4     .07       0 12376.3      .1       0
Bank Sta=4822.7,5260.2
XS Rating Curve= 0 ,0
Exp/Cntr=0.3,0.1

Type RM Length L Ch R = 1 ,4636    ,0,0,0
BEGIN DESCRIPTION:
San Miguel Creek 1.0
END DESCRIPTION:
XS GIS Cut Line= 6
      2152135.02     13377764.26      2152226.17     13374613.17
      2151164.05     13369938.93      2150898.04      13369821.5
      2147427.13     13370344.81      2141015.19      13371006.4
#Sta/Elev= 30
 -2639.7  242.56  -772.2  228.15   633.6  233.42  1230.4  212.36  1626.7  221.47
  1740.8   214.2  2988.8  215.16  4418.9  218.02    5000  211.41  5168.7  211.41
  5198.7  218.28  5201.4  219.51    6999  221.97  7328.8  212.27  7567.1  222.46
  8002.6  223.27  9693.7  218.59 10621.5  224.79 11106.4   215.1 11301.8  223.04
 11935.1  227.56 14333.8  222.11 14468.4  214.33 14772.8  219.54 14955.8  220.48
 15018.8  229.65 15151.3  230.84 15200.7  237.32 15280.1  233.15 15553.9  237.56
#Mann= 7 ,-1 , 0
 -2639.7      .1       0  1740.8     .05       0  2988.8     .07       0
  4418.9    .033       0  5201.4      .1       0 14333.8     .07       0
 14772.8      .1       0
Bank Sta=4418.9,5198.7
XS Rating Curve= 0 ,0
Exp/Cntr=0.3,0.1
LCMann Table=0

Chan Stop Cuts=-1
Use User Specified Reach Order=0
Composite Channel Slope=5